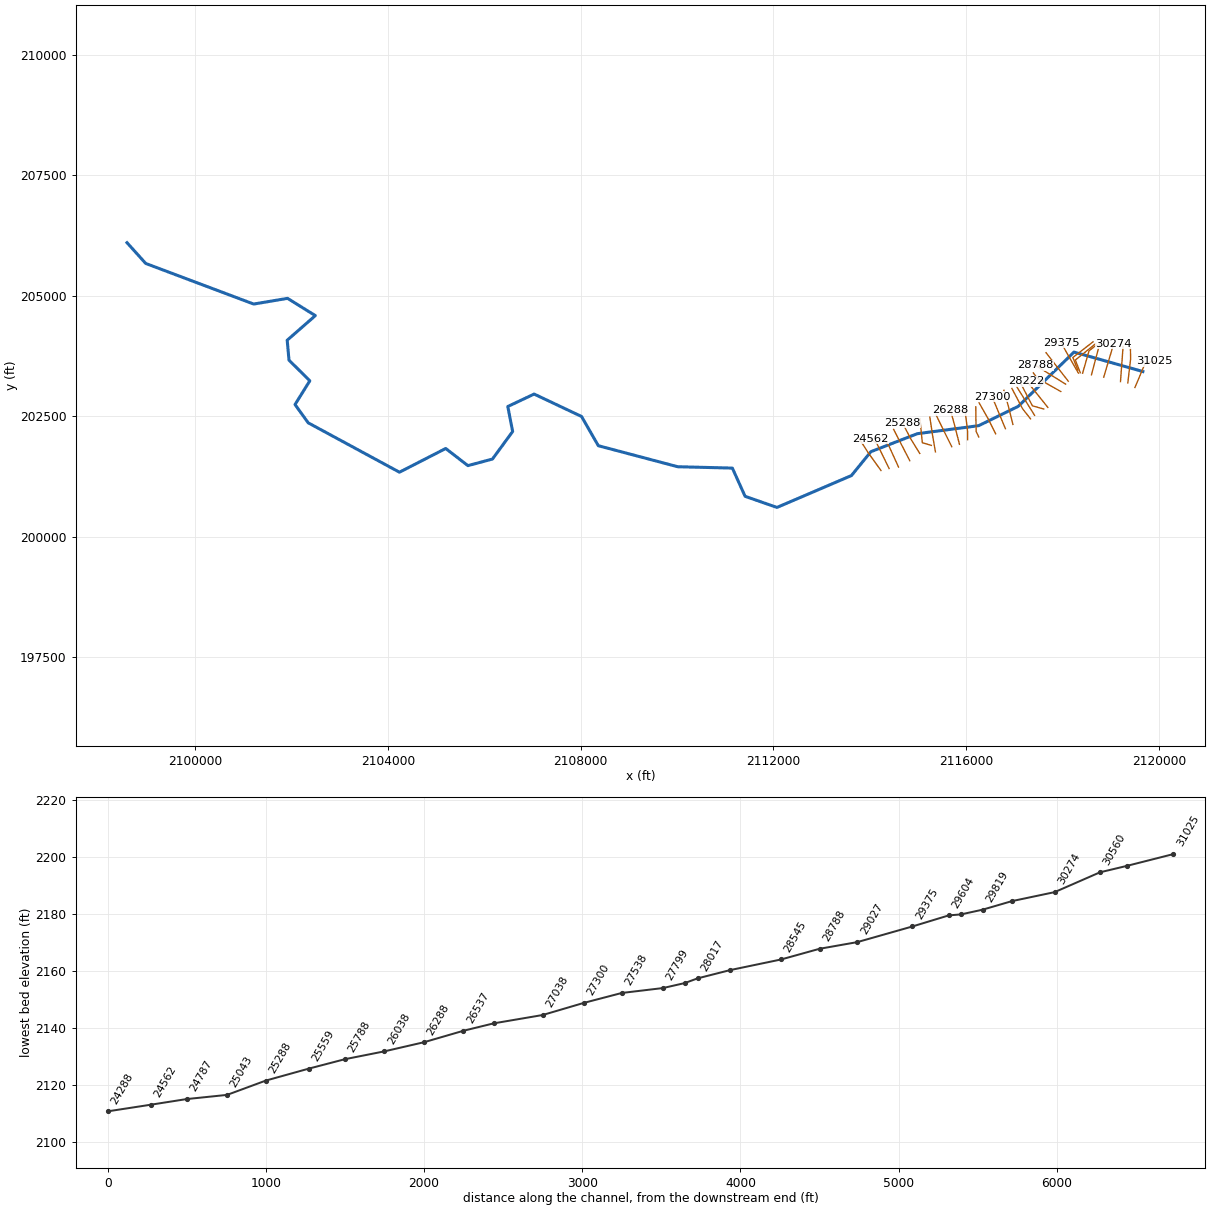
--- TCKTTBR.prj (project) ---

Proj Title=TCKTTBR
Current Plan=p01
Default Exp/Contr=0,0
English Units
Geom File=g01
Flow File=f01
Plan File=p01
Background Map Layer=Inundation Boundary (01pct Value_0)
Background Map Layer=Inundation Boundary (01pct Value_0)
BEGIN DESCRIPTION:
Stream Name: Tackett Branch
Flood Zone: Approximate
Monroe County, West Virginia
HEC-RAS Version: 5.0.7
Vertical Datum: NAVD88
Projection: NAD 1983 StatePlane West Virginia S FIPS 4702 (US Feet)
LiDAR: 2016, 1-meter
Land Use: 2016 NLCD
Hydrologic Method:
SIR2010-5033 regression equations
General Notes- Stream is in the karst. Cross section 714 shows a depression because of Karst.
For this hydrologic study, all flows were assumed to occur on the surface without any storage. Disconnects in the
30-meter hydrologic DEM were hydroconditioned using LiDAR, imagery, and dye tracer data (WVDEP, 2013).
END DESCRIPTION:
DSS File=dss
DSS Export Rating Curves= 0
DSS Export Rating Curve Sorted= 0
DSS Export Volume Flow Curves= 0
DXF Filename=INDIANCKT1.
DXF OffsetX= 0
DXF OffsetY= 0
DXF ScaleX= 0
DXF ScaleY= 0

--- TCKTTBR.p01 (plan) ---

Plan Title=Floodplain
Program Version=5.07
Short Identifier=Floodplain
Geom File=g01
Flow File=f01
Subcritical Flow
K Sum by GR= 0
Std Step Tol= 0.01
Critical Tol= 0.01
Num of Std Step Trials= 20
Max Error Tol= 0.3
Flow Tol Ratio= 0.001
Split Flow NTrial= 30
Split Flow Tol= 0.02
Split Flow Ratio= 0.02
Log Output Level= 0
Friction Slope Method= 1
Unsteady Friction Slope Method= 2
Unsteady Bridges Friction Slope Method= 1
Parabolic Critical Depth
Global Vel Dist= 0 , 0 , 0
Global Log Level= 0
CheckData=True
Encroach Param=-1 ,0,0, 0
Computation Interval=0.1SEC
Output Interval=1MIN
Instantaneous Interval=Max Profile
Mapping Interval=1HOUR
Computation Time Step Use Courant=        0
Computation Time Step Use Time Series=    0
Computation Time Step Count To Double=0
Computation Time Step Max Doubling=0
Computation Time Step Max Halving=0
Computation Time Step Residence Courant=0
Run HTab= 0
Run UNet= 0
Run Sediment= 0
Run PostProcess= 0
Run WQNet= 0
Run RASMapper=-1
UNET Theta= 0
UNET Theta Warmup= 0
UNET ZTol= 0
UNET ZSATol= 0
UNET MxIter= 0
UNET Max Iter WO Improvement= 0
UNET MaxInSteps= 0
UNET DtIC= 0
UNET DtMin= 0
UNET MaxCRTS= 0
UNET WFStab= 0
UNET SFStab= 0
UNET WFX= 1
UNET SFX= 1
UNET 1D Methodology=Finite Difference
UNET DSS MLevel= 1
UNET Pardiso=0
UNET DZMax Abort= 0
UNET Use Existing IB Tables= 0
UNET Froude Reduction=False
UNET Froude Limit= 0
UNET Froude Power= 0
UNET D1 Cores= 0
UNET D2 Coriolis=0
UNET D2 Cores= 0
UNET D2 Theta= 1
UNET D2 Theta Warmup= 1
UNET D2 Z Tol= 0.01
UNET D2 Volume Tol= 0.01
UNET D2 Max Iterations= 20
UNET D2 Equation= 0
UNET D2 RampUpFraction=0.1
UNET D2 TimeSlices= 1
UNET D2 BCVolumeCheck=0
UNET D1D2 MaxIter= 0
UNET D1D2 ZTol=0.01
UNET D1D2 QTol=0.1
UNET D1D2 MinQTol=1
DSS File=dss
Write IC File= 0
Write IC File at Fixed DateTime=0
Write IC File at Sim End=0
Echo Input=False
Echo Parameters=False
Echo Output=False
Write Detailed= 0
HDF Write Warmup=0
HDF Write Time Slices=0
HDF Flush=0
HDF Face Node Velocities=0
HDF Compression= 1
HDF Chunk Size= 1
HDF Spatial Parts= 1
HDF Use Max Rows=0
HDF Fixed Rows= 1
Calibration Method= 0
Calibration Iterations= 20
Calibration Max Change=0.05
Calibration Tolerance=0.2
Calibration Maximum=1.5
Calibration Minimum=0.5
Calibration Optimization Method= 1
WQ AD Non Conservative
WQ ULTIMATE=-1
WQ Max Comp Step=1HOUR
WQ Output Interval=15MIN
WQ Output Selected Increments= 0
WQ Output face flow=0
WQ Output face velocity=0
WQ Output face area=0
WQ Output face dispersion=0
WQ Output cell volume=0
WQ Output cell surface area=0
WQ Output cell continuity=0
WQ Output cumulative cell continuity=0
WQ Output face conc=0
WQ Output face dconc_dx=0
WQ Output face courant=0
WQ Output face peclet=0
WQ Output face adv mass=0
WQ Output face disp mass=0
WQ Output cell mass=0
WQ Output cell source sink temp=0
WQ Output nsm pathways=0
WQ Output nsm derived pathways=0
WQ Output MaxMinRange=-1
WQ Daily Max Min Mean=-1
WQ Daily Range=0
WQ Daily Time=0
WQ Create Restart=0
WQ Fixed Restart=0
WQ System Summary=0
WQ Write To DSS=0
WQ Use Fixed Temperature=0
Sorting and Armoring Iterations= 10
XS Update Threshold= 0.02
Bed Roughness Predictor= 0
Hydraulics Update Threshold= 0.02
Energy Slope Method= 1
Volume Change Method= 1
Sediment Retention Method= 0
XS Weighting Method= 0
Number of US Weighted Cross Sections= 1
Number of DS Weighted Cross Sections= 1
Upstream XS Weight=0
Main XS Weight=1
Downstream XS Weight=0
Number of DS XS's Weighted with US Boundary= 1
Upstream Boundary Weight= 1
Weight of XSs Associated with US Boundary= 0
Number of US XS's Weighted with DS Boundary= 1
Downstream Boundary Weight= 0.5
Weight of XSs Associated with DS Boundary= 0.5
Percentile Method= 0
Sediment Output Level= 3
Mass or Volume Output= 0
Output Increment Type= 1
Profile and TS Output Increment= 1
XS Output Flag= 0
XS Output Increment= 10
Write Gradation File= 0
Read Gradation Hotstart= 0
Write HDF5 File= 1
Write Binary Output= 1
Write DSS Sediment File= 0
SV Curve= 0
Specific Gage Flag= 0

--- TCKTTBR.f01 (steady flow) ---

Flow Title=Flow
Program Version=5.07
Number of Profiles= 6
Profile Names=01pct,10pct,04pct,02pct,0_2pct,01plus
River Rch & RM=TCKTTBR,Main            ,31025
     543     286     381     459     759     803
River Rch & RM=TCKTTBR,Main            ,30560
     603     319     424     511     841     891
River Rch & RM=TCKTTBR,Main            ,28017
     650     345     458     551     905     961
River Rch & RM=TCKTTBR,Main            ,26288
     705     376     497     598     981    1040
River Rch & RM=TCKTTBR,Main            ,24001
     858     461     608     729    1190    1270
River Rch & RM=TCKTTBR,Main            ,23295
     864     464     612     734    1200    1280
River Rch & RM=TCKTTBR,Main            ,23140
     955     515     678     812    1320    1410
River Rch & RM=TCKTTBR,Main            ,21690
    1000     541     711     852    1380    1480
River Rch & RM=TCKTTBR,Main            ,17982
    1110     602     791     946    1530    1640
River Rch & RM=TCKTTBR,Main            ,16732
    1160     631     828     990    1600    1720
River Rch & RM=TCKTTBR,Main            ,15371
    1280     697     913    1090    1760    1890
River Rch & RM=TCKTTBR,Main            ,12935
    1350     737     965    1150    1850    2000
River Rch & RM=TCKTTBR,Main            ,8698
    1500     822    1070    1280    2060    2220
Boundary for River Rch & Prof#=TCKTTBR,Main            , 1
Up Type= 0
Dn Type= 3
Dn Slope=0.021
Boundary for River Rch & Prof#=TCKTTBR,Main            , 2
Up Type= 0
Dn Type= 3
Dn Slope=0.021
Boundary for River Rch & Prof#=TCKTTBR,Main            , 3
Up Type= 0
Dn Type= 3
Dn Slope=0.021
Boundary for River Rch & Prof#=TCKTTBR,Main            , 4
Up Type= 0
Dn Type= 3
Dn Slope=0.021
Boundary for River Rch & Prof#=TCKTTBR,Main            , 5
Up Type= 0
Dn Type= 3
Dn Slope=0.021
Boundary for River Rch & Prof#=TCKTTBR,Main            , 6
Up Type= 0
Dn Type= 3
Dn Slope=0.021
DSS Import GetInterval= 0
DSS Import GetPeak= 0
DSS Import FillOption= 0

--- TCKTTBR.g01 (geometry) ---

Geom Title=Geometry
Program Version=5.07

River Reach=TCKTTBR         ,Main
Reach XY= 30
2119666.72299999203430.2960000042118237.68600002203833.941000015
2117079.91700003202707.6390000132116258.52000004202306.164000019
2114985.73300004202140.1480000022114022.19100004201766.884000003
     2113618.546201271.0069999992112073.01199999200609.523000002
2111411.51500002200840.2350000142111146.75800002201426.172000006
2110012.86000001201454.3840000182108365.72400001201890.582000002
     2108017.417202497.136000022     2107033.259202962.631000012
2106486.38400003202704.384000018     2106587.296202185.721000016
2106168.45900002201613.8890000132105658.47600001201477.171000004
     2105198.118201832.9140000052104238.04800001201340.727000013
2102343.95100003202365.9000000062102070.51300004202745.240999997
2102377.80500001203238.2960000042101945.51300004203666.247999996
2101908.18700004204080.3100000172102492.38800001204590.726999998
2101915.99900001204949.2340000122101212.64200002204830.996000022
2098971.98900002205673.6260000172098583.90400001206104.626000017

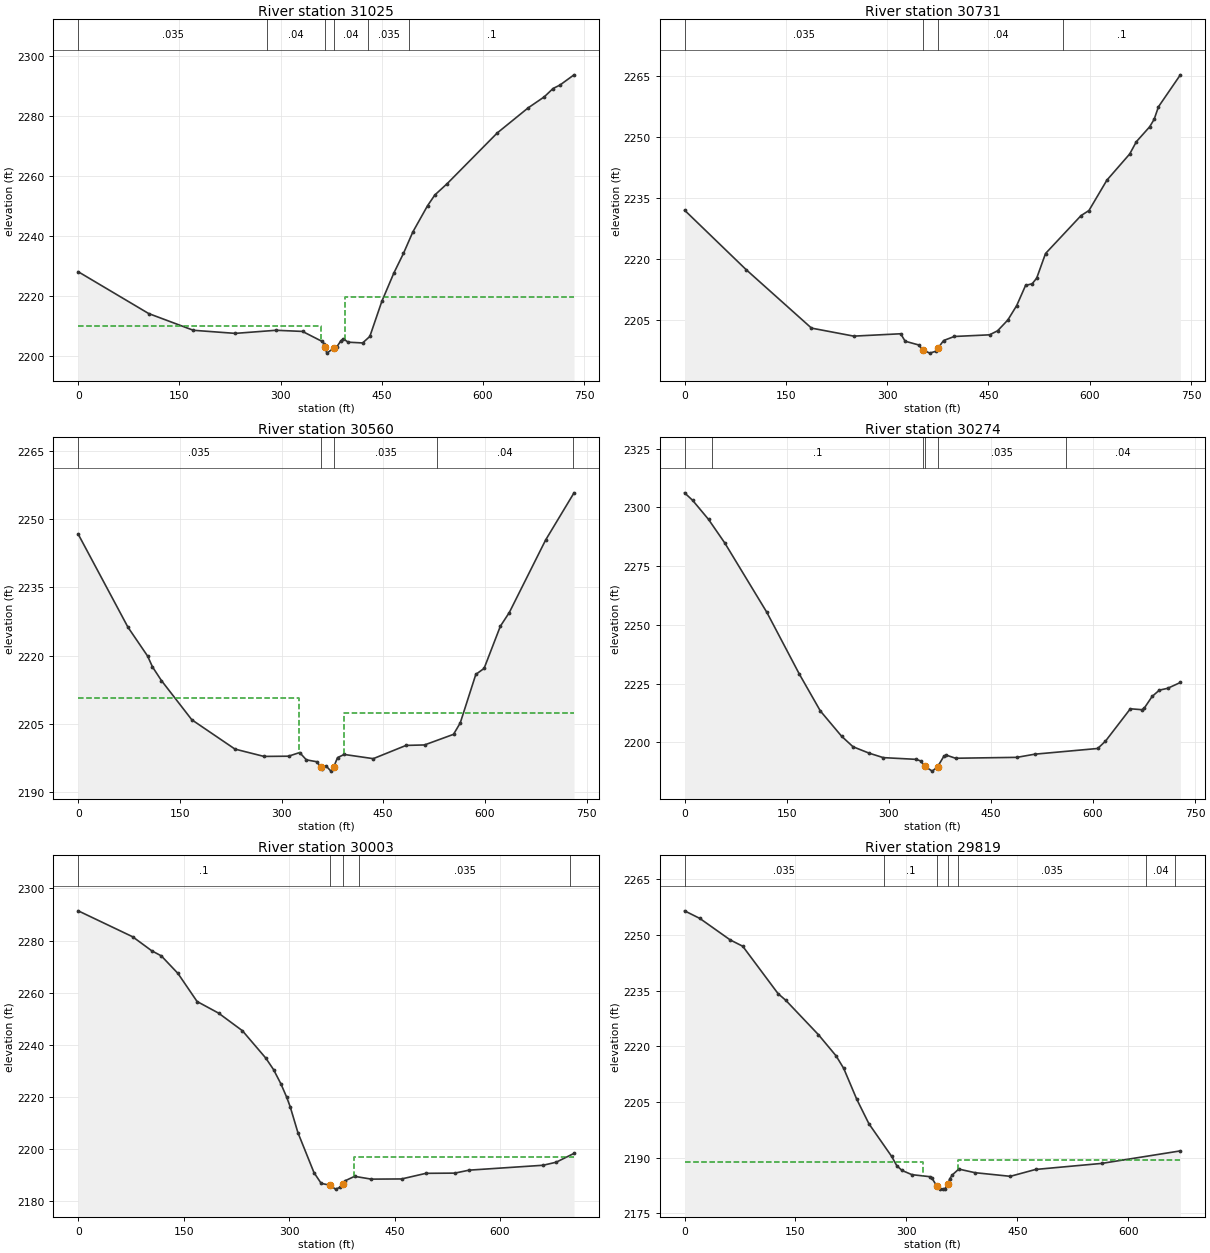
Type RM Length L Ch R = 1 ,31025   ,289.3,294.1,296.4
XS GIS Cut Line= 3
     2119501.866      203099.064      2119714.89      203602.837
     2119899.127       203640.26
#Sta/Elev= 30
       0 2228.13   104.6  2214.2   170.7 2208.65   232.8 2207.62   293.3 2208.65
   332.5 2208.27     361 2205.01   364.6 2204.16   365.9 2203.05   368.5 2201.05
   378.5 2202.62   383.5  2203.2   389.5 2205.19   393.1 2205.79   400.2 2204.69
   421.6 2204.44   432.3  2206.6   450.1 2218.28   467.9 2227.69   482.2 2234.25
   496.1 2241.38   517.8 2250.07   528.7 2253.67     547 2257.44   621.2  2274.3
   667.1 2282.66   690.8 2286.29   703.9 2289.08     714 2290.21     735 2293.63
#Mann= 6 ,-1 , 0
       0    .035       0     280     .04       0   365.9    .045       0
   378.5     .04       0     430    .035       0     490      .1       0
#XS Ineff= 2 , 0
          359.38 2210.02   394.8         2219.88
Permanent Ineff=
       F       F
Bank Sta=365.9,378.5
XS Rating Curve= 0 ,0
Exp/Cntr=0.3,0.1

Type RM Length L Ch R = 1 ,30731   ,170,170.9,171.1
XS GIS Cut Line= 3
     2119353.932      203192.429     2119412.226      203688.885
     2119408.754       203923.26
#Sta/Elev= 30
       0 2232.06    91.1 2217.45     188 2203.06   250.6 2201.09   320.1 2201.67
   326.7 2199.84   346.5 2198.93   352.82197.756     363 2196.91   372.9  2197.4
   375.72198.226   383.7 2200.01   399.4    2201   451.7 2201.41   463.6  2202.4
   478.7 2205.04   491.9  2208.6     505 2213.54   514.9 2213.98   521.5 2215.34
   534.6  2221.4   587.1 2230.71   598.9 2231.97   625.5 2239.44   659.3 2245.88
   669.1 2248.89   688.8 2252.55   695.4 2254.37   701.9 2257.49   734.3 2265.33
#Mann= 4 ,-1 , 0
       0    .035       0   352.8    .045       0   375.7     .04       0
  559.87      .1       0
Bank Sta=352.8,375.7
XS Rating Curve= 0 ,0
Exp/Cntr=0.3,0.1

Type RM Length L Ch R = 1 ,30560   ,289,286,282.6
XS GIS Cut Line= 2
      2119202.37      203220.588     2119256.029      203950.075
#Sta/Elev= 30
       0 2246.69    73.4 2226.25   102.4 2219.91   109.6 2217.53   122.8 2214.53
   167.6 2205.92   231.3 2199.48   274.1 2197.87   310.3 2197.92   326.7 2198.72
   336.6 2197.12   352.3 2196.69   357.52195.519   359.6 2195.06   366.2 2195.71
   372.8 2194.64   377.22195.646   382.6 2197.61   392.5  2198.3   435.3 2197.38
   483.7 2200.29   510.9 2200.39   553.7 2202.72   563.6 2205.22   586.6 2215.89
   598.8  2217.2   622.8 2226.47     636 2229.48   689.6 2245.41   731.5 2255.77
#Mann= 5 ,-1 , 0
       0    .035       0   357.5    .045       0   377.2    .035       0
     530     .04       0     730      .1       0
#XS Ineff= 2 , 0
          325.61 2210.75  392.54         2207.33
Permanent Ineff=
       F       F
Bank Sta=357.5,377.2
XS Rating Curve= 0 ,0
Exp/Cntr=0.3,0.1

Type RM Length L Ch R = 1 ,30274   ,270.3,271,271.3
XS GIS Cut Line= 2
     2118854.187      203312.589     2119062.526      204010.592
#Sta/Elev= 30
       0 2306.25    11.9 2303.05    35.2 2294.94    59.1 2284.89   120.8 2255.39
   168.7    2229   199.5 2213.33   230.7 2202.56   247.5 2198.07   271.4 2195.32
     292 2193.44   339.9 2192.71   346.8 2192.05   352.8 2189.77   363.9 2187.69
   371.8 2189.57     381 2194.06   384.4 2194.52   398.1 2193.18   488.3 2193.56
   514.5 2194.91     607 2197.34   618.4 2200.47   654.9 2214.25     672 2213.86
   675.4 2214.55   686.9  2219.5   697.5 2222.19   709.7 2222.97   728.4 2225.45
#Mann= 6 ,-1 , 0
       0    .035       0      40      .1       0     350    .035       0
   352.8    .045       0   371.8    .035       0     560     .04       0
Bank Sta=352.8,371.8
XS Rating Curve= 0 ,0
Exp/Cntr=0.3,0.1

Type RM Length L Ch R = 1 ,30003   ,184,184.3,183.8
XS GIS Cut Line= 2
2118600.10102581 203363.301380072118781.00887672204045.038334015
#Sta/Elev= 30
       0 2291.42    77.5 2281.45   104.6 2276.07   118.2 2274.12   141.9 2267.37
   169.1 2256.59   199.6 2252.14   233.6 2245.36   266.9 2234.83   277.9 2230.42
   288.4 2224.92   296.4 2219.93   301.5 2216.21   312.5 2206.25   335.4 2190.86
   345.6 2186.74   358.1 2186.02     366 2184.52   372.8 2185.23   376.9 2186.65
   379.6 2187.72   393.1 2189.43   416.9 2188.36     460 2188.43   494.7 2190.59
   535.7 2190.67   556.1 2191.81   661.4 2193.69   679.9 2194.86   705.3 2198.25
#Mann= 5 ,-1 , 0
       0      .1       0   358.1    .045       0   376.9      .1       0
     400    .035       0     700     .04       0
#XS Ineff= 2 , 0
                          391.86         2196.78
Permanent Ineff=
       F       F
Bank Sta=358.1,376.9
XS Rating Curve= 0 ,0
Exp/Cntr(USF)=0,0
Exp/Cntr=0.3,0.1

Type RM Length L Ch R = 1 ,29819   ,144.8,135.8,128.2
XS GIS Cut Line= 3
2118415.79375534203395.3179263362118549.63478559203860.227962703
2118696.80635458203975.271057442
#Sta/Elev= 30
       0  2256.5    20.7 2254.45    61.7 2248.67    78.7 2246.96   126.5 2234.19
   136.8 2232.42   181.1 2223.13     205 2217.42   215.3 2214.04     233  2205.7
   249.4 2199.13   280.2 2190.32     287 2187.86     294 2186.57   307.5 2185.43
   331.4 2184.89   334.8 2184.41   341.22182.369     345 2181.66   349.7 2181.53
   351.9 2181.58   356.22182.879   358.7 2184.31   362.1 2185.35   370.9 2186.93
   392.8 2185.96   440.6 2184.98   474.8 2186.83   564.2 2188.46   670.6 2191.83
#Mann= 7 ,-1 , 0
       0    .035       0     270      .1       0   341.2    .045       0
   356.2      .1       0     370    .035       0  623.79     .04       0
  663.79    .035       0
#XS Ineff= 2 , 0
          322.36 2188.96  369.46         2189.45
Permanent Ineff=
       F       F
Bank Sta=341.2,356.2
XS Rating Curve= 0 ,0
Exp/Cntr=0.5,0.3

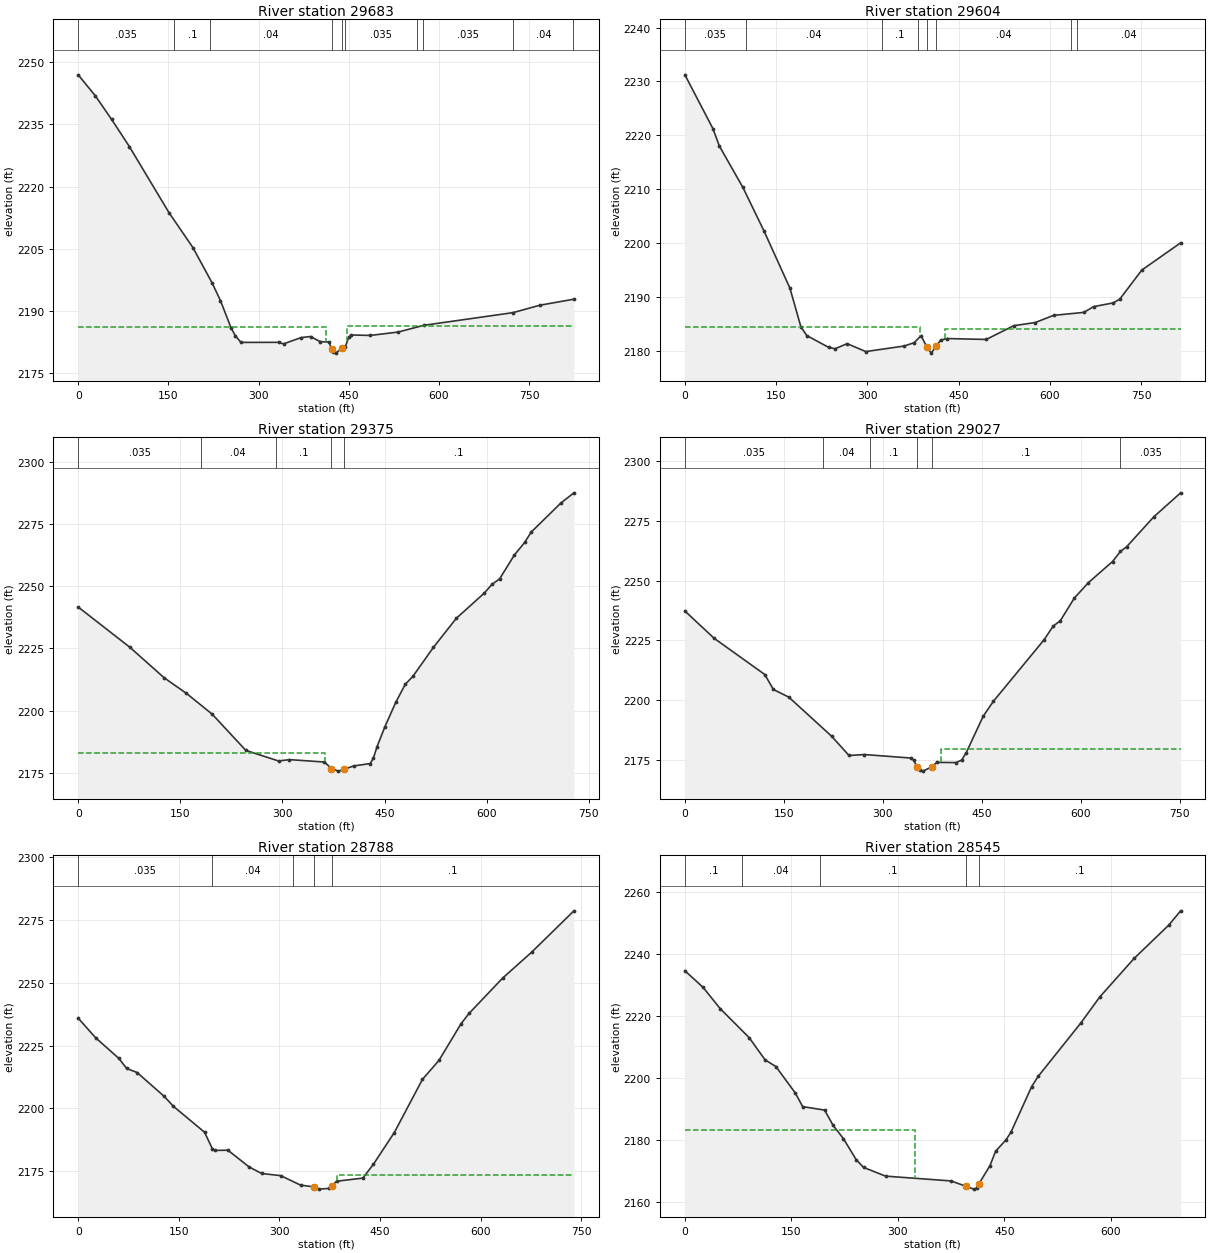
Type RM Length L Ch R = 1 ,29683   ,77.4,78.5,78.5
XS GIS Cut Line= 3
2118368.58566517203404.8383914572118265.25766517203669.045391457
2118686.64862742204008.016009439
#Sta/Elev= 30
       0 2246.89    28.7  2241.8    55.5 2236.17    85.1 2229.62   150.9 2213.73
   190.8 2205.29   222.5 2196.85   236.6 2192.53   254.2 2185.98   261.2  2184.1
   270.7 2182.46   333.5 2182.48   341.5 2182.11   370.7 2183.62   386.4 2183.88
   402.1 2182.66   417.3 2182.55   421.5 2180.77   423.1 2180.22   428.3 2179.88
   438.4 2181.03     444 2181.33   450.2 2183.77   454.5 2184.25   485.9 2184.14
   531.9 2184.95   574.9 2186.58   723.2 2189.63   767.6 2191.41   824.5 2192.87
#Mann= 10 ,-1 , 0
       0    .035       0     160      .1       0     220     .04       0
   421.5    .045       0   438.4     .04       0  443.69    .035       0
  563.69     .04       0  573.69    .035       0  723.69     .04       0
  823.69    .035       0
#XS Ineff= 2 , 0
          412.93 2186.28  447.36         2186.52
Permanent Ineff=
       F       F
Bank Sta=421.5,438.4
XS Rating Curve= 0 ,0
Exp/Cntr=0.5,0.3

Type RM Length L Ch R = 1 ,29604   ,210.7,229.3,246
XS GIS Cut Line= 3
     2118317.638      203457.664      2118214.31      203721.871
2118633.65097168204047.523179332
#Sta/Elev= 30
       0 2231.23      46 2221.25    56.6 2218.01    95.3 2210.31   129.9 2202.24
   172.6 2191.59   190.6 2184.41   200.2 2182.79   236.2 2180.59   246.8 2180.33
   266.6 2181.28   297.2 2179.81   360.4 2180.84   376.7 2181.46   388.1 2182.76
   397.62180.635   404.8 2179.52   412.92180.787   420.2 2181.94   430.9 2182.23
   495.1 2182.06   540.4 2184.62   575.6  2185.2   605.9 2186.54   655.6 2187.09
   671.6 2188.16   703.7 2188.85   714.4 2189.53   750.8 2194.95   814.6 2200.01
#Mann= 8 ,-1 , 0
       0    .035       0     100     .04       0  323.69      .1       0
  383.69     .04       0   397.6    .045       0   412.9     .04       0
  633.69    .035       0  643.69     .04       0
#XS Ineff= 2 , 0
          387.04 2184.33  427.65         2184.05
Permanent Ineff=
       F       F
Bank Sta=397.6,412.9
XS Rating Curve= 0 ,0
Exp/Cntr=0.5,0.3

Type RM Length L Ch R = 1 ,29375   ,344.2,348,348
XS GIS Cut Line= 3
     2118328.124      203398.7252118095.92513359203803.139133588
2117969.51979027204032.387850191
#Sta/Elev= 30
       0 2241.67    75.7 2225.52     126 2213.26     159 2206.93   196.8 2198.56
   246.2 2183.99   294.3 2179.72   310.3 2180.27   361.6  2179.3     3722176.694
   382.2 2175.64   389.7  2176.3   404.7 2177.73   428.9 2178.69   433.7 2180.97
   438.9 2185.46   450.5 2193.52   466.3 2203.26   480.4  2210.6   491.5 2213.76
   521.6  2225.4   555.3 2237.12   596.5  2247.3   607.8 2250.81     619 2253.02
   640.6  2262.6   655.7 2267.65   665.3 2271.83   708.9 2283.52   728.1 2287.63
#Mann= 5 ,-1 , 0
       0    .035       0     180     .04       0     290      .1       0
     372    .045       0   389.7      .1       0
#XS Ineff= 2 , 0
          362.21 2183.09
Permanent Ineff=
       F       F
Bank Sta=372,389.7
XS Rating Curve= 0 ,0
Exp/Cntr=0.3,0.1

Type RM Length L Ch R = 1 ,29027   ,233.2,239.2,240.7
XS GIS Cut Line= 2
     2118119.121        203229.3     2117656.781      203821.367
#Sta/Elev= 30
       0 2237.23    44.4 2225.78   121.1 2210.62   134.1 2204.35   157.5 2201.14
   222.4 2184.76   248.7  2176.7     272  2177.1   342.1 2175.64   346.8 2174.71
   351.52172.056   355.7 2170.45   360.7 2170.15     3742171.926   381.6 2173.82
   410.7 2173.73   419.3 2174.74   426.3 2177.87     452 2193.14   467.6 2199.45
   543.9 2225.05   558.2 2230.93   568.9 2233.17   590.2 2242.67   611.5 2249.13
     648 2257.96     660 2262.19   669.4 2264.15   710.4 2276.65   751.2 2286.74
#Mann= 6 ,-1 , 0
       0    .035       0     210     .04       0     280      .1       0
   351.5    .045       0     374      .1       0     660    .035       0
#XS Ineff= 2 , 0
                          387.36         2179.22
Permanent Ineff=
       F       F
Bank Sta=351.5,374
XS Rating Curve= 0 ,0
Exp/Cntr=0.3,0.1

Type RM Length L Ch R = 1 ,28788   ,216.8,243,238
XS GIS Cut Line= 3
     2118063.227      203168.515     2117756.576      203360.171
     2117436.462      203560.259
#Sta/Elev= 30
       0 2235.91    25.9 2228.12    60.7 2219.85    72.3 2215.86    87.8 2214.26
   128.3 2204.74   141.9  2200.8   188.4 2190.46     200 2183.88   203.8 2183.22
   223.2 2183.31     255  2176.6   273.5 2174.04   302.1 2173.16   331.5  2169.4
   351.82168.685   359.2  2167.8   374.1 2168.09   377.9 2169.05   385.4 2170.95
   424.4  2172.2   440.2 2177.74   471.1 2190.25   513.3 2211.55   537.8 2219.05
   570.7 2233.66     583 2237.88     633 2251.92   675.9 2262.16   739.1 2278.67
#Mann= 5 ,-1 , 0
       0    .035       0     200     .04       0     320      .1       0
   351.8    .045       0   377.9      .1       0
#XS Ineff= 2 , 0
                          386.39         2173.57
Permanent Ineff=
       F       F
Bank Sta=351.8,377.9
XS Rating Curve= 0 ,0
Exp/Cntr=0.3,0.1

Type RM Length L Ch R = 1 ,28545   ,345.2,322.9,314.5
XS GIS Cut Line= 3
     2117962.575       203016.03     2117474.726      203291.315
     2117393.129      203402.426
#Sta/Elev= 30
       0 2234.61    25.7 2229.22    49.8 2222.34    90.4 2213.02     113 2205.79
   128.1 2203.67   155.7 2195.03   165.8  2190.7   196.7 2189.59   208.7 2184.65
   223.2 2180.37   241.1  2173.6   251.5 2171.07   282.6 2168.25   374.7  2166.7
   396.4 2164.91   406.9 2164.05   410.6 2164.39   413.4 2165.56   429.5  2171.6
   437.5 2176.31     452 2179.92   459.2  2182.5   488.1 2197.11   497.3 2200.45
   557.6 2217.76     584  2226.1   632.4 2238.57   681.3 2249.36     698 2253.97
#Mann= 5 ,-1 , 0
       0      .1       0      80     .04       0     190      .1       0
   396.4    .045       0   413.4      .1       0
#XS Ineff= 2 , 0
          323.69 2183.21
Permanent Ineff=
       F       F
Bank Sta=396.4,413.4
XS Rating Curve= 0 ,0
Exp/Cntr=0.3,0.1

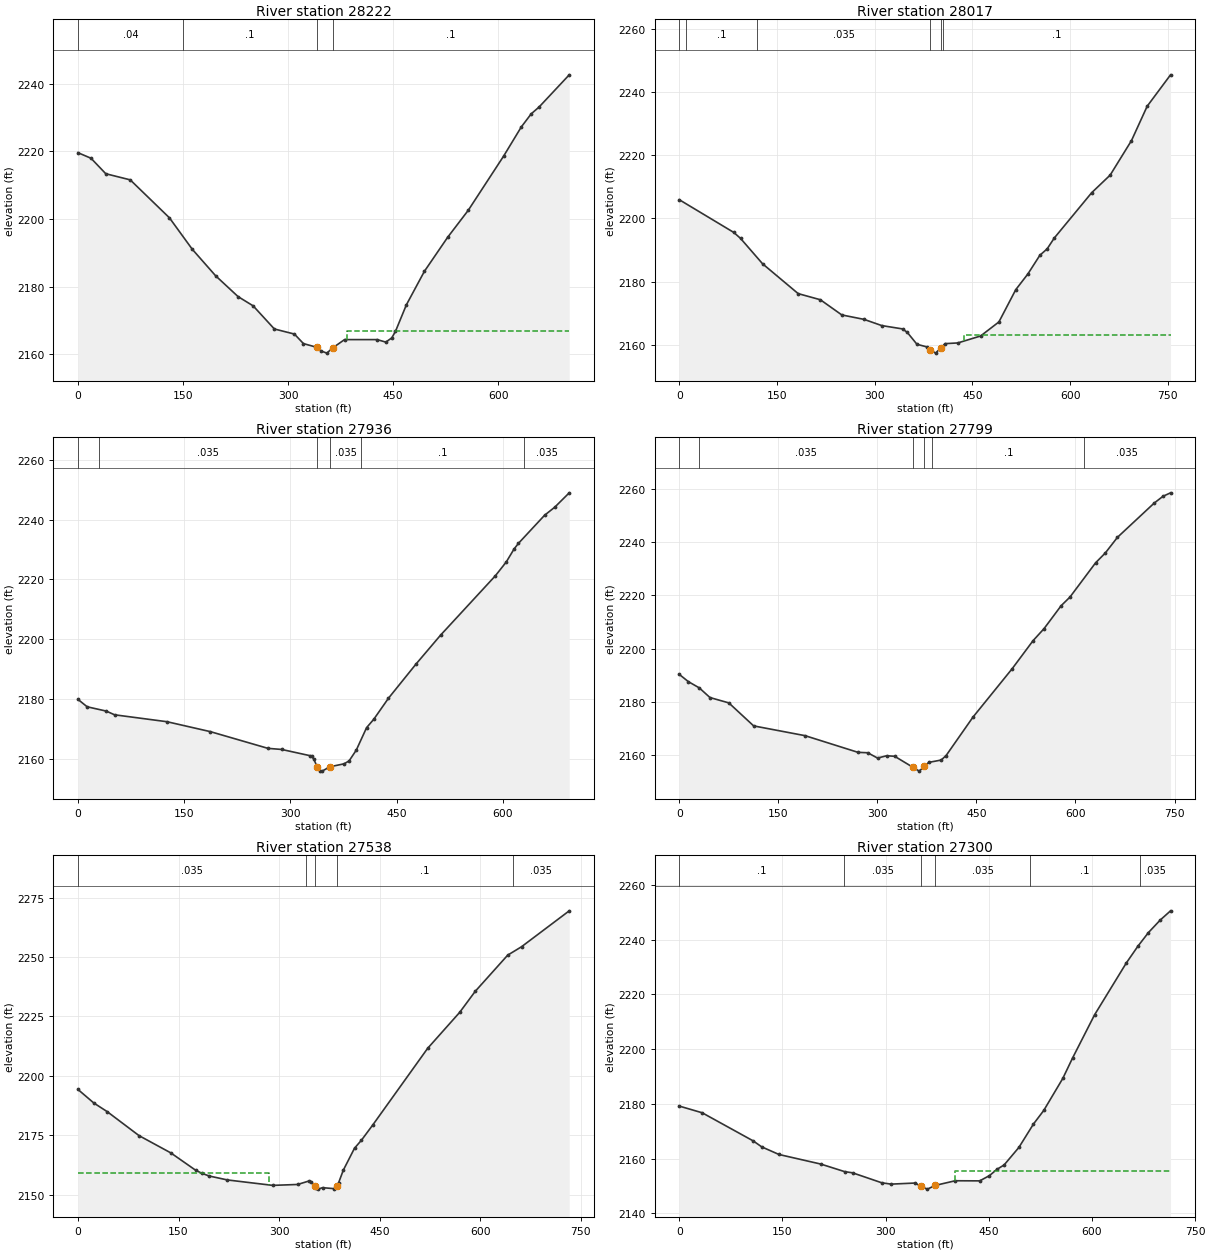
Type RM Length L Ch R = 1 ,28222   ,207.3,205.2,201.4
XS GIS Cut Line= 2
     2117695.212      202685.412     2117255.976      203232.287
#Sta/Elev= 30
       0 2219.58    18.6 2217.94    39.7 2213.36    74.6 2211.55   130.6 2200.32
   163.2 2191.02   196.5 2183.19   228.6 2177.02   250.1 2174.29   280.4 2167.45
     309 2165.95   321.9 2163.13   341.62161.995   346.9 2160.97   355.3 2160.31
   363.82161.875   380.6 2164.31   427.1 2164.31   439.5 2163.57     448 2164.81
   453.3 2166.74   468.9  2174.6   494.6  2184.5   527.8 2194.56   557.3 2202.57
   607.8  2218.6     633 2227.21   647.1 2231.07   658.3 2233.08   701.4 2242.61
#Mann= 4 ,-1 , 0
       0     .04       0     150      .1       0   341.6    .045       0
   363.8      .1       0
#XS Ineff= 2 , 0
                          383.92            2167
Permanent Ineff=
       F       F
Bank Sta=341.6,363.8
XS Rating Curve= 0 ,0
Exp/Cntr=0.3,0.1

Type RM Length L Ch R = 1 ,28017   ,78.8,80.5,81.1
XS GIS Cut Line= 3
     2117610.143      202652.426     2117374.032      202718.398
     2117138.897      203169.929
#Sta/Elev= 30
       0  2205.9    83.7 2195.55      94 2193.68   127.9 2185.64   182.5 2176.22
   216.6 2174.28   249.5 2169.48   283.6 2168.08   310.8 2166.12   342.8 2165.06
   350.1 2163.94   364.9  2160.2   379.7  2159.4   385.12158.445   393.5 2157.41
   401.82159.168   408.1 2160.41   427.6 2160.63   462.6 2162.83   490.7 2167.27
   516.6 2177.48   535.1 2182.41   553.6 2188.35   564.7 2190.35   575.8 2193.82
   633.1 2208.11   661.5 2213.68   694.2 2224.58   718.3 2235.44   754.2 2245.37
#Mann= 6 ,-1 , 0
       0     .04       0      10      .1       0     120    .035       0
   385.1    .045       0   401.8    .035       0  405.15      .1       0
#XS Ineff= 2 , 0
                          436.76         2163.01
Permanent Ineff=
       F       F
Bank Sta=385.1,401.8
XS Rating Curve= 0 ,0
Exp/Cntr=0.3,0.1

Type RM Length L Ch R = 1 ,27936   ,138.5,137.7,135.9
XS GIS Cut Line= 2
2117419.43926199202521.6038000592117051.91068068203110.030388799
#Sta/Elev= 30
       0  2179.8      13 2177.32      40 2175.88    51.7 2174.64   125.8 2172.32
   187.1 2168.99   268.3  2163.4   287.7 2163.03   328.2 2160.92   330.2 2160.77
   332.9 2159.82     338 2157.17   341.8 2155.92   344.8 2155.77   355.72157.221
   375.8 2158.22   382.9  2159.2     393 2162.79   407.6 2170.33   417.8 2173.16
   438.5 2180.19   477.2 2191.58     512  2201.3   589.4 2221.19   604.9 2225.85
   615.9 2230.19   622.1 2232.08     659 2241.49   673.4  2244.2   693.8    2249
#Mann= 6 ,-1 , 0
       0      .1       0      30    .035       0     338    .045       0
   355.7    .035       0     400      .1       0     630    .035       0
Bank Sta=338,355.7
XS Rating Curve= 0 ,0
Exp/Cntr(USF)=0,0
Exp/Cntr=0.3,0.1

Type RM Length L Ch R = 1 ,27799   ,262,260.7,258.3
XS GIS Cut Line= 3
     2117335.907      202447.599     2117172.643      202654.162
     2116948.618       203079.53
#Sta/Elev= 30
       0 2190.35    13.8 2187.62    30.2  2185.3    46.5 2181.65      75 2179.65
   112.6 2171.01   190.5 2167.34   270.6 2161.08   285.4 2160.92   300.2 2158.93
   314.2  2159.8   326.2 2159.59   354.22155.407   363.3 2154.02   371.22155.802
   377.9 2157.31   396.6 2158.18   404.1 2159.88   444.9 2174.35   504.2 2192.51
   535.8 2203.03   552.4 2207.54   578.3 2216.15   591.7 2219.41   630.5 2232.27
   645.1 2235.93   663.6 2241.84   719.2 2254.69   732.5 2257.24     744 2258.55
#Mann= 6 ,-1 , 0
       0      .1       0      30    .035       0   354.2    .045       0
   371.2    .035       0  383.29      .1       0  613.29    .035       0
Bank Sta=354.2,371.2
XS Rating Curve= 0 ,0
Exp/Cntr=0.3,0.1

Type RM Length L Ch R = 1 ,27538   ,234.1,238.3,241.1
XS GIS Cut Line= 3
      2116969.51      202332.681     2116880.854      202691.311
      2116781.98      203041.001
#Sta/Elev= 30
       0 2194.25    23.5 2188.58    43.8 2184.87    91.1 2174.81   138.4 2167.56
   175.6 2160.23     185 2158.93   195.7 2157.82   222.8 2156.16   290.5 2153.87
   327.7 2154.25   344.6 2155.72   347.9 2155.42   353.12153.563   354.7 2152.81
   358.1 2152.29   364.8  2152.9   381.8  2152.5   385.82153.553   388.7 2154.91
   395.8 2160.28   412.5 2169.52   422.8 2172.87   439.8 2179.33   521.6 2211.57
   569.4 2226.72   592.5 2235.54     641  2250.8   661.6 2254.33   732.8 2269.46
#Mann= 5 ,-1 , 0
       0    .035       0     340      .1       0   353.1    .045       0
   385.8      .1       0  649.43    .035       0
#XS Ineff= 2 , 0
          284.66 2158.92
Permanent Ineff=
       F       F
Bank Sta=353.1,385.8
XS Rating Curve= 0 ,0
Exp/Cntr=0.3,0.1

Type RM Length L Ch R = 1 ,27300   ,258.6,261.7,262.2
XS GIS Cut Line= 2
      2116813.96      202244.2752116539.33873282202903.625477735
#Sta/Elev= 30
       0 2179.19    33.3 2176.74   107.4 2166.47   119.9 2164.27     145 2161.49
   205.8 2157.99   240.4 2155.23     252 2154.79   294.6 2151.13   308.1 2150.66
   343.2 2151.06   351.1 2149.81   360.8 2148.83     372 2150.18   401.2 2151.89
   436.8 2151.85     451 2153.77   461.7 2156.03   472.3 2157.67   493.8 2164.08
     515 2172.64   529.9 2177.58   557.6 2189.29   571.8 2196.75   603.8 2212.54
     650 2231.52   666.9 2237.66   682.1 2242.61   699.5 2247.25   714.3 2250.57
#Mann= 6 ,-1 , 0
       0      .1       0     240    .035       0   351.1    .045       0
     372    .035       0     510      .1       0     670    .035       0
#XS Ineff= 2 , 0
                          400.69         2155.62
Permanent Ineff=
       F       F
Bank Sta=351.1,372
XS Rating Curve= 0 ,0
Exp/Cntr=0.3,0.1

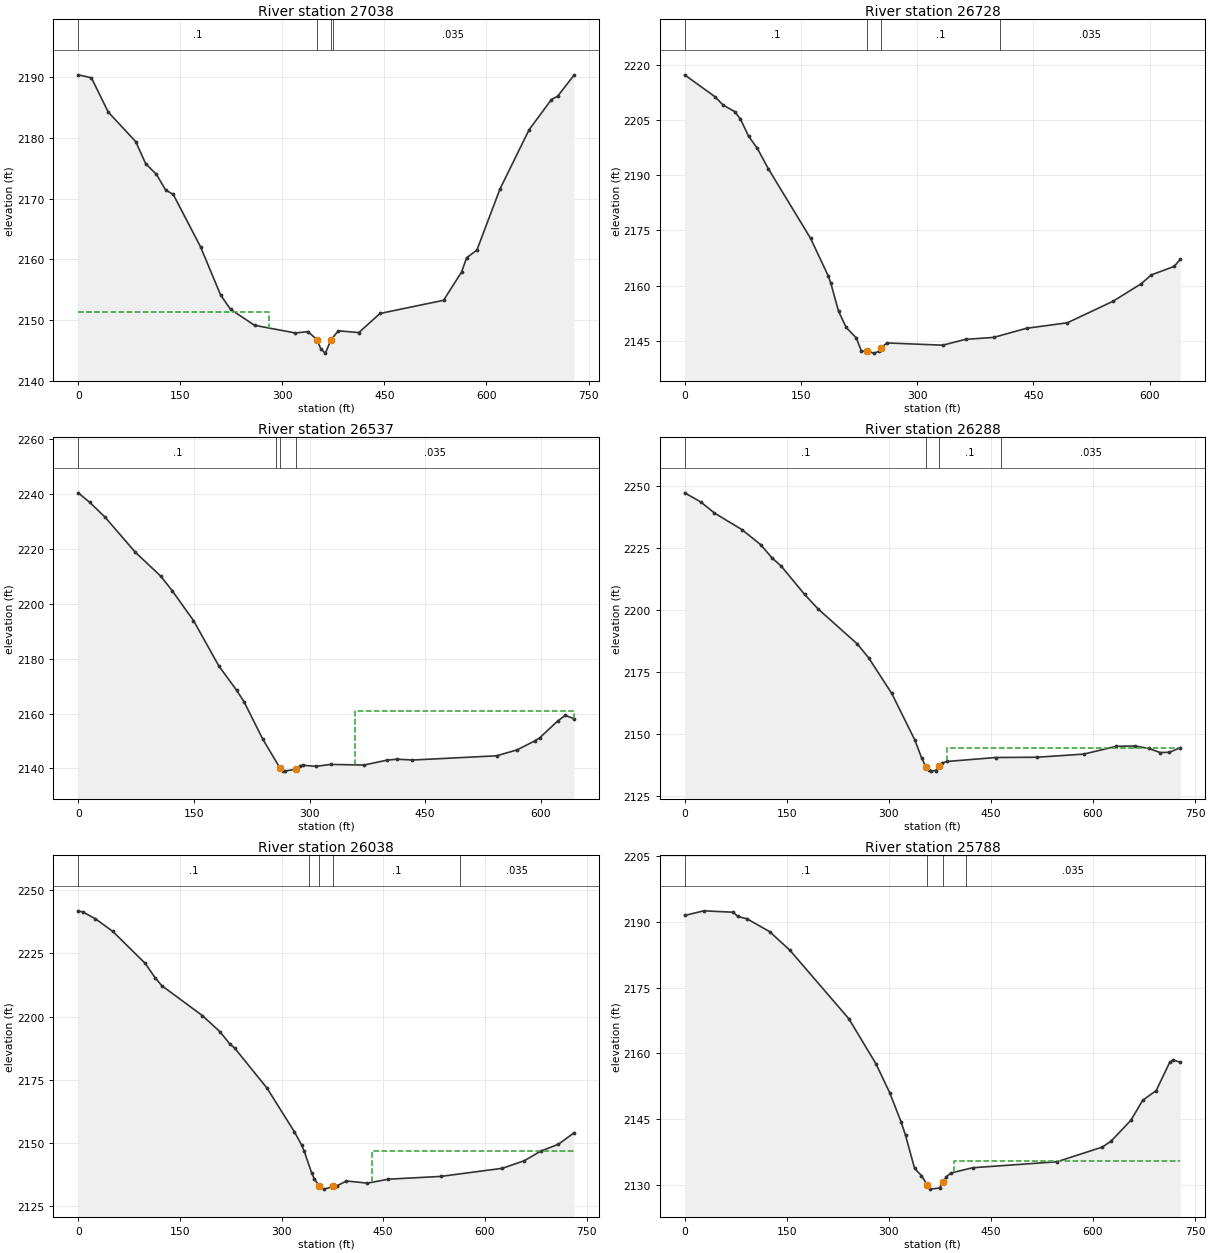
Type RM Length L Ch R = 1 ,27038   ,314.5,309.8,302.7
XS GIS Cut Line= 3
     2116610.492      202138.784     2116447.754      202464.257
     2116267.701      202781.317
#Sta/Elev= 30
       0 2190.43    19.4 2189.94    44.2 2184.28    84.6 2179.41    99.2 2175.77
   114.8 2174.05   128.6 2171.42   139.6 2170.73   179.9 2162.05   209.3 2154.13
   223.9 2151.77   259.1 2149.14   319.3 2147.87   337.7  2148.1   350.82146.772
   356.9 2145.17   363.3 2144.55   371.4 2146.74   382.2 2148.23   412.3 2147.94
   443.6 2151.09   536.9 2153.26   563.3 2157.91   570.8 2160.27   585.9 2161.54
   619.9 2171.63   662.6 2181.38   695.3 2186.34   704.6 2186.91   728.5 2190.36
#Mann= 4 ,-1 , 0
       0      .1       0   350.8    .045       0   371.4      .1       0
  373.89    .035       0
#XS Ineff= 2 , 0
          280.35  2151.4
Permanent Ineff=
       F       F
Bank Sta=350.8,371.4
XS Rating Curve= 0 ,0
Exp/Cntr=0.3,0.1

Type RM Length L Ch R = 1 ,26728   ,188.3,191,191.8
XS GIS Cut Line= 3
2116261.60368554202071.1855816372116206.18304177202186.041489821
     2116198.644      202698.171
#Sta/Elev= 30
       0 2217.27    38.8 2211.37    49.6 2209.07    64.4 2207.29    71.8 2205.34
    82.5  2200.6    93.9 2197.25     108 2191.74   162.5 2172.83   185.4 2162.58
   188.7 2160.58   198.6 2153.03   208.4 2148.62   221.5 2145.75   228.1 2142.17
   235.72142.125   244.5 2141.62   251.1 2142.13     254 2143.13   260.9 2144.39
   333.1 2143.78   362.6 2145.37   398.7 2145.89   441.4 2148.38   493.9 2149.87
   552.9 2155.73     589 2160.46   602.1 2162.87   631.7 2165.19   639.7 2167.17
#Mann= 4 ,-1 , 0
       0      .1       0   235.7    .045       0     254      .1       0
  407.53    .035       0
Bank Sta=235.7,254
XS Rating Curve= 0 ,0
Exp/Cntr=0.3,0.1

Type RM Length L Ch R = 1 ,26537   ,247.1,249.2,251.2
XS GIS Cut Line= 3
     2116028.288      202015.662     2116028.288      202192.528
     2115973.973      202655.241
#Sta/Elev= 30
       0 2240.35      15 2236.86    34.7 2231.53    74.1 2218.71   106.9 2210.05
   121.9 2204.72   149.5 2193.85   182.4  2177.3   205.5 2168.43   215.2  2164.2
   239.3 2150.68   261.62140.187     265 2139.13   268.3 2139.02   282.82139.789
   288.1 2141.03   291.4 2141.18   307.9 2140.75   327.5 2141.46   370.7 2141.24
   400.4 2143.02   413.5 2143.37   433.4 2143.06   542.4  2144.6   568.9 2146.74
     592 2150.02   598.6 2151.19   621.7 2157.27   631.6 2159.32   642.8  2158.1
#Mann= 4 ,-1 , 0
       0      .1       0  256.87    .035       0   261.6    .045       0
   282.8    .035       0
#XS Ineff= 2 , 0
                          358.48          2160.8
Permanent Ineff=
       F       F
Bank Sta=261.6,282.8
XS Rating Curve= 0 ,0
Exp/Cntr=0.3,0.1

Type RM Length L Ch R = 1 ,26288   ,246.9,250,252.8
XS GIS Cut Line= 3
     2115860.418      201919.278     2115771.293      202272.855
     2115674.522      202623.639
#Sta/Elev= 30
       0 2247.24    23.5  2243.6    43.8 2239.11    84.4 2232.37   111.5 2226.39
   128.4 2221.02     142 2217.67   176.2  2206.3   196.1 2200.42   253.6 2186.33
   270.5 2180.67   304.4 2166.32   338.4 2147.49   348.3 2140.31   354.92136.548
   358.5 2135.32   361.9    2135   368.7 2135.25   374.52136.916   378.9 2138.32
   385.7  2138.9   457.2 2140.49   518.4 2140.61   586.5 2141.87   634.1 2144.99
   661.5 2145.17   681.8 2144.16   698.7  2142.5   712.4  2142.6   728.5 2144.49
#Mann= 4 ,-1 , 0
       0      .1       0   354.9    .045       0   374.5      .1       0
  464.64    .035       0
#XS Ineff= 2 , 0
                           385.6         2144.37
Permanent Ineff=
       F       F
Bank Sta=354.9,374.5
XS Rating Curve= 0 ,0
Exp/Cntr=0.3,0.1

Type RM Length L Ch R = 1 ,26038   ,253.6,250,243.9
XS GIS Cut Line= 3
     2115700.398      201870.102     2115537.958      202195.191
     2115377.109      202526.161
#Sta/Elev= 30
       0 2241.76     7.1 2241.27    25.5  2238.6    51.1 2233.61    98.9 2220.99
   113.5 2215.31   123.3 2212.21   183.2 2200.37   208.9 2194.06   223.6  2189.2
     231 2187.49   278.5 2171.74   318.9  2154.5   329.9  2149.1   333.6 2146.68
   344.6 2138.05   348.3 2135.92   355.92132.853   362.9  2131.8   376.42132.869
   381.1 2132.99   395.7 2135.02   426.8 2134.17   457.7 2135.73   534.8 2136.82
   625.7 2140.03   658.4 2143.04   682.1 2146.78   708.5 2149.53   731.4 2154.02
#Mann= 5 ,-1 , 0
       0      .1       0     340    .035       0   355.9    .045       0
   376.4      .1       0  563.41    .035       0
#XS Ineff= 2 , 0
                          433.58         2146.91
Permanent Ineff=
       F       F
Bank Sta=355.9,376.4
XS Rating Curve= 0 ,0
Exp/Cntr=0.3,0.1

Type RM Length L Ch R = 1 ,25788   ,229.5,228.9,226.7
XS GIS Cut Line= 3
     2115361.529      201763.321      2115299.78      202121.796
      2115245.89      202482.448
#Sta/Elev= 30
       0 2191.47    28.3 2192.52    71.6  2192.2    78.2 2191.23    91.5 2190.71
   124.8 2187.78   154.8 2183.51   241.3  2167.9   281.3 2157.58   301.3 2151.03
   317.9 2144.44   324.6 2141.31   337.9 2133.77   347.9 2132.13   356.32130.064
   361.2 2129.04   374.5  2129.3     380 2130.63   384.4 2131.87   391.5 2132.73
   423.2 2133.92     547 2135.28   613.7 2138.63   626.6 2139.99   655.7 2144.74
     673  2149.3   692.9 2151.52   712.8 2157.99   717.6 2158.52   728.4 2157.97
#Mann= 4 ,-1 , 0
       0      .1       0   356.3    .045       0     380      .1       0
  413.75    .035       0
#XS Ineff= 2 , 0
                          395.08         2135.39
Permanent Ineff=
       F       F
Bank Sta=356.3,380
XS Rating Curve= 0 ,0
Exp/Cntr=0.3,0.1

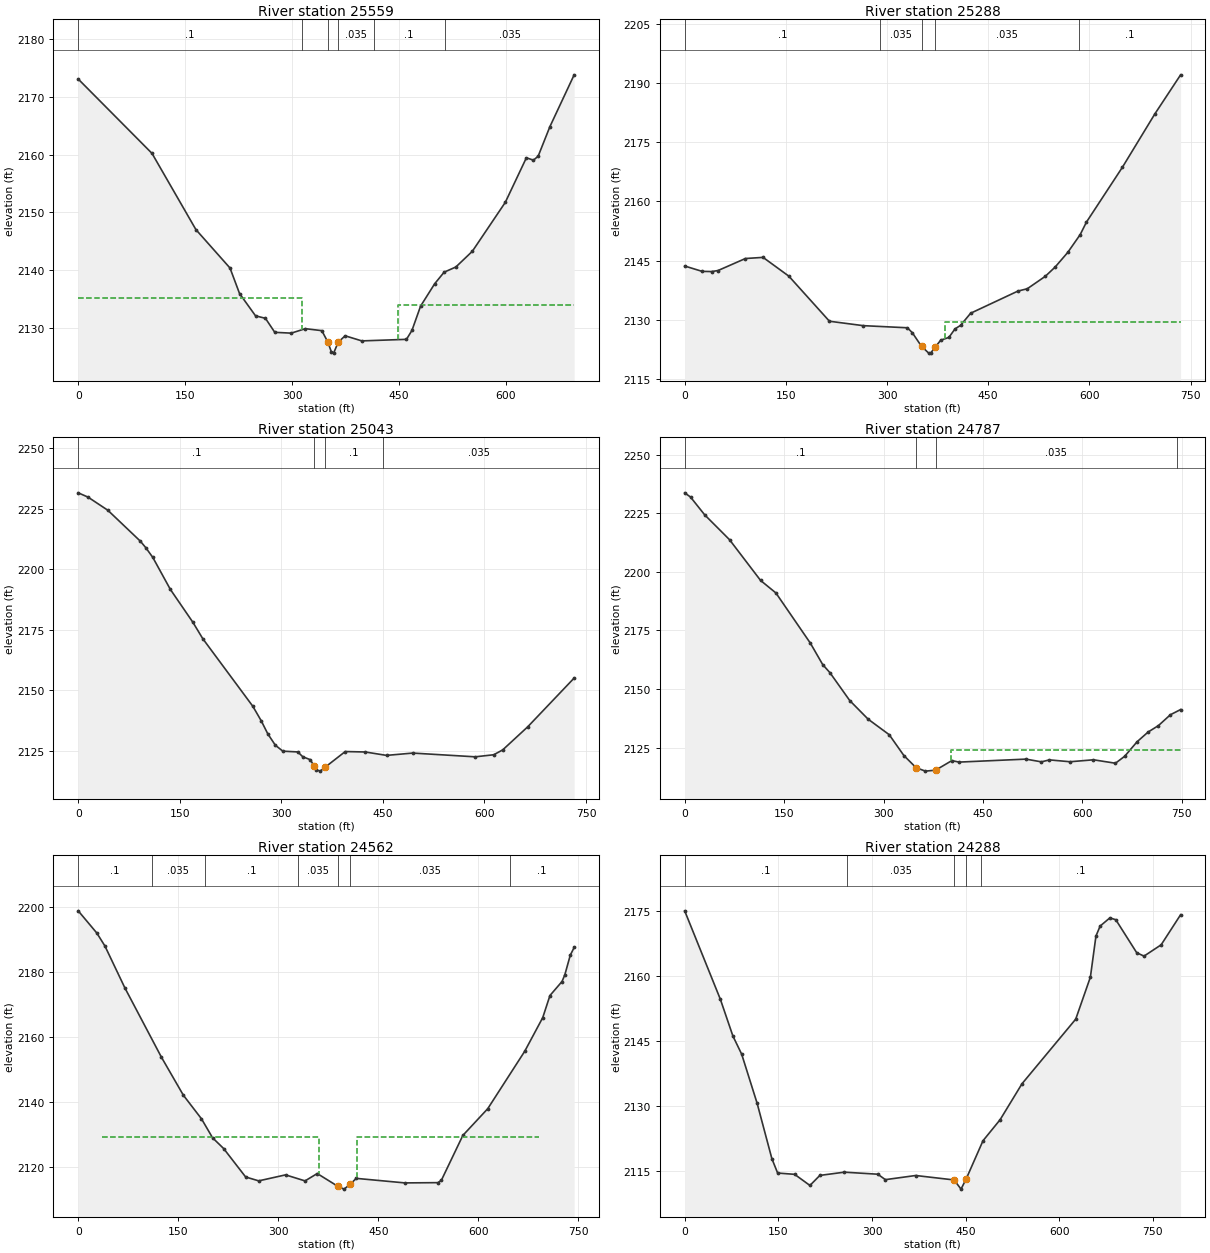
Type RM Length L Ch R = 1 ,25559   ,260.1,271.1,273.4
XS GIS Cut Line= 3
     2115276.335       201897.392115090.20239101201952.847629235
2115039.12463819202451.593359551
#Sta/Elev= 30
       0 2173.03   103.5  2160.2   165.1 2147.04   212.9 2140.41   226.3    2136
   248.7 2132.16   262.6 2131.73   275.7 2129.31   298.8 2129.17   318.6 2129.94
   341.7  2129.6   350.2 2127.61   354.9 2125.99   358.2 2125.72   364.8 2127.63
   374.4 2128.71   397.8 2127.83   460.4  2128.1   468.1 2129.64   480.2 2133.83
     500  2137.7   513.2 2139.69   529.7 2140.59   552.8  2143.3     599 2151.74
   628.6 2159.44   638.5 2159.03   645.1 2159.71   661.6 2164.82   695.6 2173.76
#Mann= 6 ,-1 , 0
       0      .1       0  314.22    .035       0   350.2    .045       0
   364.8    .035       0  414.22      .1       0  514.22    .035       0
#XS Ineff= 2 , 0
          313.22  2135.2  448.79          2134.1
Permanent Ineff=
       F       F
Bank Sta=350.2,364.8
XS Rating Curve= 0 ,0
Exp/Cntr=0.3,0.1

Type RM Length L Ch R = 1 ,25288   ,244.5,244.7,244.9
XS GIS Cut Line= 3
     2115036.114      201729.795     2114845.238      202039.978
     2114675.094      202369.682
#Sta/Elev= 30
       0 2143.63    25.9 2142.27    39.9 2142.22    49.4 2142.48      90 2145.53
   116.2 2145.82   154.4 2141.06   214.6 2129.62   264.7  2128.5   330.2 2127.96
   337.5  2126.7   351.22123.229   361.8 2121.53   364.8 2121.57   371.72123.142
   379.6 2124.81   391.7 2125.52   400.7 2127.67   409.1 2128.59   423.9 2131.65
     494 2137.27   507.9 2137.86   534.7 2141.03   549.1 2143.35   567.9 2147.08
   586.3 2151.59   595.6 2154.77     649 2168.71   697.1 2182.24   735.2 2192.13
#Mann= 5 ,-1 , 0
       0      .1       0     290    .035       0   351.2    .045       0
   371.7    .035       0  584.21      .1       0
#XS Ineff= 2 , 0
                          385.23          2129.4
Permanent Ineff=
       F       F
Bank Sta=351.2,371.7
XS Rating Curve= 0 ,0
Exp/Cntr=0.3,0.1

Type RM Length L Ch R = 1 ,25043   ,255.7,255.8,253.1
XS GIS Cut Line= 2
     2114829.734      201578.399        2114494.      202229.421
#Sta/Elev= 30
       0 2231.65    14.5 2229.87    43.8 2224.43    91.8 2211.64    99.8 2208.96
   110.2 2204.91   136.1 2191.69   169.3 2178.12     184  2171.3   257.9 2143.34
   270.3 2137.34     280 2131.94   291.1 2127.25   302.2 2124.77   324.3 2124.45
   331.7 2122.45   342.8 2121.24   348.7 2118.45   351.5 2117.09   357.5 2116.51
   364.9 2118.17   394.4 2124.61     424 2124.43   455.4 2123.02   494.1 2123.98
   586.4 2122.43   613.7 2123.28     627  2125.3   663.9 2134.84   732.5 2155.02
#Mann= 4 ,-1 , 0
       0      .1       0   348.7    .045       0   364.9      .1       0
     450    .035       0
Bank Sta=348.7,364.9
XS Rating Curve= 0 ,0
Exp/Cntr=0.3,0.1

Type RM Length L Ch R = 1 ,24787   ,227.4,225.6,222.5
XS GIS Cut Line= 3
     2114595.786      201447.508     2114399.599      201877.858
     2114248.774      202107.893
#Sta/Elev= 30
       0  2233.7     8.8  2231.9    30.1 2224.34    67.6 2213.73   114.5 2196.34
   137.6 2191.01   189.6 2169.59   208.2 2160.46   219.1 2157.01     249 2145.12
   276.7 2137.19   308.5 2130.57   330.6 2121.69     3492116.511     363 2115.04
   378.42115.437   402.9 2119.52   413.8 2118.89   514.6 2120.16     538    2119
   550.2 2119.83   581.2 2119.04   616.6 2119.87   649.7 2118.41   663.6 2121.37
   682.4 2127.58   698.9 2131.69   714.6 2134.47   732.6 2139.08     748  2141.3
#Mann= 4 ,-1 , 0
       0      .1       0     349    .045       0   378.4    .035       0
  742.96      .1       0
#XS Ineff= 2 , 0
                          401.78         2124.17
Permanent Ineff=
       F       F
Bank Sta=349,378.4
XS Rating Curve= 0 ,0
Exp/Cntr=0.3,0.1

Type RM Length L Ch R = 1 ,24562   ,266.7,273.5,272.1
XS GIS Cut Line= 3
2114400.17115731 201416.577359562114146.82839558201935.227527598
     2114014.399      202036.278
#Sta/Elev= 30
       0 2198.95    27.9  2192.1    40.1 2188.08      70 2175.16   124.8 2153.78
   157.7 2142.05   184.9 2134.76   201.5 2128.91   218.1  2125.6   251.1 2116.82
   270.7 2115.62     311 2117.47   340.2 2115.61   358.5 2117.88   389.52113.925
   398.7 2113.07   408.12114.591   416.9 2116.39   489.9 2114.99   539.6 2115.07
   544.7 2115.82   576.9 2129.65   614.2 2137.89   669.7 2155.62   696.7    2166
   707.5 2172.81   725.6 2177.14   729.8 2179.19     738 2185.27   743.8 2187.64
#Mann= 7 ,-1 , 0
       0      .1       0     110    .035       0     190      .1       0
     330    .035       0   389.5    .045       0   408.1    .035       0
  647.22      .1       0
#XS Ineff= 2 ,-1
   35.85   361.52129.031  417.91  690.632129.146
Permanent Ineff=
       F       F
Bank Sta=389.5,408.1
XS Rating Curve= 0 ,0
Exp/Cntr=0.3,0.1

Type RM Length L Ch R = 1 ,24288   ,280.5,287.1,286
XS GIS Cut Line= 3
     2114231.344      201375.813     2113972.176       201737.01
     2113782.156      202030.679
#Sta/Elev= 30
       0 2175.07    57.2  2154.6    77.2 2146.14    91.3 2141.92     116 2130.59
   139.7 2117.75   148.9 2114.45   176.1 2114.15   200.6 2111.58   216.5  2113.9
   255.6 2114.65   309.3 2114.18   321.4 2112.92     370 2113.88   431.52112.851
   442.6 2110.73   451.12113.168   477.8 2121.92   505.2 2126.78   540.3  2135.1
   626.3 2150.03   649.8 2159.75   658.7 2169.24   665.4 2171.55     681 2173.44
   690.5 2173.01     724 2165.38   735.7  2164.6   763.1 2167.21   794.3 2174.17
#Mann= 5 ,-1 , 0
       0      .1       0     260    .035       0   431.5    .045       0
   451.1    .035       0  474.56      .1       0
Bank Sta=431.5,451.1
XS Rating Curve= 0 ,0
Exp/Cntr=0.3,0.1