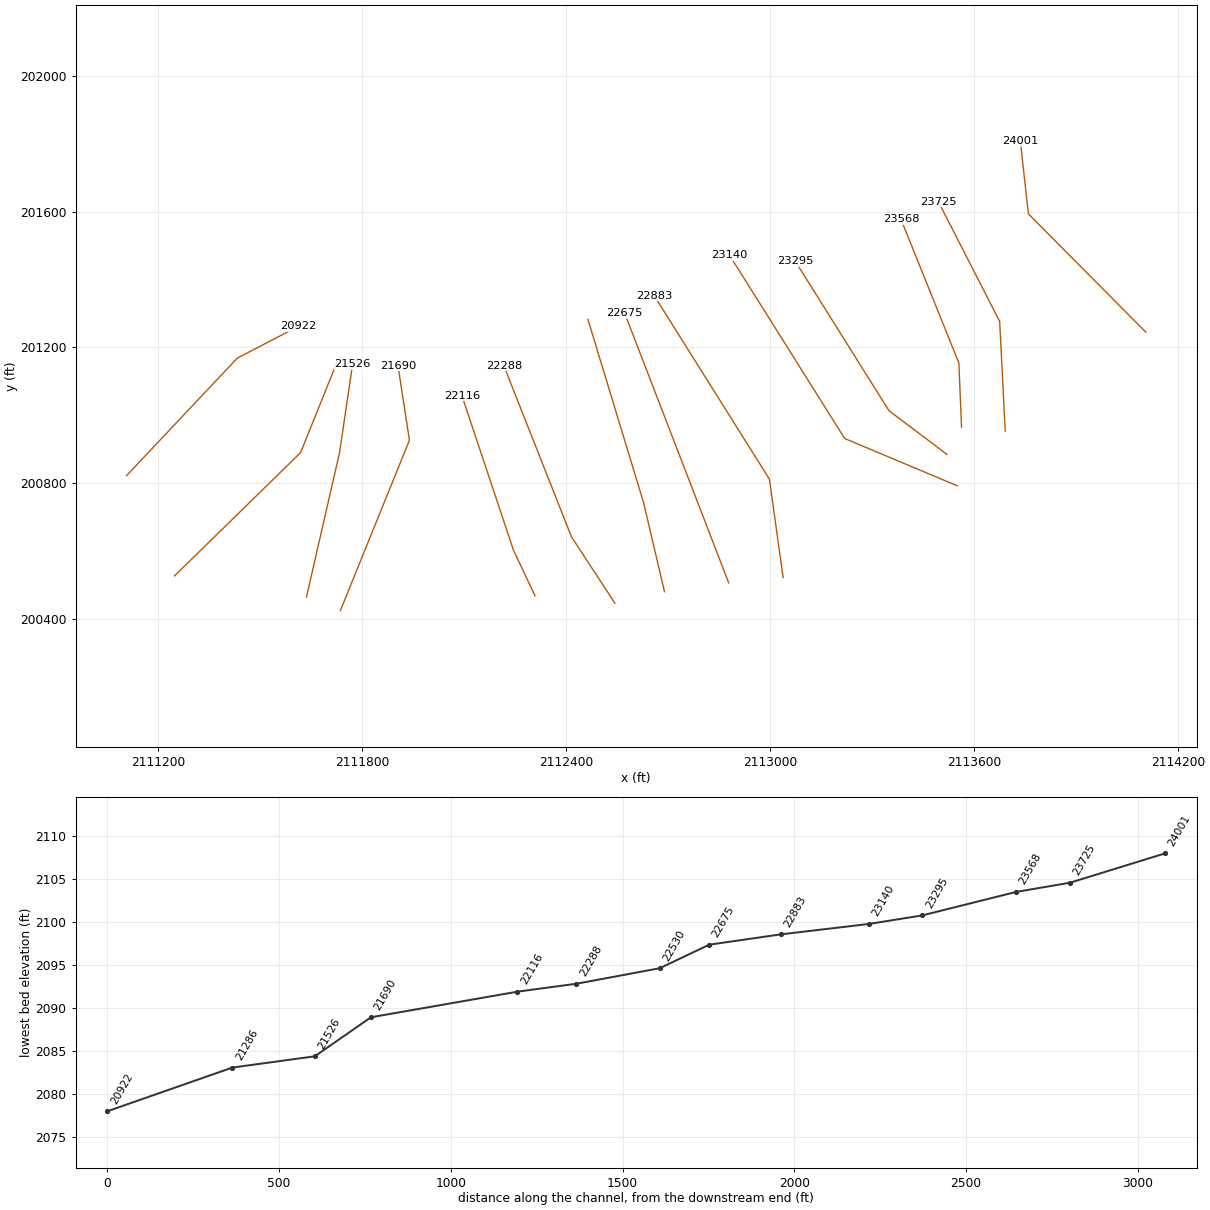
HEC-RAS study TCKTTBR.prj: TCKTTBR

--- TCKTTBR.g01 (geometry) --- (continued)

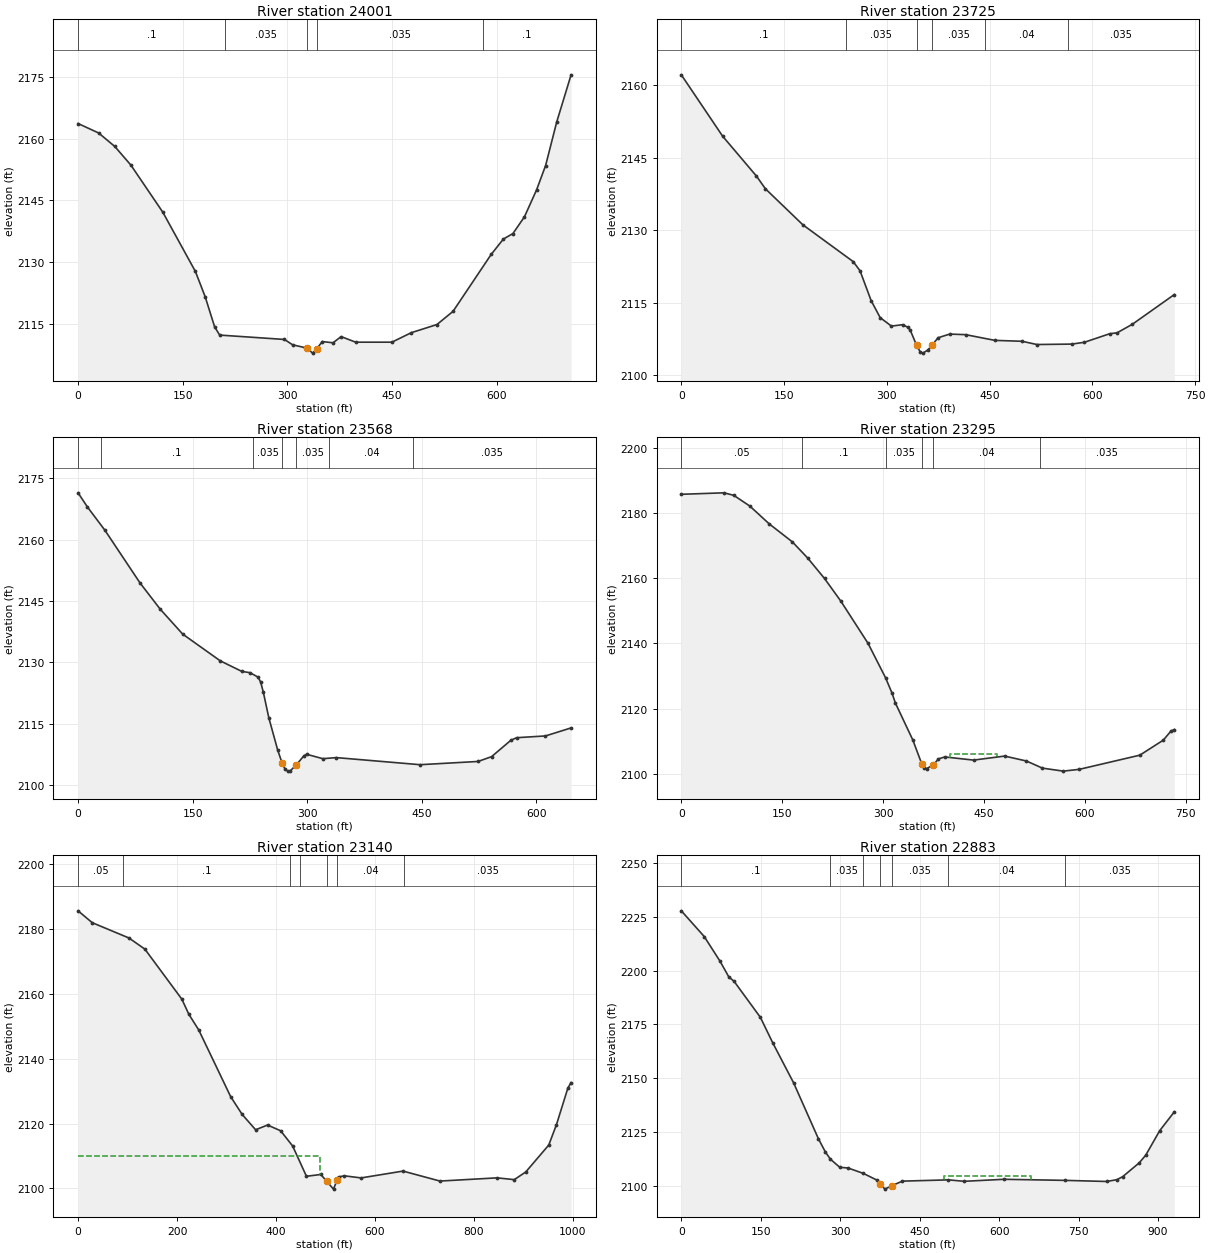
Type RM Length L Ch R = 1 ,24001   ,281,276.7,271
XS GIS Cut Line= 3
      2114104.46      201245.263 2113759.2946517201593.849865154
     2113735.537      201808.414
#Sta/Elev= 30
       0 2163.68    29.5 2161.38    52.6 2158.11    75.7 2153.58   121.5 2142.13
   168.1 2127.77   182.1 2121.64   195.7  2114.3   202.9 2112.32   295.7 2111.26
   307.3 2109.97   328.1 2109.15     336 2107.94   342.1 2109.02   349.9 2110.75
   365.3 2110.45   376.9 2111.95   397.7  2110.6   449.7  2110.6   477.4  2112.9
   514.2 2114.88   537.3 2118.09   591.9  2131.9   609.4 2135.64   623.1 2136.97
   639.6 2141.04     657 2147.59   669.9 2153.48   685.8 2164.05   706.4  2175.5
#Mann= 5 ,-1 , 0
       0      .1       0     210    .035       0   328.1    .045       0
   342.1    .035       0  580.56      .1       0
Bank Sta=328.1,342.1
XS Rating Curve= 0 ,0
Exp/Cntr=0.3,0.1

Type RM Length L Ch R = 1 ,23725   ,158,156.8,155.6
XS GIS Cut Line= 3
     2113691.049      200953.379     2113674.773       201276.73
     2113494.651      201629.377
#Sta/Elev= 30
       0  2162.1    60.3 2149.41   109.6 2141.17   122.7 2138.54   177.5 2131.07
   250.9 2123.47   260.9 2121.57   277.1 2115.39   290.3 2111.88   306.7 2110.13
   323.1 2110.42   330.8 2109.88   334.1 2109.32   343.42106.175   348.8 2104.78
   352.7 2104.54   360.1 2105.21   366.32106.251   374.8 2107.72   391.8 2108.48
   415.1 2108.36   457.6 2107.18   497.4 2106.99   519.1 2106.32   569.9 2106.41
   588.3 2106.78   625.1 2108.54   636.2 2108.75   658.3  2110.5   719.7 2116.66
#Mann= 6 ,-1 , 0
       0      .1       0     240    .035       0   343.4    .045       0
   366.3    .035       0  443.76     .04       0  563.76    .035       0
Bank Sta=343.4,366.3
XS Rating Curve= 0 ,0
Exp/Cntr=0.3,0.1

Type RM Length L Ch R = 1 ,23568   ,270,273,274.9
XS GIS Cut Line= 3
     2113562.577      200965.315     2113554.764      201154.117
      2113384.56      201577.631
#Sta/Elev= 30
       0  2171.4    12.2 2167.96    35.2 2162.25    81.2 2149.38   107.5 2143.01
     137 2136.91   186.3 2130.37   214.3 2127.82     225  2127.5   235.6 2126.42
   239.1 2125.18   242.6 2122.67   249.7  2116.5   261.3 2108.63   267.22105.383
   270.9 2103.98   274.5 2103.47     278 2103.58   285.32104.924   295.7 2107.22
   299.2 2107.58   320.4 2106.51   338.1 2106.77   447.7 2105.04   523.6 2105.83
   541.3    2107   566.5 2110.99   574.1 2111.63   611.9 2112.06   645.4 2114.02
#Mann= 7 ,-1 , 0
       0     .05       0      30      .1       0  228.96    .035       0
   267.2    .045       0   285.3    .035       0  328.96     .04       0
  438.96    .035       0
Bank Sta=267.2,285.3
XS Rating Curve= 0 ,0
Exp/Cntr=0.3,0.1

Type RM Length L Ch R = 1 ,23295   ,154.5,154.6,154.5
XS GIS Cut Line= 3
     2113519.608      200884.586     2113349.035      201013.492
     2113073.645      201454.116
#Sta/Elev= 30
       0 2185.88    63.5 2186.33      78 2185.56   101.9 2182.26   130.7 2176.79
   165.1 2171.26   187.7 2166.34     213 2159.99   237.2 2153.05   277.7 2140.07
   303.9 2129.42   313.4 2124.76   318.4 2121.71   344.4 2110.31   357.62103.017
     361 2101.84   364.8 2101.51     3752102.697   382.5 2104.51   391.9 2105.11
   434.8 2104.14   480.9 2105.38   513.4 2103.86   537.2 2101.67   568.2 2100.75
     592  2101.3   682.1 2105.66   716.9 2110.27   728.5 2113.09   733.4 2113.54
#Mann= 6 ,-1 , 0
       0     .05       0     180      .1       0   303.8    .035       0
   357.6    .045       0     375     .04       0   533.8    .035       0
#XS Ineff= 1 ,-1
  400.11  470.09 2106.08
Permanent Ineff=
       F
Bank Sta=357.6,375
XS Rating Curve= 0 ,0
Exp/Cntr=0.3,0.1

Type RM Length L Ch R = 1 ,23140   ,256.3,257.2,256
XS GIS Cut Line= 3
     2113549.556      200792.138     2113218.827      200931.461
     2112880.285      201471.825
#Sta/Elev= 30
       0 2185.69    28.6 2182.03   102.9  2177.3     135 2173.87   209.7 2158.43
     224 2153.72     244 2148.88   308.5 2128.29   331.7 2122.82   358.9 2118.08
     383 2119.55   409.4 2117.78   433.7 2113.08   461.6 2103.73   490.7 2104.28
   502.82102.124   516.3 2099.76   523.42102.555   526.4  2103.5   537.8 2103.88
     572 2103.22   656.8 2105.33   731.4 2102.25   846.9 2103.24   881.7 2102.69
   904.9 2105.06   951.4 2113.38   966.9 2119.65     990 2130.96   996.5 2132.68
#Mann= 7 ,-1 , 0
       0     .05       0      90      .1       0  428.88    .035       0
  448.88     .04       0   502.8    .045       0   523.4     .04       0
  658.88    .035       0
#XS Ineff= 2 , 0
          488.23 2109.96
Permanent Ineff=
       F       F
Bank Sta=502.8,523.4
XS Rating Curve= 0 ,0
Exp/Cntr=0.3,0.1

Type RM Length L Ch R = 1 ,22883   ,211.9,208.6,204
XS GIS Cut Line= 3
     2113037.837      200521.304     2112997.472      200811.669
     2112658.931      201352.034
#Sta/Elev= 30
       0  2227.7    43.3 2215.75    73.1 2204.31    89.6 2197.06    99.6 2194.99
   149.3 2178.26   172.4 2166.53   212.1 2147.82   258.8 2121.94   271.8 2115.87
   281.3 2112.48   299.2 2108.68   314.7 2108.36   343.6 2105.86   368.9 2102.78
   374.92101.153   384.4 2098.55   397.82100.189   417.4 2102.26   504.4 2102.85
     534 2102.18   608.9 2103.11   723.5 2102.62     803  2102.1   822.4 2102.93
   833.5 2104.38   864.4 2110.72   876.8 2114.31   903.1 2125.65   930.8 2134.45
#Mann= 7 ,-1 , 0
       0      .1       0   281.3    .035       0   343.6      .1       0
   374.9    .045       0   397.8    .035       0   504.4     .04       0
   723.5    .035       0
#XS Ineff= 1 ,-1
     496     660 2104.43
Permanent Ineff=
       F
Bank Sta=374.9,397.8
XS Rating Curve= 0 ,0
Exp/Cntr=0.3,0.1

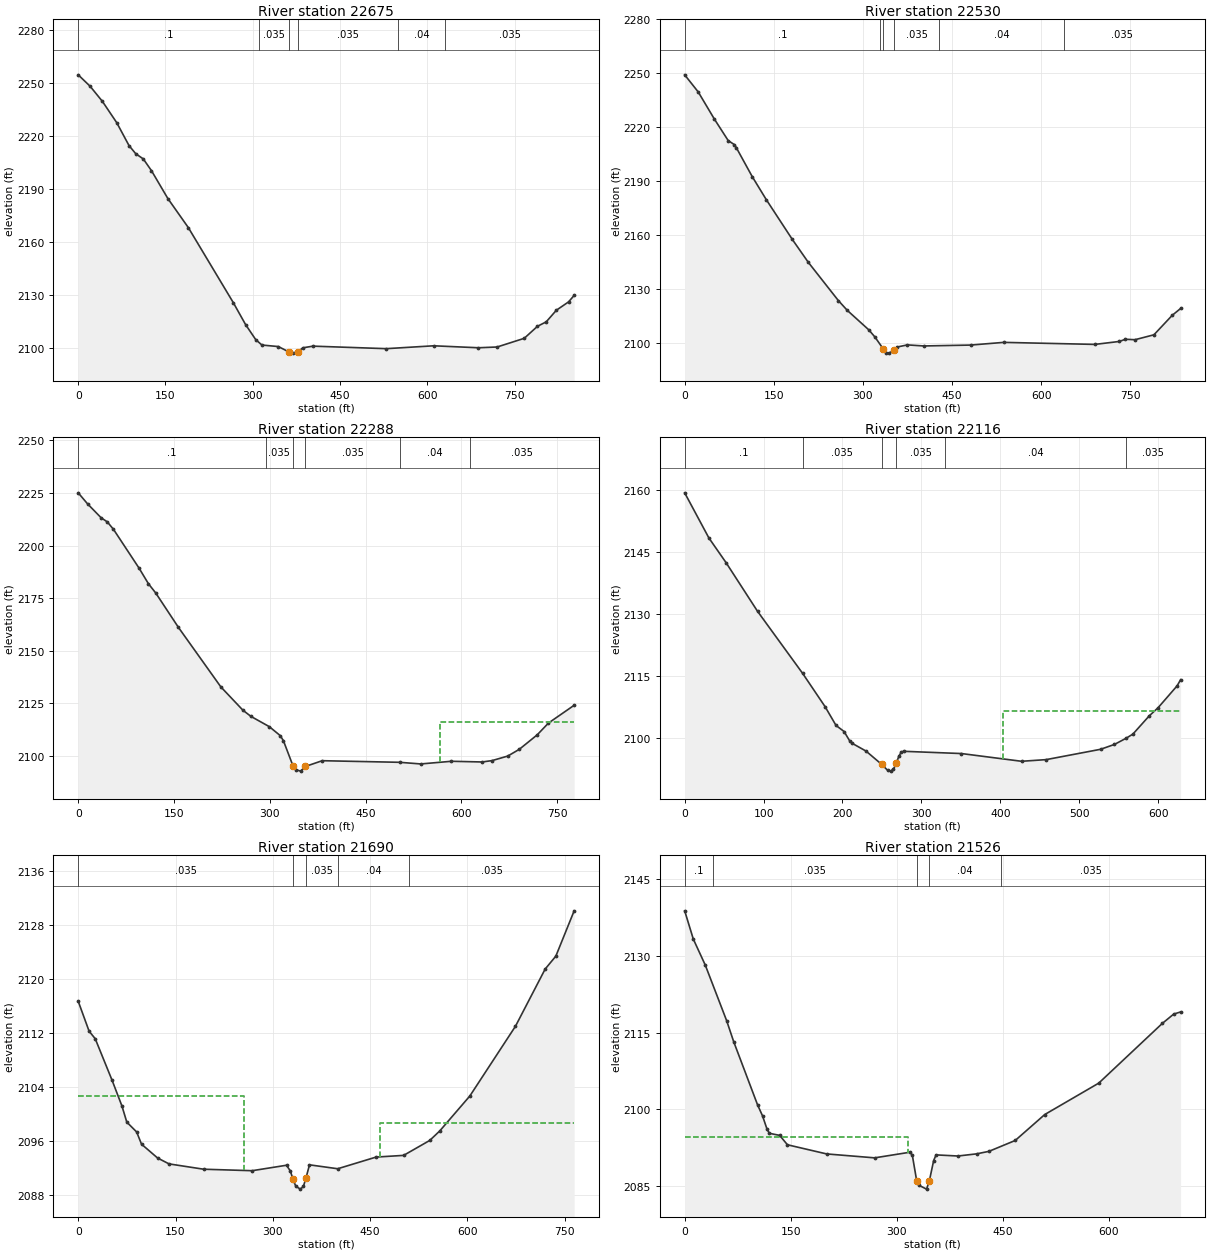
Type RM Length L Ch R = 1 ,22675   ,145.1,144.2,143.3
XS GIS Cut Line= 2
     2112877.738      200505.665     2112571.691      201301.252
#Sta/Elev= 30
       0 2254.49    20.5 2248.02    41.6 2239.49    66.2 2227.48    87.3 2214.55
    98.9 2209.94   111.9 2206.99   125.9 2200.38   154.1 2184.63   189.2 2168.26
   266.5 2125.89   287.6 2113.51   305.2 2104.93   315.8 2101.91   343.9 2101.06
   362.82097.925   368.5 2097.35   377.82098.173   386.1 2100.35   403.6 2101.29
   529.5 2099.87     611 2101.49   687.9 2100.38     720 2100.81   766.6 2105.71
   789.4 2112.51   804.4 2115.01   821.9 2121.59   842.8 2126.28   852.4 2129.95
#Mann= 6 ,-1 , 0
       0      .1       0     310    .035       0   362.8    .045       0
   377.8    .035       0     550     .04       0     630    .035       0
Bank Sta=362.8,377.8
XS Rating Curve= 0 ,0
Exp/Cntr=0.3,0.1

Type RM Length L Ch R = 1 ,22530   ,240.8,242.4,243.3
XS GIS Cut Line= 3
     2112688.879      200479.638     2112627.681      200741.357
     2112463.618      201283.023
#Sta/Elev= 30
       0 2249.11    22.8  2239.6    49.7 2224.69    73.3 2212.59    83.4 2210.42
    86.8 2208.75   113.7  2192.6   137.3 2179.85   181.2 2157.72   208.1 2145.01
   258.6 2123.82   273.8 2118.32   309.9 2107.54   320.2 2103.57   334.22096.965
   339.6 2094.92   344.2 2094.62   352.62096.427     358 2098.04     375 2099.19
   402.4  2098.6   481.3 2099.09   536.9 2100.59   690.4 2099.46   731.5  2101.1
   741.8 2102.31   757.9 2102.07   789.8  2104.8   820.6 2115.62   834.7 2119.41
#Mann= 6 ,-1 , 0
       0      .1       0  328.78    .035       0   334.2    .045       0
   352.6    .035       0  428.78     .04       0  638.78    .035       0
Bank Sta=334.2,352.6
XS Rating Curve= 0 ,0
Exp/Cntr=0.3,0.1

Type RM Length L Ch R = 1 ,22288   ,173,171.8,171
XS GIS Cut Line= 3
     2112543.045      200445.784     2112415.441      200641.096
     2112216.222      201146.304
#Sta/Elev= 30
       0 2225.03    14.7 2219.77      36 2213.14    45.5 2211.24    55.2 2207.69
    95.3 2189.23     110 2181.81   121.4 2177.43   156.9  2161.1   223.3 2132.83
     258 2121.71   270.5 2118.81   299.2 2113.94   316.3 2109.68   321.3 2107.24
   336.5  2095.1     341 2093.48   348.1 2092.82   355.52095.022     382 2097.77
   503.3 2097.01   536.3 2096.23   584.3  2097.5   632.4 2097.17   647.9 2097.82
   672.5 2099.98   690.6  2103.2   718.4 2110.01   736.2 2115.66   776.4 2124.11
#Mann= 6 ,-1 , 0
       0      .1       0   293.3    .035       0   336.5    .045       0
   355.5    .035       0   503.3     .04       0   613.3    .035       0
#XS Ineff= 2 , 0
                          566.99         2115.98
Permanent Ineff=
       F       F
Bank Sta=336.5,355.5
XS Rating Curve= 0 ,0
Exp/Cntr=0.3,0.1

Type RM Length L Ch R = 1 ,22116   ,435.1,426.5,415.3
XS GIS Cut Line= 3
2112308.00224719200467.5062134742112244.41802246200602.704438206
     2112093.199      201057.306
#Sta/Elev= 30
       0  2159.2    30.7 2148.28    52.4 2142.33    92.3 2130.56   149.4 2115.56
   177.9  2107.5   191.8 2102.95     202 2101.48     209 2099.25   212.5  2098.6
   229.8 2096.75   249.52093.559   257.4 2092.06   260.9  2091.9   264.4 2092.31
   268.3 2093.85   271.3 2095.46   274.7 2096.57   278.2 2096.69   350.8 2096.15
   426.9 2094.28     458 2094.68   527.1 2097.18   544.7 2098.36   559.4 2099.85
     568 2100.85   588.8 2105.28   599.8  2107.2     624 2112.51   628.5 2114.01
#Mann= 6 ,-1 , 0
       0      .1       0   149.4    .035       0   249.5    .045       0
   268.3    .035       0   329.4     .04       0   559.4    .035       0
#XS Ineff= 2 , 0
                          403.04         2106.36
Permanent Ineff=
       F       F
Bank Sta=249.5,268.3
XS Rating Curve= 0 ,0
Exp/Cntr=0.3,0.1

Type RM Length L Ch R = 1 ,21690   ,160.1,163.7,165.3
XS GIS Cut Line= 3
2111735.57510114200423.9039662792111938.65216853200926.212123588
     2111905.024      201146.304
#Sta/Elev= 30
       0 2116.77    16.8 2112.33    26.2 2111.22    52.3 2105.04    67.4 2101.25
    74.9 2098.86    90.1  2097.4    97.6 2095.59   122.4 2093.54     140 2092.67
   193.4 2091.88   268.1 2091.66   321.1 2092.47   326.9 2091.63   331.32090.362
   335.3 2089.37   342.4 2088.93   347.1 2089.32   350.92090.507   356.5 2092.53
     400 2091.95   459.2 2093.68   501.6 2093.93   541.8 2096.14   557.2 2097.54
   603.7 2102.73     674 2113.06   719.8 2121.54   736.3 2123.46   764.5 2130.17
#Mann= 5 ,-1 , 0
       0    .035       0   331.3    .045       0   350.9    .035       0
     400     .04       0     510    .035       0
#XS Ineff= 2 , 0
             256 2102.69  464.65         2098.72
Permanent Ineff=
       F       F
Bank Sta=331.3,350.9
XS Rating Curve= 0 ,0
Exp/Cntr=0.3,0.1

Type RM Length L Ch R = 1 ,21526   ,238.6,239.5,223.1
XS GIS Cut Line= 3
2111635.78615729200463.640089886     2111733.149      200889.794
2111771.63358427201151.179044943
#Sta/Elev= 30
       0 2138.86    12.2 2133.33    29.1 2128.25    59.4 2117.34    69.4 2113.22
   103.1 2100.88   110.1 2098.73   116.6 2096.07   119.9 2095.32   134.3 2094.92
   145.3 2093.08   200.7 2091.29   268.6 2090.52   318.5 2091.62   321.9 2091.04
   328.2 2085.94   331.9 2085.11     342  2084.4  345.91 2085.97   352.1    2090
   355.5  2091.1   386.4 2090.88   412.7  2091.3   430.2 2091.79   467.4 2093.92
   509.2    2099   585.5 2105.14   675.5 2116.84   691.6 2118.66   701.3 2119.07
#Mann= 5 ,-1 , 0
       0      .1       0      40    .035       0   328.2    .045       0
  345.91     .04       0  447.13    .035       0
#XS Ineff= 2 , 0
          315.49 2094.55
Permanent Ineff=
       F       F
Bank Sta=328.2,345.91
XS Rating Curve= 0 ,0
Exp/Cntr=0.3,0.1

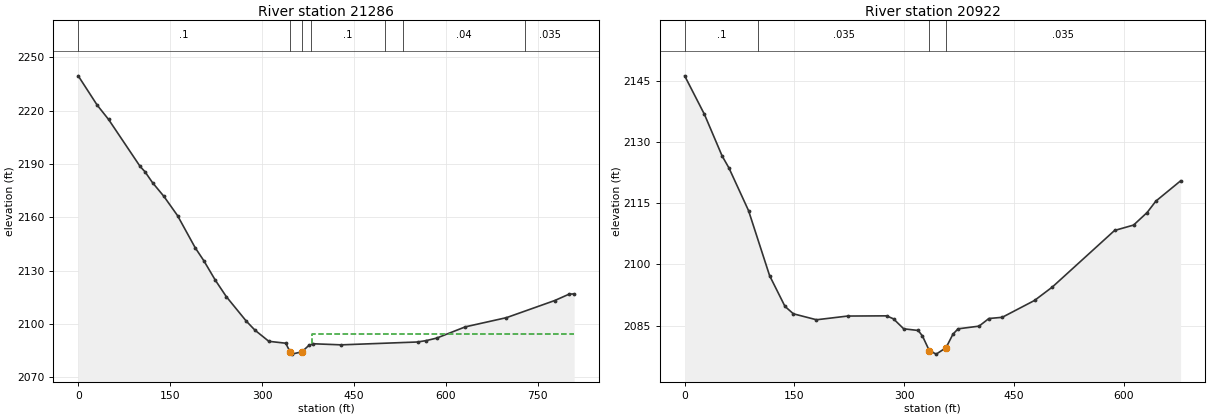
Type RM Length L Ch R = 1 ,21286   ,360.6,364.2,362.4
XS GIS Cut Line= 3
     2111247.606      200526.154     2111618.566      200889.794
     2111726.645      201158.865
#Sta/Elev= 30
       0 2239.68    30.9 2223.23    49.6 2215.12   101.1 2188.67     109 2185.71
   121.3 2179.57   139.9 2171.84   162.1 2161.04   190.9 2142.97   204.9 2135.72
   223.8 2124.69   241.7 2115.45   274.4 2101.63   288.6 2096.54   311.1 2090.31
   338.7 2089.24  345.61 2084.45   348.7  2083.1   364.9 2084.39   376.5 2088.01
   383.5 2088.93   429.2 2088.32   553.9 2089.93   568.1 2090.72     585 2092.11
   631.7 2098.44   698.9 2103.62   777.8 2113.27   801.4 2116.88   809.4 2116.96
#Mann= 7 ,-1 , 0
       0      .1       0  345.61    .045       0   364.9    .035       0
     380      .1       0     500    .035       0  529.47     .04       0
  729.47    .035       0
#XS Ineff= 2 , 0
                          381.55         2094.69
Permanent Ineff=
       F       F
Bank Sta=345.61,364.9
XS Rating Curve= 0 ,0
Exp/Cntr=0.3,0.1

Type RM Length L Ch R = 1 ,20922   ,110.3,109.9,110.4
XS GIS Cut Line= 3
     2111106.847      200822.086     2111432.368       201168.44
     2111612.056       201262.19
#Sta/Elev= 30
       0 2146.15      27 2136.72    51.2 2126.53    60.4 2123.64    87.3 2113.16
   116.1 2097.24   137.1 2089.72   148.6  2087.9   180.2 2086.44   222.8 2087.35
   276.1  2087.4   285.5 2086.66   299.4 2084.23   319.2 2083.82     325 2082.49
   334.4  2078.9   343.9 2078.03   357.32079.604   366.7  2082.9   373.7 2084.22
   402.4 2084.88   415.9 2086.75   434.1 2087.04   478.3 2091.17   502.6 2094.45
   587.7  2108.3   613.7 2109.62   632.2 2112.69   644.2 2115.49     678 2120.45
#Mann= 4 ,-1 , 0
       0      .1       0     100    .035       0   334.4    .045       0
   357.3    .035       0
Bank Sta=334.4,357.3
XS Rating Curve= 0 ,0
Exp/Cntr=0.3,0.1