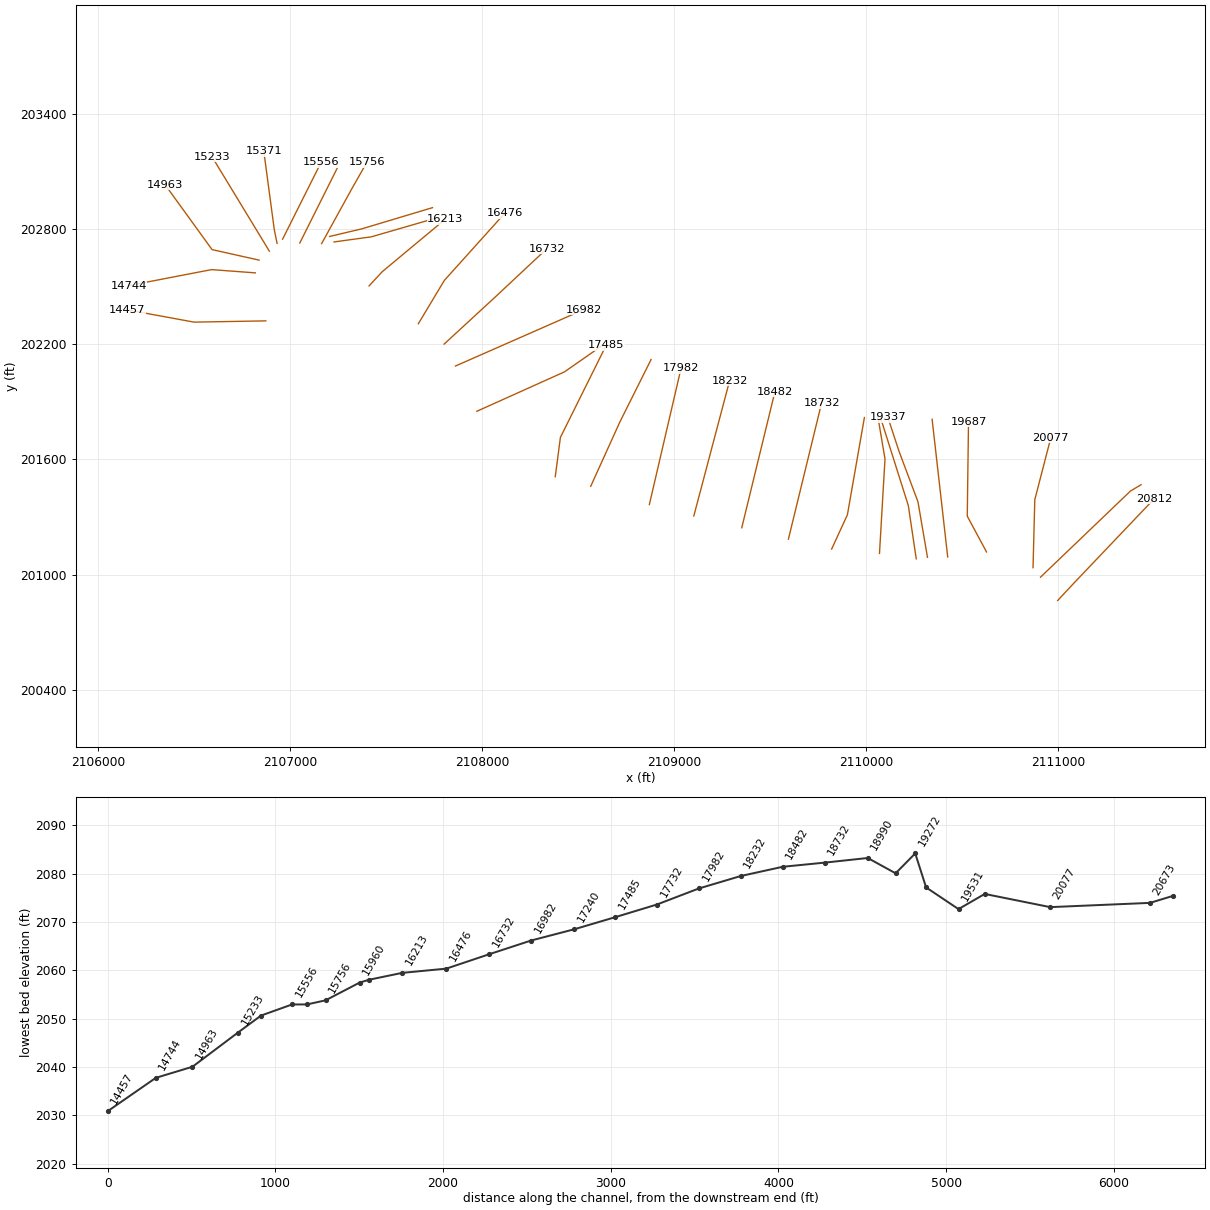
HEC-RAS study TCKTTBR.prj: TCKTTBR

--- TCKTTBR.g01 (geometry) --- (continued)

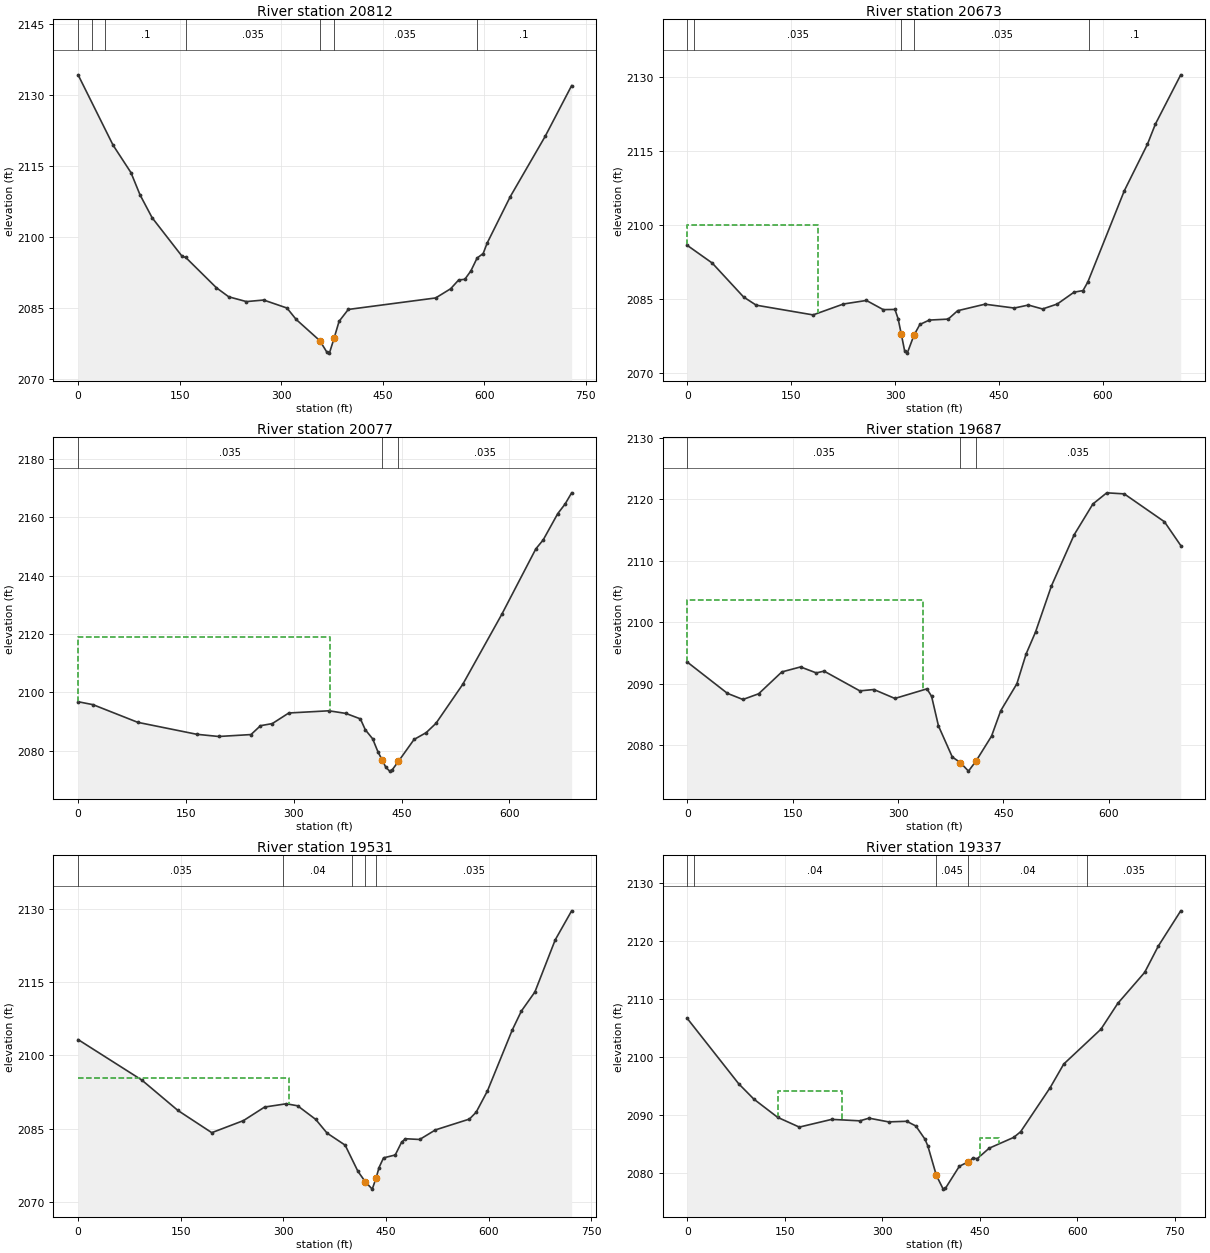
Type RM Length L Ch R = 1 ,20812   ,138.9,139.4,138.4
XS GIS Cut Line= 3
2110998.13689389200864.721553054     2111086.014      200958.804
     2111500.077        201393.7
#Sta/Elev= 30
       0 2134.26    51.7 2119.39    78.1  2113.6    91.5  2108.9   109.4 2104.06
   153.5 2095.94   159.1 2095.66   204.4 2089.26   222.6 2087.35   248.7 2086.34
   274.2 2086.67   308.6 2084.98   322.2 2082.57   357.1 2078.09   367.5 2075.67
   371.3 2075.45   378.2 2078.58   385.6 2082.17   399.2 2084.68   528.3 2087.11
   550.4 2089.05   562.3 2090.91   571.4 2091.05   580.4 2092.84   589.5 2095.54
   598.5  2096.5   604.4 2098.71   638.5 2108.51   690.1 2121.26   729.2 2131.98
#Mann= 7 ,-1 , 0
       0      .1       0      20    .035       0      40      .1       0
  158.74    .035       0   357.1    .045       0   378.2    .035       0
  588.74      .1       0
Bank Sta=357.1,378.2
XS Rating Curve= 0 ,0
Exp/Cntr=0.3,0.1

Type RM Length L Ch R = 1 ,20673   ,573.4,595.5,589.6
XS GIS Cut Line= 3
     2110908.953      200986.399     2111377.124      201434.694
     2111432.346      201467.669
#Sta/Elev= 30
       0 2095.83    36.1 2092.24    81.5 2085.34    99.7 2083.69   181.7 2081.72
   225.6 2083.93   258.7 2084.65     283 2082.79   299.9 2082.83   304.5 2080.94
   308.92077.945   313.8  2074.5   317.7 2073.97   327.42077.613   335.9 2079.78
   349.5 2080.67   376.8 2080.87   390.4 2082.57   429.8 2083.89   472.2 2083.11
   492.5 2083.72     513 2082.92   534.3 2083.93   558.5 2086.33   571.4 2086.65
   578.4  2088.4   631.1 2106.91   664.4 2116.32   675.9 2120.41   712.5  2130.4
#Mann= 5 ,-1 , 0
       0      .1       0      10    .035       0   308.9    .045       0
   327.4    .035       0     580      .1       0
#XS Ineff= 2 , 0
          188.39 2099.99
Permanent Ineff=
       F       F
Bank Sta=308.9,327.4
XS Rating Curve= 0 ,0
Exp/Cntr=0.3,0.1

Type RM Length L Ch R = 1 ,20077   ,382.3,390.3,388.6
XS GIS Cut Line= 3
     2110869.868      201035.627     2110879.069      201389.762
     2110962.316      201711.409
#Sta/Elev= 30
       0 2096.83    20.7 2095.83      83 2089.78   165.1 2085.69   195.6 2084.94
   240.5  2085.6   253.7 2088.63   270.1 2089.35   293.1 2092.98   348.9 2093.73
   372.4 2092.84   392.7 2090.96   399.5 2087.24   409.7 2084.16   417.3 2079.57
   422.7 2077.05     428 2074.41   433.4 2073.09   436.8 2073.48   445.52076.406
   467.3 2083.92   484.2 2086.26   497.8 2089.44   535.1  2102.8   589.3 2126.71
   636.7 2149.12   646.9 2152.17   667.2 2161.18   677.4 2164.46   686.5 2168.29
#Mann= 3 ,-1 , 0
       0    .035       0   422.7    .045       0   445.5    .035       0
#XS Ineff= 2 , 0
           349.8 2119.14
Permanent Ineff=
       F       F
Bank Sta=422.7,445.5
XS Rating Curve= 0 ,0
Exp/Cntr=0.3,0.1

Type RM Length L Ch R = 1 ,19687   ,154.3,156.5,156.2
XS GIS Cut Line= 3
     2110627.681      201117.659      2110527.42      201303.857
     2110533.931      201794.742
#Sta/Elev= 30
       0 2093.55    57.2 2088.46    79.3 2087.46   101.7 2088.39   134.7 2091.94
   161.3 2092.75   183.7 2091.78   194.8 2092.07   245.7 2088.86   265.7 2089.08
   295.6 2087.63   341.2 2089.19   347.8 2087.98   357.6 2083.17   377.3 2078.11
   388.8 2077.21   400.3 2075.82   411.12077.466   433.1  2081.5   446.2 2085.63
   469.2 2090.02   482.3 2094.85   495.7 2098.41   518.4 2105.92   550.7 2114.22
   577.4 2119.23   597.1 2121.04     622 2120.87   679.2 2116.34   702.4 2112.48
#Mann= 3 ,-1 , 0
       0    .035       0   388.8    .045       0   411.1    .035       0
#XS Ineff= 2 , 0
          335.56 2103.64
Permanent Ineff=
       F       F
Bank Sta=388.8,411.1
XS Rating Curve= 0 ,0
Exp/Cntr=0.3,0.1

Type RM Length L Ch R = 1 ,19531   ,171.5,193.2,198.3
XS GIS Cut Line= 2
2110425.57027509201091.7316221432110344.37266101201808.456715661
#Sta/Elev= 30
       0 2103.25    93.1 2094.98   145.9 2088.76   195.4 2084.22   241.7 2086.69
   272.6 2089.46   304.4 2090.13   320.9 2089.71   347.3 2086.93   363.8 2084.14
   390.3 2081.67     409 2076.31     420 2074.14   429.9 2072.68   435.7 2075.02
   439.8 2077.09   446.4 2079.07   463.5 2079.66   472.8 2082.28   478.4 2082.98
   499.2 2082.83   522.3 2084.79   571.9    2087   581.8 2088.41   598.3 2092.77
   634.4 2105.17   647.8 2109.07   667.6 2112.98   697.3 2123.63   721.3 2129.57
#Mann= 5 ,-1 , 0
       0    .035       0     300     .04       0     400    .035       0
     420    .045       0   435.7    .035       0
#XS Ineff= 2 , 0
          308.69 2095.49
Permanent Ineff=
       F       F
Bank Sta=420,435.7
XS Rating Curve= 0 ,0
Exp/Cntr(USF)=0,0
Exp/Cntr=0.5,0.3

Type RM Length L Ch R = 1 ,19337   ,81.2,64.9,64.6
XS GIS Cut Line= 4
2110320.21695281201089.6676876412110270.87632833201378.301424622
2110171.84178453201642.3935414332110114.23198653201817.696359551
#Sta/Elev= 30
       0  2106.6    79.3 2095.32   102.6 2092.68   139.2 2089.54   172.5 2087.86
   222.4 2089.19   265.7 2088.94   279.8  2089.4   309.8 2088.76   337.8 2088.86
   351.8 2088.05   365.9 2085.77   370.3  2084.6   383.4 2079.53   393.9 2077.17
   397.4 2077.32   418.7  2081.1   432.4 2081.88   439.4 2082.48   446.5 2082.44
   464.6 2084.22   502.5 2086.09   513.1 2087.07   558.6 2094.68   579.4 2098.73
   636.6 2104.73   662.4 2109.16   703.9 2114.52   724.9 2119.06   759.4 2125.13
#Mann= 5 ,-1 , 0
       0    .035       0      10     .04       0   383.4    .045       0
   432.4     .04       0  614.87    .035       0
#XS Ineff= 2 ,-1
     140     238    2094     450     480    2086
Permanent Ineff=
       F       F
Bank Sta=383.4,432.4
XS Rating Curve= 0 ,0
Exp/Cntr=0.5,0.3

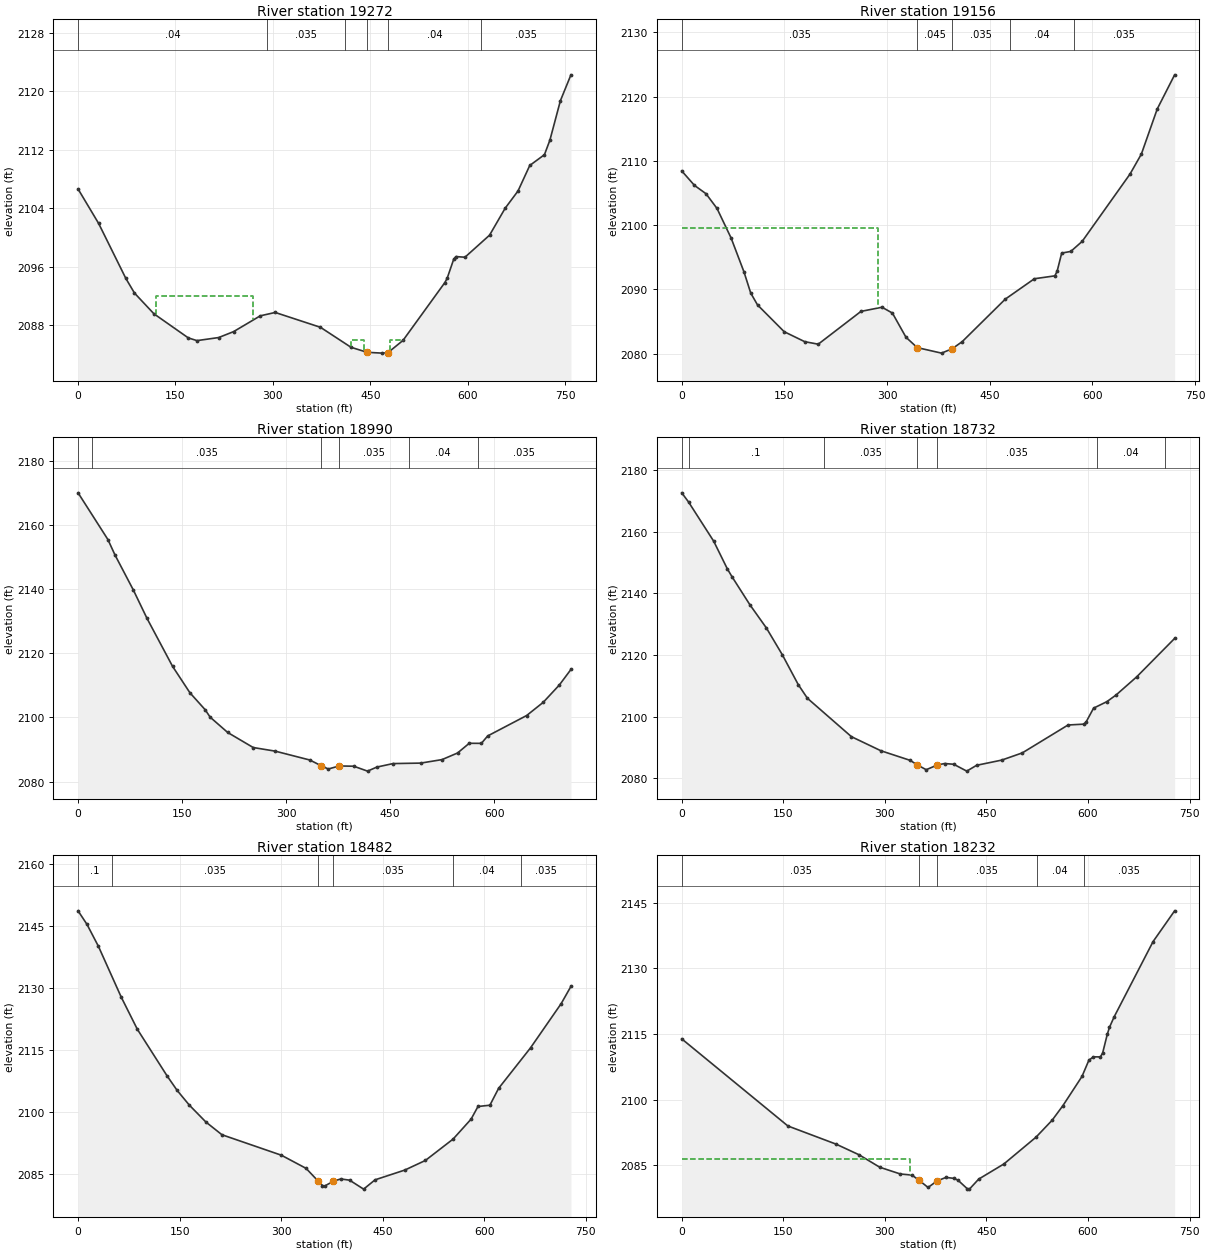
Type RM Length L Ch R = 1 ,19272   ,128,116.8,78.8
XS GIS Cut Line= 3
2110261.74406066201081.8556876412110220.43590561201359.354984269
     2110076.248      201815.575
#Sta/Elev= 30
       0 2106.65    31.7 2101.94    73.6 2094.42    86.9 2092.42   116.8 2089.59
   169.8 2086.29   183.1 2085.92   216.5 2086.34   239.5 2087.15   280.6 2089.31
   303.6 2089.77   373.3 2087.74   420.3 2085.01   445.2 2084.32   468.5 2084.21
     477 2084.26   500.4 2085.95   564.8 2093.85   568.3 2094.42   578.6 2097.08
     582 2097.41   595.8 2097.32   633.7 2100.34   657.7 2104.02   677.5 2106.38
   695.6 2109.87   718.2 2111.34   726.6 2113.33   742.8 2118.73     759 2122.26
#Mann= 6 ,-1 , 0
       0     .04       0  290.56    .035       0  410.56     .04       0
   445.2    .045       0     477     .04       0  620.56    .035       0
#XS Ineff= 3 ,-1
     120     270    2092     420     440    2086     480     500    2086
Permanent Ineff=
       F       F       F
Bank Sta=445.2,477
XS Rating Curve= 0 ,0
Exp/Cntr=0.5,0.3

Type RM Length L Ch R = 1 ,19156   ,165,166.1,175.2
XS GIS Cut Line= 3
     2110070.389      201109.846     2110099.035      201602.034
     2110061.274      201825.992
#Sta/Elev= 30
       0 2108.43    18.6 2106.18    35.4 2104.89    51.5  2102.6    72.1    2098
    90.9 2092.73   100.8 2089.43   110.7 2087.59   149.7 2083.42   179.7 2081.87
   199.4 2081.48   261.8 2086.58   292.6 2087.23   307.8 2086.32   327.6 2082.56
     344 2080.95   379.5 2080.09   395.1 2080.77   409.7 2081.87   472.7 2088.49
   515.2 2091.66   545.1 2092.11   548.4 2092.81   555.1 2095.65   568.4 2095.91
     585 2097.47   654.9 2107.94   671.5 2111.05   694.7 2118.07   720.1 2123.38
#Mann= 5 ,-1 , 0
       0    .035       0     344    .045       0   395.1    .035       0
     480     .04       0  573.02    .035       0
#XS Ineff= 2 , 0
          287.17 2099.58
Permanent Ineff=
       F       F
Bank Sta=344,395.1
XS Rating Curve= 0 ,0
Exp/Cntr=0.3,0.1

Type RM Length L Ch R = 1 ,18990   ,258.6,257.5,256.2
XS GIS Cut Line= 3
     2109821.257      201132.633     2109903.288      201311.018
      2109991.83      201817.528
#Sta/Elev= 30
       0 2169.94      43  2155.4    53.2  2150.6    79.7 2139.67    99.4 2130.83
   136.2 2115.91   161.3 2107.65   183.2 2102.39   190.4 2100.07   215.7  2095.3
   252.5 2090.61   284.1 2089.49   334.1 2086.72   350.32084.961   360.7 2083.92
   376.52084.871   397.4 2084.79   417.3 2083.26   430.7 2084.52     454 2085.61
   493.9 2085.76   524.7 2086.85     547  2088.9   563.9 2091.93   581.4 2091.91
   590.5 2094.22   646.6 2100.57   670.5 2104.68   693.8 2110.09   710.5 2114.93
#Mann= 6 ,-1 , 0
       0      .1       0      20    .035       0   350.3    .045       0
   376.5    .035       0  476.34     .04       0  576.34    .035       0
Bank Sta=350.3,376.5
XS Rating Curve= 0 ,0
Exp/Cntr=0.3,0.1

Type RM Length L Ch R = 1 ,18732   ,250.1,250,250
XS GIS Cut Line= 3
     2109596.124      201184.345      2109682.34      201537.987
     2109768.555       201891.63
#Sta/Elev= 30
       0 2172.67      10 2169.71    47.2 2156.96    67.4 2147.95    74.2 2145.44
   100.6 2136.34   125.1 2128.76   148.5 2120.11   172.1 2110.39   185.6 2105.96
   250.6 2093.49   294.1 2088.92   337.6 2085.78   347.6 2084.35   361.1 2082.76
   377.12084.257   388.2 2084.77   401.7 2084.53     421  2082.3   435.5 2084.19
   472.6 2085.88     503 2088.22   570.6 2097.28   594.2 2097.56   597.5 2098.36
   608.3 2102.75     628 2104.87   641.5 2107.02   671.9  2112.9     728 2125.39
#Mann= 7 ,-1 , 0
       0    .035       0      10      .1       0     210    .035       0
   347.6    .045       0   377.1    .035       0     614     .04       0
     714    .035       0
Bank Sta=347.6,377.1
XS Rating Curve= 0 ,0
Exp/Cntr=0.3,0.1

Type RM Length L Ch R = 1 ,18482   ,250.4,250,249.6
XS GIS Cut Line= 3
     2109353.238      201243.559     2109439.453      201597.201
     2109525.669      201950.843
#Sta/Elev= 30
       0 2148.73    13.2 2145.45    30.1 2140.14    63.9 2127.82    87.5 2120.11
   131.4 2108.84   146.4  2105.3   164.3 2101.76   188.8 2097.67   212.5 2094.59
   300.3 2089.64   336.8 2086.46   354.3 2083.44     361 2082.31   364.4  2082.2
   377.12083.355   388.1  2083.9     401 2083.61   421.8 2081.44   438.7 2083.69
   482.6 2086.05     513 2088.37     554 2093.55   580.5 2098.36   590.7 2101.42
   608.3 2101.73   621.1 2105.79   668.3  2115.6   713.6  2126.3     728 2130.46
#Mann= 6 ,-1 , 0
       0      .1       0      50    .035       0   354.3    .045       0
   377.1    .035       0     554     .04       0     654    .035       0
Bank Sta=354.3,377.1
XS Rating Curve= 0 ,0
Exp/Cntr=0.3,0.1

Type RM Length L Ch R = 1 ,18232   ,249.5,250,250.5
XS GIS Cut Line= 3
     2109103.588       201304.97     2109196.681      201656.864
     2109289.775      202008.758
#Sta/Elev= 30
       0 2113.87   156.8 2093.96     228 2089.81     262 2087.37   292.5 2084.53
   322.9 2082.99     340 2082.74   350.92081.517   363.8 2079.91   377.1  2081.4
   390.3 2082.21   401.4    2082   407.9 2081.59   421.5 2079.65   424.9 2079.53
   438.6 2081.82   475.8 2085.28   523.3 2091.41   547.1 2095.28   562.9 2098.59
   591.2 2105.29   601.4 2109.01   608.1 2109.76   618.4 2109.75   621.7 2110.65
   628.5 2114.89   631.8 2116.52   638.7 2118.91   696.2 2136.11     728 2143.13
#Mann= 5 ,-1 , 0
       0    .035       0   350.9    .045       0   377.1    .035       0
     524     .04       0     594    .035       0
#XS Ineff= 2 , 0
           337.5 2086.36
Permanent Ineff=
       F       F
Bank Sta=350.9,377.1
XS Rating Curve= 0 ,0
Exp/Cntr=0.3,0.1

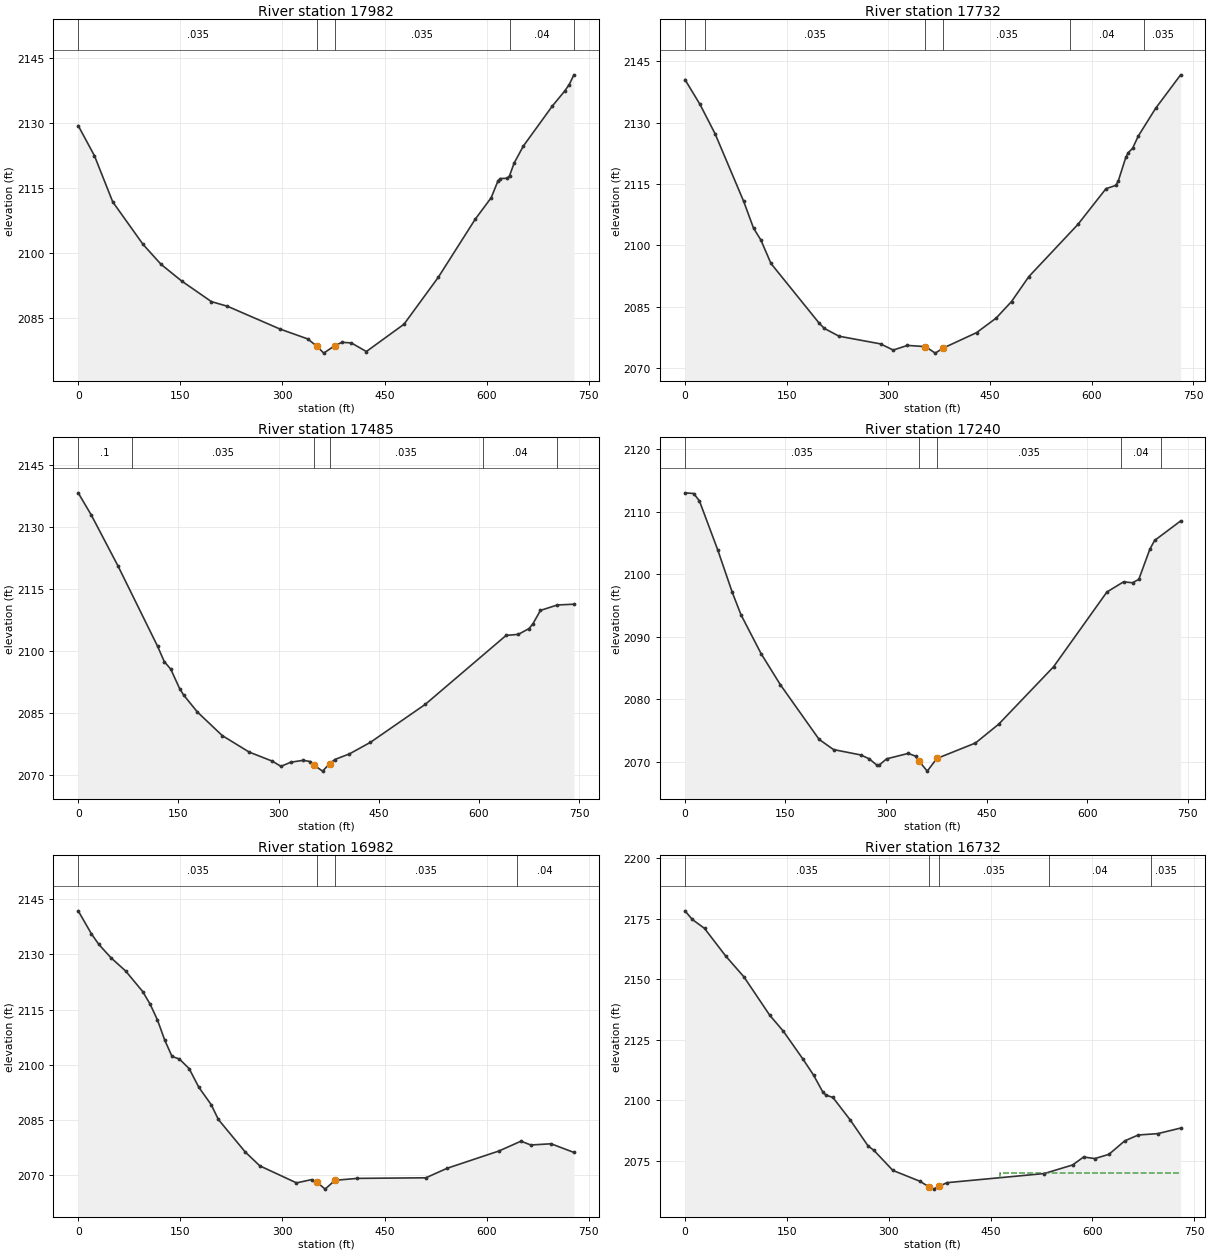
Type RM Length L Ch R = 1 ,17982   ,253.3,250,245.5
XS GIS Cut Line= 3
     2108872.097      201364.461     2108954.548         201719.
     2109036.999      202073.539
#Sta/Elev= 30
       0 2129.33    23.8 2122.41    50.7 2111.78    95.2 2101.99   121.5 2097.42
   151.8 2093.57   195.6 2088.81   219.2 2087.74   296.6 2082.48   337.1 2080.22
   350.92078.493   360.6 2076.95   377.12078.705   387.6 2079.44   401.1  2079.3
   423.2 2077.32   478.5 2083.61   529.1 2094.47   582.9 2107.74   606.5 2112.72
   616.6 2116.64     620 2117.14   630.1 2117.21   633.5 2117.79   640.2 2120.69
   653.7 2124.61   696.4 2133.85   714.3 2137.25   721.1 2138.78     728 2141.02
#Mann= 5 ,-1 , 0
       0    .035       0   350.9    .045       0   377.1    .035       0
     634     .04       0     728    .035       0
Bank Sta=350.9,377.1
XS Rating Curve= 0 ,0
Exp/Cntr=0.3,0.1

Type RM Length L Ch R = 1 ,17732   ,247.5,246.9,247.7
XS GIS Cut Line= 3
       2108566.8      201459.467     2108718.572      201794.453
     2108881.063       202119.43
#Sta/Elev= 30
       0 2140.58    22.2  2134.5    44.5  2127.3    86.6 2110.78   101.2 2104.21
     112 2101.31   126.9 2095.57   198.2 2080.92   205.7 2079.67   227.3 2077.77
   288.5 2075.89   307.2 2074.38   328.2 2075.52   354.8 2075.22   369.2 2073.63
   380.92074.864   430.1 2078.64     459  2082.2   481.7 2086.26   507.2 2092.35
   579.5 2105.11     621 2113.87   635.5 2114.67   639.2 2115.79   650.2 2121.51
   653.9 2122.71   660.2 2123.72   668.6 2126.74   694.2 2133.53   731.1 2141.73
#Mann= 6 ,-1 , 0
       0      .1       0      30    .035       0   354.8    .045       0
   380.9    .035       0  567.76     .04       0  677.76    .035       0
Bank Sta=354.8,380.9
XS Rating Curve= 0 ,0
Exp/Cntr=0.3,0.1

Type RM Length L Ch R = 1 ,17485   ,257,245.5,233.1
XS GIS Cut Line= 3
     2108382.072      201509.293     2108408.931      201714.013
     2108647.302       202193.91
#Sta/Elev= 30
       0 2138.18    19.6 2132.82    59.3 2120.63   118.9 2101.15   128.8 2097.48
   138.7 2095.61   151.9 2090.94   158.1 2089.35   178.4 2085.31   215.7 2079.61
     256 2075.63   290.9 2073.42   303.6 2072.18   318.3 2073.18   336.6 2073.63
   347.6 2073.35   353.52072.451   365.9 2071.03   376.42072.791   384.2 2073.83
   406.2 2075.19   437.7 2077.99   519.8 2087.15   640.8 2103.78     659 2104.02
   675.1 2105.43   680.9 2106.57   692.2 2109.81   717.6 2111.12   742.3 2111.31
#Mann= 6 ,-1 , 0
       0      .1       0      80    .035       0   353.5    .045       0
   376.4    .035       0  606.47     .04       0  716.47    .035       0
Bank Sta=353.5,376.4
XS Rating Curve= 0 ,0
Exp/Cntr=0.3,0.1

Type RM Length L Ch R = 1 ,17240   ,257.8,257.6,257.4
XS GIS Cut Line= 3
     2107973.675      201849.972     2108429.764      202055.159
     2108626.379      202191.877
#Sta/Elev= 30
       0 2113.05      13 2112.94    21.6 2111.76      49  2103.9    70.6 2097.13
    83.6 2093.54   113.7  2087.3   142.5 2082.32   200.2 2073.59   221.7 2071.96
   262.3  2071.1   274.7  2070.5   286.4 2069.47     290 2069.49   300.8 2070.47
   333.2 2071.35   344.2  2070.9   349.82070.054   361.5 2068.51   375.92070.535
   433.5 2073.01   468.2 2076.03     550 2085.21   629.6 2097.18   654.4  2098.8
   667.8 2098.66   677.2  2099.2   693.7 2104.04   700.8 2105.43   739.6 2108.55
#Mann= 5 ,-1 , 0
       0    .035       0   349.8    .045       0   375.9    .035       0
  650.12     .04       0  710.12    .035       0
Bank Sta=349.8,375.9
XS Rating Curve= 0 ,0
Exp/Cntr=0.3,0.1

Type RM Length L Ch R = 1 ,16982   ,245.3,250,254.7
XS GIS Cut Line= 3
     2107862.671      202085.783     2108195.881        202232.3
      2108529.09      202378.817
#Sta/Elev= 30
       0 2141.84    19.5 2135.56    30.3 2132.71    48.2 2129.07    69.7 2125.48
    94.8 2119.88   105.6 2116.47   116.3 2112.22   127.1 2106.68   137.8 2102.25
   148.6 2101.56   162.9 2098.95   177.2 2093.86   195.2 2089.18   205.9 2085.11
   245.3 2076.28   266.8  2072.5   320.6 2067.88   342.7 2068.76   350.92068.062
   362.6 2066.18   377.12068.578   409.9  2069.1   510.6 2069.26   541.8 2071.85
   618.1 2076.56   650.3 2079.22   664.7 2078.18   694.5 2078.51     728 2076.16
#Mann= 4 ,-1 , 0
       0    .035       0   350.9    .045       0   377.1    .035       0
     644     .04       0
Bank Sta=350.9,377.1
XS Rating Curve= 0 ,0
Exp/Cntr=0.3,0.1

Type RM Length L Ch R = 1 ,16732   ,254.7,255.7,256.5
XS GIS Cut Line= 3
     2107803.615      202199.972     2108072.948      202448.185
     2108338.299      202696.713
#Sta/Elev= 30
       0 2178.22    10.9 2174.65    28.8 2170.98      60 2159.57    86.8 2150.98
     125 2135.07   144.8 2128.56   173.7 2117.04   189.4 2110.39   202.8 2103.53
   207.3  2102.2   217.9 2101.17   243.5 2091.84   269.7 2081.14   278.3 2079.33
   306.1 2071.07   345.7 2066.62   358.82064.379   366.3 2063.34   373.82064.485
   385.9 2066.01     529 2069.77   570.8 2073.32     587 2076.61   603.3 2075.95
   624.2 2077.69   647.4 2083.25   667.4 2085.69     696 2086.24   729.8 2088.55
#Mann= 5 ,-1 , 0
       0    .035       0   358.8    .045       0   373.8    .035       0
  536.26     .04       0  686.26    .035       0
#XS Ineff= 2 , 0
                          464.57         2069.96
Permanent Ineff=
       F       F
Bank Sta=358.8,373.8
XS Rating Curve= 0 ,0
Exp/Cntr=0.3,0.1

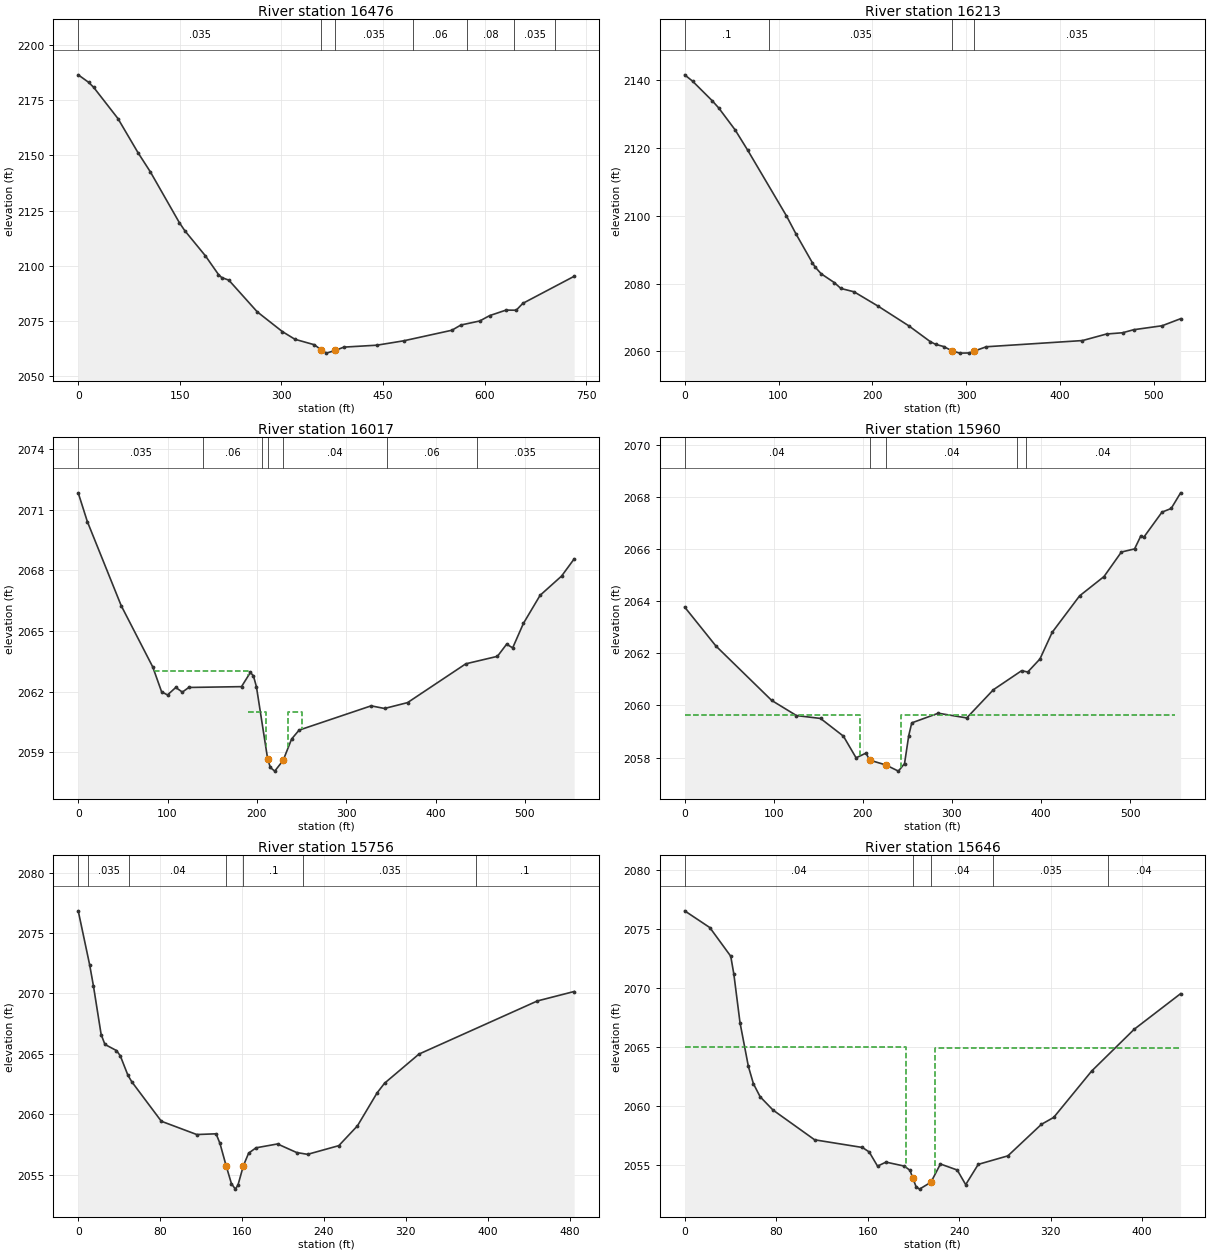
Type RM Length L Ch R = 1 ,16476   ,266.4,263.5,259.8
XS GIS Cut Line= 3
     2107669.266      202305.903     2107804.764      202531.721
     2108118.166      202879.986
#Sta/Elev= 30
       0 2186.53    15.3 2183.15    22.8 2180.86    58.6 2166.72    88.4 2151.16
   106.4 2142.58   149.2 2119.55   157.3 2115.87   187.8 2104.44     207    2096
   211.7 2094.64   222.3 2093.44   264.2 2079.08   301.4  2070.1     320 2066.62
   348.5 2064.16   358.42061.875   366.1 2060.36   379.4 2061.57     392 2063.08
   440.8 2063.96   480.3 2065.94   551.5 2070.74   564.7  2073.1   592.5 2074.93
   607.2 2077.37   631.3 2079.86   646.4 2079.82   656.2 2082.93   731.9 2095.19
#Mann= 7 ,-1 , 0
       0    .035       0   358.4    .045       0   379.4    .035       0
  493.35     .06       0  573.35     .08       0  643.35    .035       0
  703.35     .04       0
Bank Sta=358.4,379.4
XS Rating Curve= 0 ,0
Exp/Cntr=0.3,0.1

Type RM Length L Ch R = 1 ,16213   ,197.6,195.7,190.5
XS GIS Cut Line= 3
2107412.83475282202502.9572359362107481.29787643202576.998157309
2107810.04364046202850.676382023
#Sta/Elev= 30
       0  2141.6     8.4 2139.73    29.3 2133.97    36.3 2131.82    53.8 2125.34
    67.3  2119.3   108.4 2100.02   118.7 2094.62   136.2  2086.1   139.2 2084.84
   145.5 2082.89   159.5 2080.29   166.5 2078.56   180.5 2077.58   205.9 2073.39
   238.7 2067.57   261.8 2062.87   267.4 2062.08     276 2061.43   284.7 2060.19
   293.1 2059.48   303.3 2059.53   308.4 2060.06   321.5 2061.36     424 2063.19
   449.6 2065.12   466.7 2065.49   478.6 2066.39   508.9 2067.56   528.6 2069.64
#Mann= 4 ,-1 , 0
       0      .1       0      90    .035       0   284.7    .045       0
   308.4    .035       0
Bank Sta=284.7,308.4
XS Rating Curve= 0 ,0
Exp/Cntr=0.5,0.3

Type RM Length L Ch R = 1 ,16017   ,57.6,57.2,58.2
XS GIS Cut Line= 3
2107230.28501763202731.7960764992107424.53377066 202758.42471179
      2107769.49      202858.415
#Sta/Elev= 30
       0 2071.84    10.2 2070.42    48.1 2066.26    83.5 2063.22    93.4 2061.99
     100 2061.84   109.2 2062.21   116.6 2061.98   123.8 2062.21   182.8 2062.25
   192.7 2062.95   196.1 2062.79   199.5 2062.25   212.12058.668   215.1 2058.25
     220 2058.07   229.4  2058.6   238.9 2059.66   247.3  2060.1   327.9  2061.3
   342.9 2061.17   368.7 2061.46   433.9 2063.38   469.3 2063.75   479.6 2064.35
   486.4 2064.17   498.4 2065.38   517.1 2066.77   541.1 2067.72   555.2 2068.57
#Mann= 7 ,-1 , 0
       0    .035       0     140     .06       0  206.07     .04       0
   212.1    .045       0   229.4     .04       0  346.07     .06       0
  446.07    .035       0
#XS Ineff= 3 ,-1
      85     190    2063     190     210    2061     235     250    2061
Permanent Ineff=
       F       F       F
Bank Sta=212.1,229.4
XS Rating Curve= 0 ,0
Exp/Cntr=0.5,0.3

Type RM Length L Ch R = 1 ,15960   ,188.5,203.5,213.4
XS GIS Cut Line= 3
2107207.22439722202760.352632726 2107375.6821648202800.206188258
2107743.08058823202910.384794113
#Sta/Elev= 30
       0 2063.77      35 2062.28    97.7 2060.19   125.5 2059.61   152.5  2059.5
   178.2 2058.82   192.4 2057.99   203.5 2058.17   207.72057.901   225.72057.718
   239.9 2057.48   246.8 2057.77   251.5 2058.84   254.9 2059.33   284.7  2059.7
   316.6 2059.52   346.5  2060.6   378.2 2061.33   385.1 2061.28   398.8 2061.78
   412.5  2062.8   443.3  2064.2   470.7 2064.94   490.2 2065.88     505    2066
   511.8 2066.48   515.2 2066.44   535.8 2067.41   546.1 2067.55   556.7 2068.15
#Mann= 5 ,-1 , 0
       0     .04       0   207.7    .045       0   225.7     .04       0
  373.11     .06       0  383.11     .04       0
#XS Ineff= 2 ,-1
       0  196.97 2059.62  243.03   550.1 2059.62
Permanent Ineff=
       F       F
Bank Sta=207.7,225.7
XS Rating Curve= 0 ,0
Exp/Cntr=0.5,0.3

Type RM Length L Ch R = 1 ,15756   ,110.8,110.7,110.6
XS GIS Cut Line= 3
2107165.53418624202723.0041673362107323.99673155203010.889362018
     2107401.118      203146.304
#Sta/Elev= 30
       0 2076.84    11.2 2072.36    14.9 2070.61    22.4  2066.6    26.1 2065.78
    37.4 2065.27    41.1 2064.84    48.6 2063.22    52.4 2062.68    81.2 2059.42
   115.8 2058.32   134.7 2058.38   138.5 2057.58   144.52055.735   149.7 2054.25
   153.5  2053.8   156.1 2054.14   161.4 2055.75   166.5 2056.78   173.7 2057.22
   194.7 2057.54   213.4 2056.83   224.1 2056.68   254.6  2057.4   272.8 2059.04
     292 2061.77   299.3 2062.57   332.9 2064.98   448.6 2069.38   484.5 2070.16
#Mann= 7 ,-1 , 0
       0     .04       0      10    .035       0      50     .04       0
   144.5    .045       0   161.4      .1       0     220    .035       0
  388.62      .1       0
Bank Sta=144.5,161.4
XS Rating Curve= 0 ,0
Exp/Cntr=0.5,0.3

Type RM Length L Ch R = 1 ,15646   ,89.6,89.6,89.8
XS GIS Cut Line= 2
2107051.84262742 202726.223313712107245.85262742 203114.24431371
#Sta/Elev= 30
       0 2076.54      22 2075.12    40.3 2072.69      43 2071.18    48.4 2067.06
    55.7 2063.36    60.1 2061.89      66 2060.78    77.3 2059.65   113.7 2057.13
   155.5 2056.48   161.4  2056.1   168.7  2054.9   176.1 2055.24   192.2  2054.9
   197.1 2054.54   199.42053.921   202.4 2053.16   205.4 2052.95   215.42053.534
   223.7 2055.08   238.4 2054.57   245.8 2053.33   256.8 2055.05   282.7 2055.77
     312 2058.44   322.8 2059.03     356 2062.96   393.2  2066.5   433.8 2069.52
#Mann= 5 ,-1 , 0
       0     .04       0   199.4    .045       0   215.4     .04       0
     270    .035       0     370     .04       0
#XS Ineff= 2 , 0
          193.94    2065  219.19         2064.93
Permanent Ineff=
       F       F
Bank Sta=199.4,215.4
XS Rating Curve= 0 ,0
Exp/Cntr=0.5,0.3

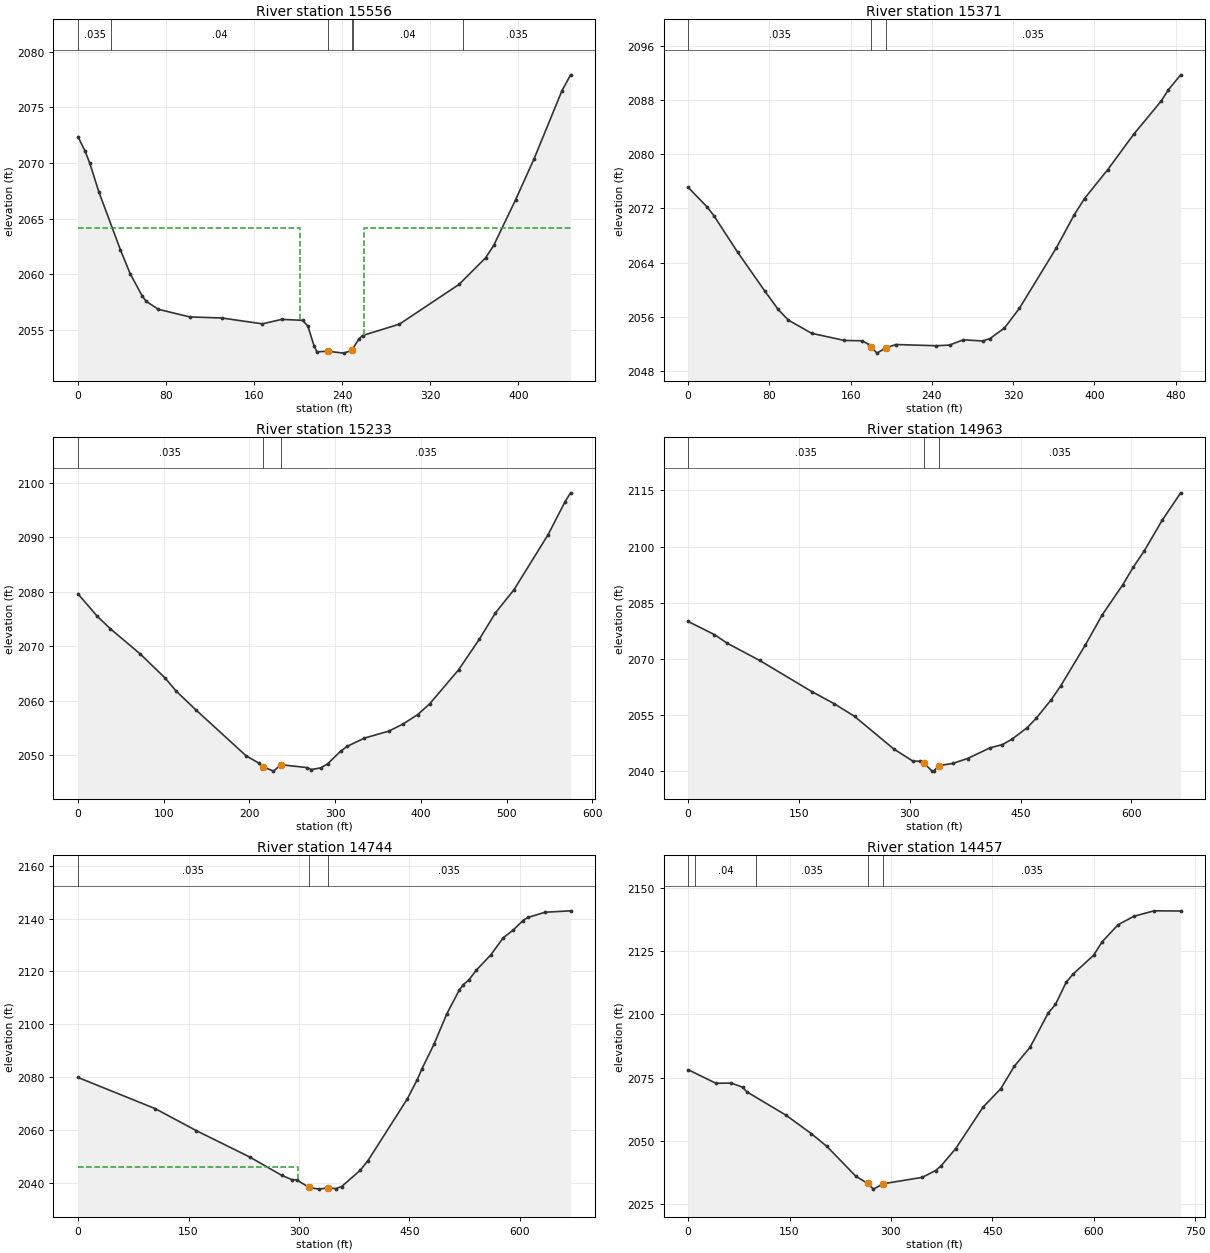
Type RM Length L Ch R = 1 ,15556   ,175.9,184.9,184.4
XS GIS Cut Line= 2
 2106962.3657778 202746.247627422107162.83109806203146.254222205
#Sta/Elev= 30
       0 2072.35     6.3 2071.09    10.6    2070      19 2067.38    38.5 2062.21
    47.3 2060.08    58.3 2058.06      62 2057.58      73 2056.87   101.5 2056.19
   130.8 2056.09   167.4 2055.57   185.2 2055.97   204.1 2055.88   208.8 2055.35
   214.5 2053.56     217 2053.06   226.7 2053.11   241.4 2052.94   248.6 2053.19
   255.3 2054.24   258.5 2054.52   291.9 2055.54     346  2059.1   370.3  2061.5
   377.6 2062.61   397.5 2066.71   414.3 2070.39   439.5 2076.47   447.4 2077.91
#Mann= 6 ,-1 , 0
       0    .035       0      30     .04       0   226.7    .045       0
   248.6    .035       0     250     .04       0     350    .035       0
#XS Ineff= 2 , 0
          202.02 2064.14   260.1          2064.2
Permanent Ineff=
       F       F
Bank Sta=226.7,248.6
XS Rating Curve= 0 ,0
Exp/Cntr=0.5,0.3

Type RM Length L Ch R = 1 ,15371   ,130.4,138,144.9
XS GIS Cut Line= 3
      2106933.67      202724.4292106919.45345753202793.452803872
2106864.51104591203204.300954247
#Sta/Elev= 30
       0  2075.1    18.6 2072.22    25.3 2070.93    48.7 2065.54    75.5  2059.8
    88.7 2057.08    98.6 2055.52   121.7 2053.56   153.9 2052.51   171.4 2052.46
   178.1  2051.9   180.1 2051.51     186 2050.64   194.6 2051.42   204.6 2051.91
   244.4 2051.73   257.5 2051.83   270.9 2052.61     290 2052.43   297.2 2052.79
   311.5 2054.35   326.1 2057.23   362.6 2066.18     380    2071   390.3 2073.45
   413.1  2077.7     439 2082.98   465.8 2087.83   472.7 2089.46     485  2091.7
#Mann= 3 ,-1 , 0
       0    .035       0   180.1    .045       0   194.6    .035       0
Bank Sta=180.1,194.6
XS Rating Curve= 0 ,0
Exp/Cntr=0.3,0.1

Type RM Length L Ch R = 1 ,15233   ,265.3,270.5,269.6
XS GIS Cut Line= 2
     2106893.306      202684.065     2106594.912      203175.275
#Sta/Elev= 30
       0 2079.62    22.5  2075.5    37.8 2073.21    72.4 2068.63   101.6 2064.19
   114.6 2061.78   137.6 2058.33   196.4 2049.88   210.6 2048.62   215.52047.938
     228 2047.11   236.72048.282   267.3 2047.76   272.1  2047.4   283.5 2047.72
   291.2 2048.45   306.5 2050.79   314.2 2051.67   334.2 2053.17   362.8 2054.46
   379.5 2055.78   396.3 2057.48   410.2 2059.44     444 2065.69   468.2  2071.3
   486.9 2076.12   508.5 2080.35   548.4 2090.47   568.2 2096.52   574.7 2098.16
#Mann= 3 ,-1 , 0
       0    .035       0   215.5    .045       0   236.7    .035       0
Bank Sta=215.5,236.7
XS Rating Curve= 0 ,0
Exp/Cntr=0.3,0.1

Type RM Length L Ch R = 1 ,14963   ,197.4,218.8,234.1
XS GIS Cut Line= 3
      2106839.92       202637.19     2106595.129      202691.877
     2106351.231      203028.785
#Sta/Elev= 30
       0 2080.01    35.6  2076.5    53.2 2074.17    96.9 2069.59   167.5 2061.27
   197.7 2058.05   225.2 2054.68   278.2 2045.99   304.1 2042.74   313.5 2042.67
   319.62042.114   329.7 2040.15   332.3 2040.05   339.22041.502     358  2042.1
   378.3 2043.42   408.6 2046.27   425.4 2047.14     438 2048.53     459 2051.66
   470.9 2054.12   491.7 2059.17   504.2 2062.78   537.3 2073.62   560.5 2081.77
   588.4 2089.82   602.5 2094.51   617.2 2098.78   641.5 2106.98   666.7 2114.35
#Mann= 3 ,-1 , 0
       0    .035       0   319.6    .045       0   339.2    .035       0
Bank Sta=319.6,339.2
XS Rating Curve= 0 ,0
Exp/Cntr=0.3,0.1

Type RM Length L Ch R = 1 ,14744   ,286.8,287.2,281.9
XS GIS Cut Line= 3
     2106820.389      202570.784     2106592.524      202587.711
     2106160.233      202504.377
#Sta/Elev= 30
       0 2079.94   104.8 2068.16   160.7 2059.83   233.2 2049.87   276.6 2042.95
     290 2041.37   296.7 2041.25   313.32038.467   326.7 2037.75   339.42038.255
   350.1 2037.94   357.9 2038.74   383.1 2044.87   393.6 2048.51     447 2071.82
   460.4 2079.06   467.1 2083.32   483.6  2092.7   500.7 2104.01   517.5 2112.92
   523.1    2115   530.6 2116.81   540.6 2120.43   560.6 2126.34   577.3 2132.73
   590.4 2135.54   604.1 2139.24   610.7 2140.38   634.1 2142.37   668.7  2142.9
#Mann= 3 ,-1 , 0
       0    .035       0   313.3    .045       0   339.4    .035       0
#XS Ineff= 2 , 0
          298.04 2046.12
Permanent Ineff=
       F       F
Bank Sta=313.3,339.4
XS Rating Curve= 0 ,0
Exp/Cntr=0.3,0.1

Type RM Length L Ch R = 1 ,14457   ,266,260.5,248.5
XS GIS Cut Line= 3
     2106875.077      202320.784     2106501.379      202314.273
     2106152.295      202378.314
#Sta/Elev= 30
       0 2078.11    41.1 2072.74    63.8 2072.82    80.5 2071.18      87 2069.33
     145 2060.07   182.2  2052.8   205.2 2047.77   247.8 2036.03   265.62033.074
   274.1 2030.84   288.52032.957   346.3  2035.5     366 2038.17   374.3 2040.07
   395.9 2046.91   436.3 2063.29   462.6 2070.62   482.6  2079.5   505.9 2086.98
   532.6  2100.5   543.4 2103.93   559.3  2112.7   569.3 2115.91   599.8 2123.39
   612.7 2128.78     636 2135.47   659.4 2138.83   689.4 2140.99   728.7 2140.92
#Mann= 5 ,-1 , 0
       0    .035       0      10     .04       0     100    .035       0
   265.6    .045       0   288.5    .035       0
Bank Sta=265.6,288.5
XS Rating Curve= 0 ,0
Exp/Cntr=0.3,0.1