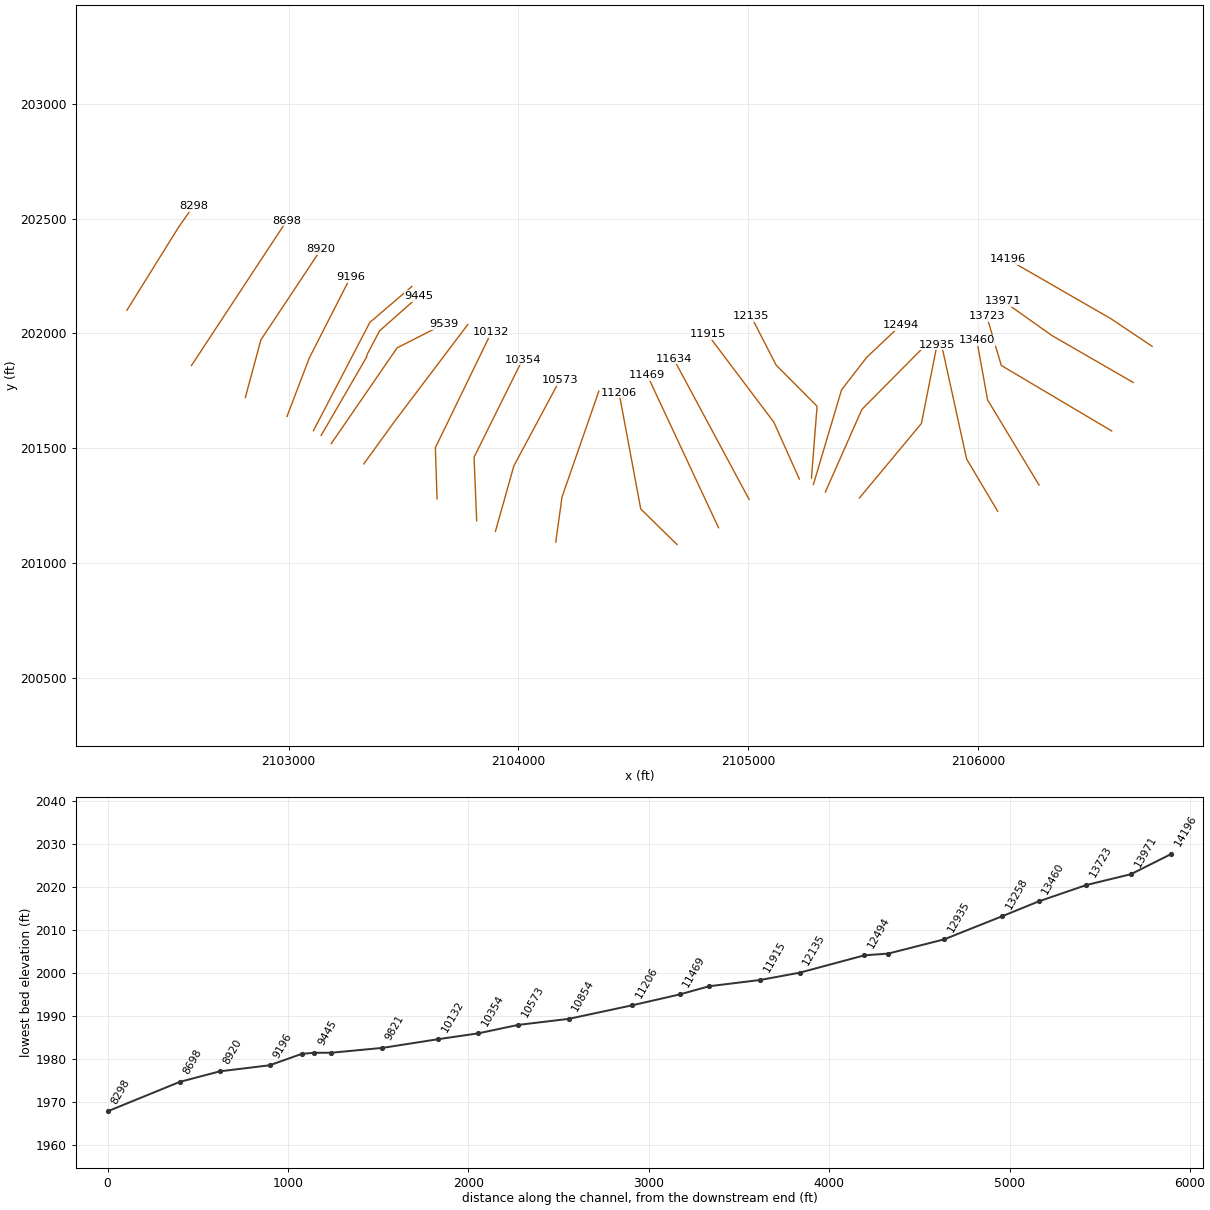
HEC-RAS study TCKTTBR.prj: TCKTTBR

--- TCKTTBR.g01 (geometry) --- (continued)

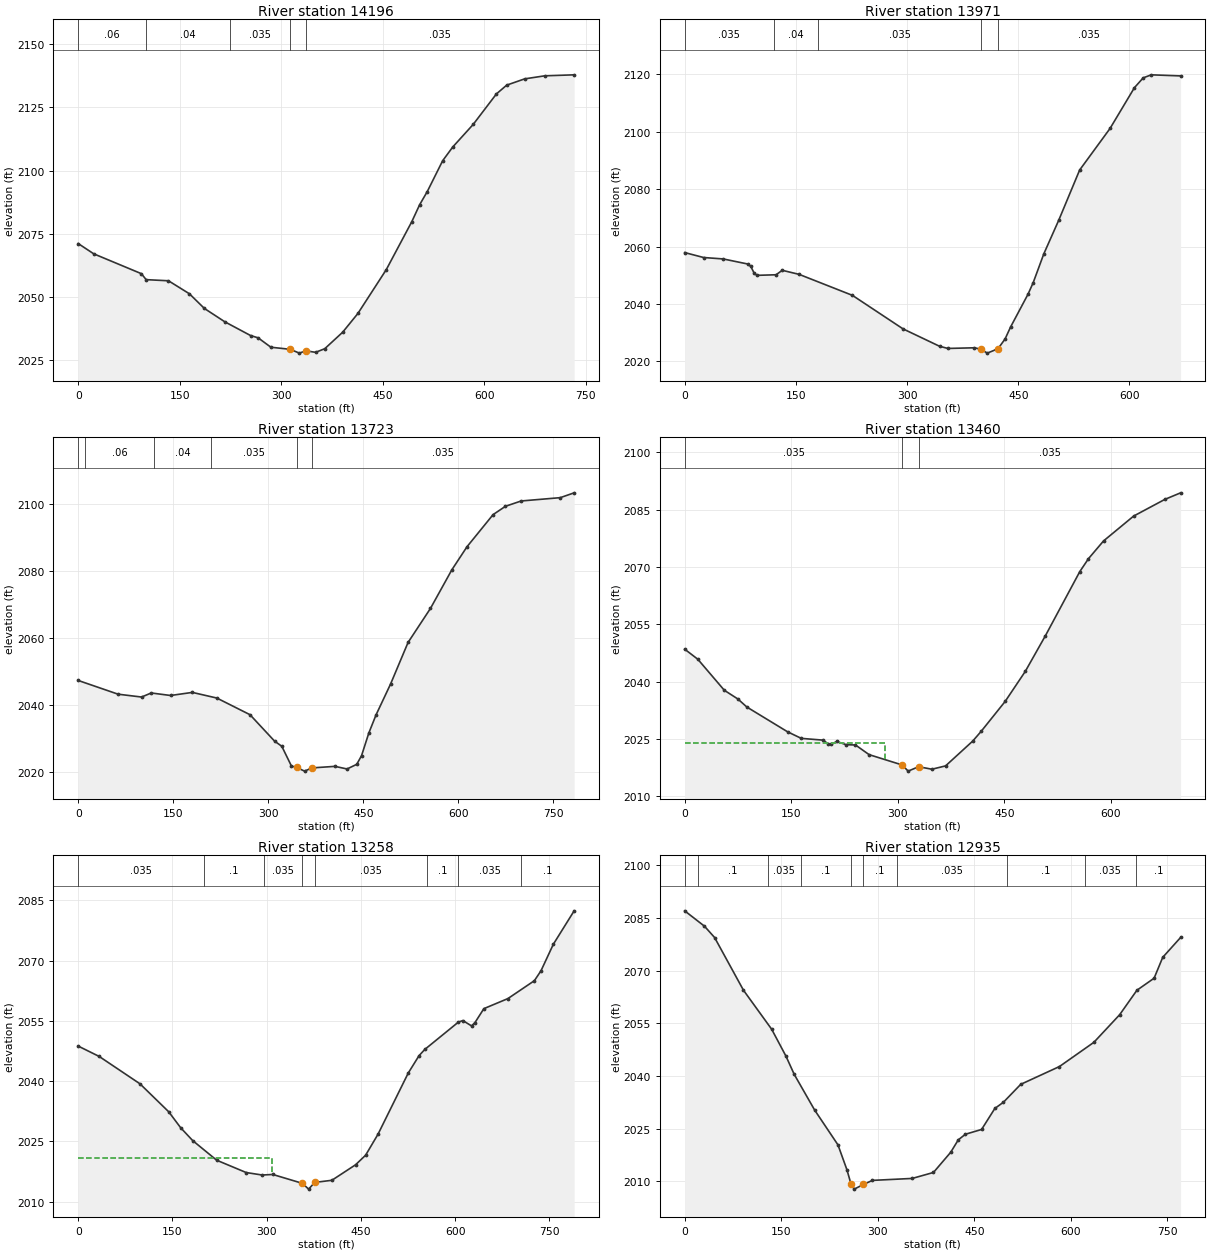
Type RM Length L Ch R = 1 ,14196   ,224.4,225.2,222.8
XS GIS Cut Line= 3
     2106757.889      201943.179     2106579.504      202062.971
     2106130.909      202321.796
#Sta/Elev= 30
       0 2071.04      23 2066.96    93.3  2059.1   100.4 2056.73   133.4 2056.28
   164.3 2051.13   186.4 2045.32   216.5 2040.04   254.7 2034.57   265.8 2033.67
   284.7 2029.94   313.22029.113   326.8  2027.6   336.22028.511   350.8 2027.92
   364.3 2029.35   390.8  2035.9   413.3 2043.34   455.2  2060.7     493 2079.76
   504.5 2086.43   515.8 2091.67   538.5 2103.87   553.6 2109.38   583.6 2118.26
     618 2130.38   633.2 2133.85   659.7 2136.33   689.5 2137.54   732.8 2137.93
#Mann= 5 ,-1 , 0
       0     .06       0     100     .04       0  224.88    .035       0
   313.2    .045       0   336.2    .035       0
Bank Sta=313.2,336.2
XS Rating Curve= 0 ,0
Exp/Cntr=0.3,0.1

Type RM Length L Ch R = 1 ,13971   ,246.7,248,247.1
XS GIS Cut Line= 3
     2106675.589      201785.935     2106320.856      201990.873
     2106109.452      202141.096
#Sta/Elev= 30
       0 2057.89    25.5 2056.17      52 2055.67    84.8 2053.92    89.2 2053.06
    93.7 2050.74    97.5 2049.96   123.3 2050.16   131.6 2051.72   154.5 2050.29
   226.3 2042.99   294.5 2031.33   343.8 2025.27   355.1 2024.51   390.9 2024.74
   399.82024.217   408.2 2022.88   422.62024.397   432.2 2027.81   439.6 2031.96
   463.2 2043.42   470.2 2047.46   484.5 2057.47   504.7 2069.22   532.8 2086.63
   573.8  2101.1   606.7  2115.3   618.5 2118.71   629.4 2119.77     669 2119.39
#Mann= 5 ,-1 , 0
       0    .035       0     120     .04       0     180    .035       0
   399.8    .045       0   422.6    .035       0
Bank Sta=399.8,422.6
XS Rating Curve= 0 ,0
Exp/Cntr=0.3,0.1

Type RM Length L Ch R = 1 ,13723   ,267.7,263.2,248.2
XS GIS Cut Line= 3
     2106582.035      201574.436     2106101.639      201859.846
     2106037.837       202074.69
#Sta/Elev= 30
       0 2047.38    62.9 2043.29     100 2042.44   115.3 2043.65   145.8  2042.9
   180.2 2043.82   218.8 2042.14   271.2 2037.17   309.9 2029.31   321.4 2027.75
   336.6 2021.87   344.82021.448   357.3 2020.35   369.22021.313   405.3 2021.77
   424.4 2020.99   439.7 2022.38   447.3 2024.97   458.7 2031.68   470.2 2037.13
   493.1 2046.32   520.7 2058.71   556.1 2068.87   589.8 2080.36   613.8 2087.26
   654.9 2096.82   674.5 2099.31   699.3 2100.89     761 2101.88   782.9 2103.32
#Mann= 6 ,-1 , 0
       0    .035       0      10     .06       0     120     .04       0
     210    .035       0   344.8    .045       0   369.2    .035       0
Bank Sta=344.8,369.2
XS Rating Curve= 0 ,0
Exp/Cntr=0.3,0.1

Type RM Length L Ch R = 1 ,13460   ,202.2,201.9,191.8
XS GIS Cut Line= 3
     2106265.702      201339.013     2106041.743      201710.107
     2105994.868      201970.523
#Sta/Elev= 30
       0 2048.47    18.5 2045.83    55.8 2037.71    74.9 2035.43    87.5 2033.33
   144.8 2026.85   164.1 2025.13   194.7 2024.67   202.4 2023.65   206.2 2023.55
   213.9 2024.33   227.3 2023.47   240.4  2023.4   259.6 2020.87   306.32018.161
   314.5 2016.56   329.22017.711     348 2017.06   367.2 2017.93   405.5 2024.44
   417.3 2026.97   451.1 2034.81   479.3 2042.63   507.6 2051.95   556.1 2068.76
   568.3 2072.14   589.5 2076.78   631.9 2083.29   675.8 2087.65     698 2089.37
#Mann= 3 ,-1 , 0
       0    .035       0   306.3    .045       0   329.2    .035       0
#XS Ineff= 2 , 0
           281.5 2023.99
Permanent Ineff=
       F       F
Bank Sta=306.3,329.2
XS Rating Curve= 0 ,0
Exp/Cntr=0.3,0.1

Type RM Length L Ch R = 1 ,13258   ,328.6,322.9,301.7
XS GIS Cut Line= 3
     2106086.014      201224.429     2105950.597      201452.294
     2105838.429       201964.56
#Sta/Elev= 30
       0 2048.73    33.4 2046.15    98.3 2039.34   144.1 2032.37   163.1  2028.4
   182.2 2025.21   220.4 2020.32   267.4 2017.25   292.9 2016.63   309.7 2016.77
   356.82014.565   366.8 2013.12   376.52014.787   403.8 2015.32   441.5 2019.18
   457.5 2021.56   477.3  2026.8   525.4 2042.02   542.6 2046.35   551.7 2047.89
   605.3 2054.71   612.3 2055.08   626.1 2053.76   631.6 2054.58   645.8 2058.05
     684 2060.55   726.2 2065.01   736.7 2067.47   756.4 2074.09   789.5  2082.4
#Mann= 8 ,-1 , 0
       0    .035       0     200      .1       0  295.07    .035       0
   356.8    .045       0   376.5    .035       0  555.07      .1       0
  605.07    .035       0  705.07      .1       0
#XS Ineff= 2 , 0
          308.17 2020.75
Permanent Ineff=
       F       F
Bank Sta=356.8,376.5
XS Rating Curve= 0 ,0
Exp/Cntr=0.3,0.1

Type RM Length L Ch R = 1 ,12935   ,299.5,309.3,278.6
XS GIS Cut Line= 3
     2105484.452      201283.023     2105753.983      201607.242
     2105821.691       201949.69
#Sta/Elev= 30
       0 2087.07    30.8 2082.68    46.5 2079.46    91.4 2064.42   135.2 2053.31
   157.4 2045.64   170.2 2040.46   201.9 2030.29   238.2 2020.35   252.1 2013.27
   258.3 2009.31   263.5 2007.73   277.8 2009.06   291.7 2010.22   353.6 2010.78
   386.6 2012.48   413.4 2018.23   425.2 2021.78   436.3 2023.38   461.4 2024.74
     482 2030.73   495.4 2032.51   522.2  2037.6   582.4 2042.68   635.9 2049.58
     676 2057.46   702.8 2064.43   729.5 2067.86   742.9 2073.81   770.7 2079.48
#Mann= 10 ,-1 , 0
       0    .035       0      20      .1       0     130    .035       0
     180      .1       0   258.3    .045       0   277.8      .1       0
     330    .035       0  501.62      .1       0  621.62    .035       0
  701.62      .1       0
Bank Sta=258.3,277.8
XS Rating Curve= 0 ,0
Exp/Cntr=0.3,0.1

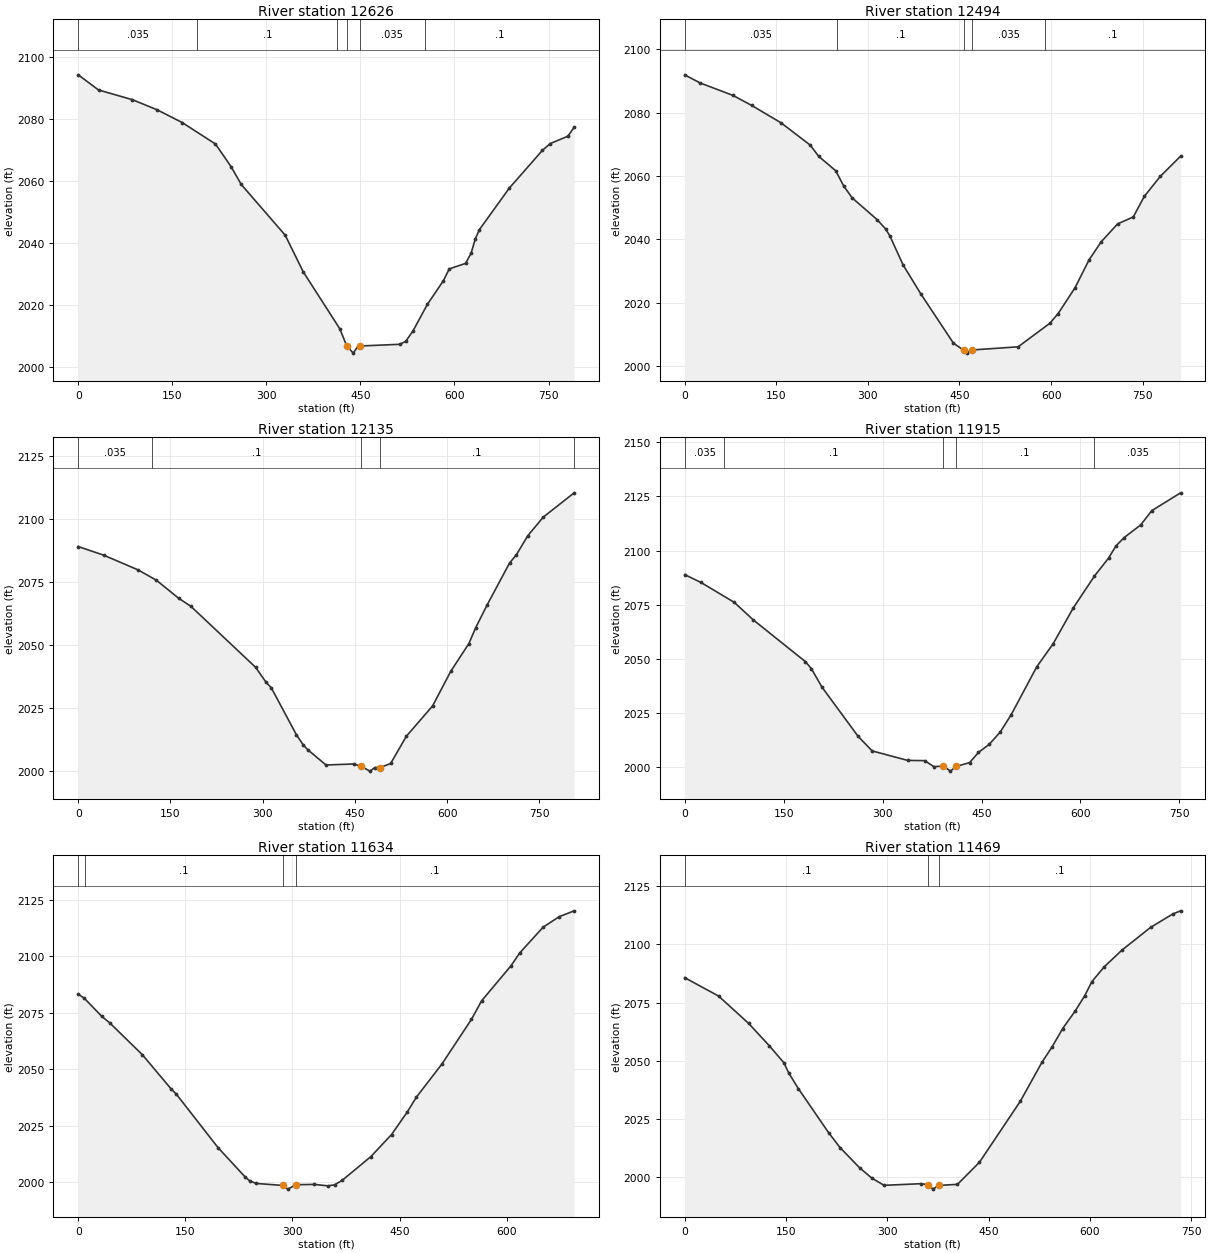
Type RM Length L Ch R = 1 ,12626   ,129.1,131.4,132.5
XS GIS Cut Line= 3
     2105336.129      201308.748     2105494.868       201668.44
     2105774.816      201950.992
#Sta/Elev= 30
       0 2094.27    32.4 2089.38    86.2 2086.26   125.7    2083   165.7 2078.88
   218.9 2071.94     244 2064.56     260 2058.88   330.1  2042.5   358.8  2030.7
   417.2 2012.28   428.32006.729   438.6 2004.43   445.5 2006.52   448.62006.723
   512.8 2007.28   522.1  2008.2   533.8 2011.56   556.7 2020.13   582.4 2027.82
   591.7 2031.63   617.7 2033.39   626.5 2036.67   633.4 2041.39   639.8  2044.3
   687.6 2057.73   740.2 2069.87   752.8 2072.08   780.8 2074.45   790.9 2077.32
#Mann= 6 ,-1 , 0
       0    .035       0     190      .1       0  413.16    .035       0
   428.3    .045       0   448.6    .035       0  553.16      .1       0
Bank Sta=428.3,448.6
XS Rating Curve= 0 ,0
Exp/Cntr=0.3,0.1

Type RM Length L Ch R = 1 ,12494   ,309.9,358.9,342.6
XS GIS Cut Line= 4
     2105283.877      201341.3822105406.60571673201754.215548028
2105516.38128354  201895.7971759     2105663.273      202034.789
#Sta/Elev= 30
       02091.946   25.252089.383  79.0642085.452 109.8692082.261 157.7872076.794
 205.7052069.729 219.3962066.204 247.201 2061.67 260.4692056.813  274.162053.106
 315.2332046.179 328.9242043.287 335.7692041.149 357.6872031.886  387.112022.608
 440.1042007.185  456.712004.952 461.8622004.037 471.2162005.043 546.0452006.035
  597.862013.458 611.5072016.535 639.0262024.637 662.253 2033.53 681.9872039.195
  708.982044.875 734.5212047.044 752.5882053.544 778.6042059.838 812.071 2066.26
#Mann= 5 ,-1 , 0
       0    .035       0     250      .1       0  456.71    .045       0
 471.216    .035       0  590.69      .1       0
Bank Sta=456.71,471.216
XS Rating Curve= 0 ,0
Exp/Cntr=0.3,0.1

Type RM Length L Ch R = 1 ,12135   ,191.5,220,185.5
XS GIS Cut Line= 4
 2105275.4453255201369.0651743772105299.95366263201682.215255517
2105121.57585164201861.697258301 2105012.4253255202074.794174377
#Sta/Elev= 30
       0 2089.22    41.7 2085.77    97.6 2079.92   127.2 2075.83   163.4 2068.67
   183.2 2065.49   288.5 2041.25   304.9 2035.51   314.1 2033.07     355  2014.4
     366  2010.4   373.6 2008.45     403 2002.44   447.8 2002.84   460.42001.892
   474.3    2000   482.6 2001.41   490.62001.382   508.2 2003.05   533.7 2013.86
   576.4 2025.92   605.9 2039.64   635.4 2050.69   646.4 2056.94   664.9 2065.95
   701.7 2082.74   712.4 2085.86   731.2 2093.51   756.2 2100.87   806.6 2110.56
#Mann= 5 ,-1 , 0
       0    .035       0     120      .1       0   460.4    .045       0
   490.6      .1       0  806.58    .035       0
Bank Sta=460.4,490.6
XS Rating Curve= 0 ,0
Exp/Cntr=0.3,0.1

Type RM Length L Ch R = 1 ,11915   ,276.3,281.5,271.4
XS GIS Cut Line= 3
     2105222.733      201365.054     2105112.056       201612.45
     2104822.993      201996.565
#Sta/Elev= 30
       0 2088.89    24.7 2085.28    75.1 2076.12   103.7  2068.1   182.9 2048.81
     192 2045.58     208 2037.09   262.7 2014.41   284.2 2007.62   338.1 2003.24
   363.9 2003.14   377.9 2000.31     392 2000.71   402.8  1998.3   411.5 2000.47
   431.8 2002.21   445.4 2006.91   461.9 2010.72   478.3  2016.3   495.1 2024.39
   533.8 2046.45   558.4 2056.94   588.8 2073.39   621.1 2088.21   642.5 2096.49
   653.8 2102.13   666.1 2105.95   691.2 2111.78   708.2 2118.41   751.8  2126.6
#Mann= 5 ,-1 , 0
       0    .035       0      60      .1       0     392    .045       0
   411.5      .1       0  621.02    .035       0
Bank Sta=392,411.5
XS Rating Curve= 0 ,0
Exp/Cntr=0.3,0.1

Type RM Length L Ch R = 1 ,11634   ,163.8,164.5,161.5
XS GIS Cut Line= 2
     2105003.983      201276.513     2104675.858      201888.492
#Sta/Elev= 30
       0 2083.23     8.5 2081.44      33 2073.39    44.2 2070.48    89.9 2056.38
   129.8 2041.35   137.3 2038.97   195.9 2015.19   234.1 2002.11   240.1 2000.52
   248.9 1999.38   286.2 1998.49   293.6 1996.85   304.61998.809   330.8 1998.94
   349.5  1998.3   358.9 1998.75   369.5 2000.72   409.8 2011.27   438.7 2021.03
   460.7 2031.01   473.6 2037.65   509.5 2052.39   550.5 2072.03   564.9 2080.32
   606.1 2095.85   618.2 2101.51     651 2112.92   673.3 2117.53   694.4 2120.15
#Mann= 4 ,-1 , 0
       0    .035       0      10      .1       0   286.2    .045       0
   304.6      .1       0
Bank Sta=286.2,304.6
XS Rating Curve= 0 ,0
Exp/Cntr=0.3,0.1

Type RM Length L Ch R = 1 ,11469   ,261,263.6,253.5
XS GIS Cut Line= 2
     2104871.191      201152.924     2104560.609       201818.27
#Sta/Elev= 30
       0 2085.73    50.1 2077.85    94.5 2066.15   125.1 2056.56   146.8 2049.24
     154 2044.85   168.5 2038.02     213 2019.22   230.1 2012.76     259  2004.1
     277 1999.69   295.2 1996.57   349.5 1997.27   360.4 1996.89   367.6 1994.94
   375.9 1996.53   403.9 1996.99   436.4 2006.45   496.9 2032.65   528.9 2049.36
   543.8 2055.93   559.5  2063.8   578.3 2071.47   592.1 2077.86     603 2084.06
   621.1 2090.35   647.4 2097.55   689.9 2107.32   722.5 2113.04   734.3 2114.42
#Mann= 3 ,-1 , 0
       0      .1       0   360.4    .045       0   375.9      .1       0
Bank Sta=360.4,375.9
XS Rating Curve= 0 ,0
Exp/Cntr=0.3,0.1

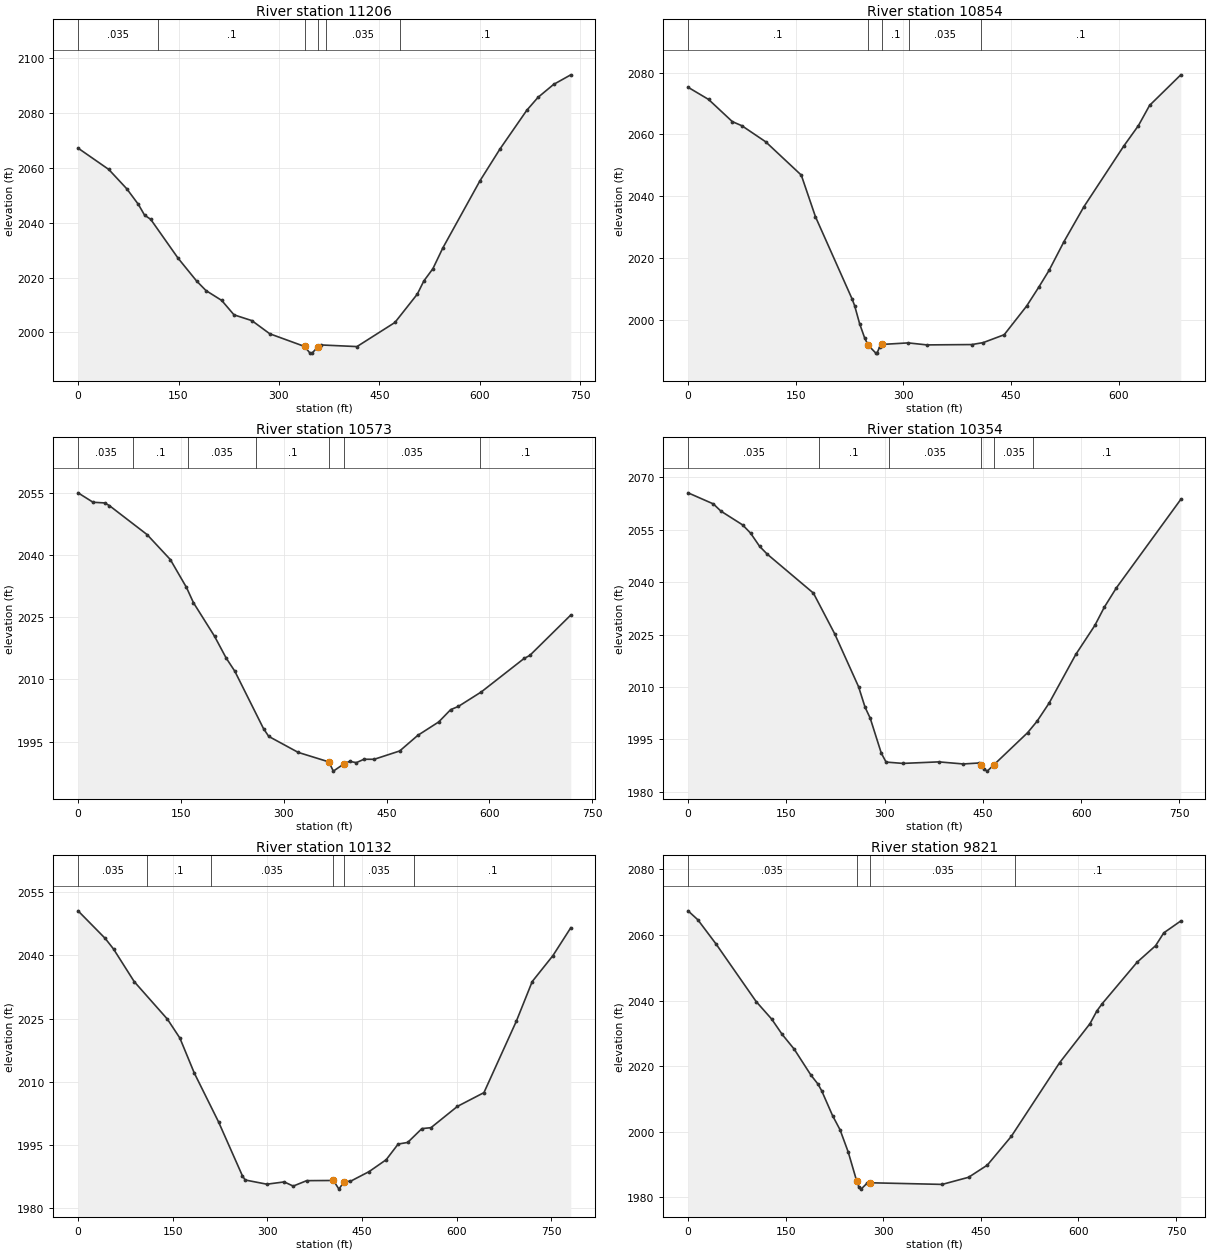
Type RM Length L Ch R = 1 ,11206   ,340.8,352,331.4
XS GIS Cut Line= 3
     2104690.181      201079.898     2104532.629      201234.846
2104438.29303264201740.982947689
#Sta/Elev= 30
       0 2067.23    45.9 2059.44    72.8 2052.38    90.1 2046.69    99.3 2042.78
   108.5 2041.24   149.3 2027.08   176.9 2018.77   191.1 2015.23   214.5 2011.65
   232.9 2006.38   259.6 2004.27   286.3 1999.47   338.2 1994.85   346.4 1992.41
   349.7 1992.47   357.71994.587   363.1 1995.39   416.5  1994.8   473.2  2003.6
   506.6 2013.94   516.4 2018.76   529.9 2023.23   544.8 2030.83     600 2055.23
     630 2066.89   670.1 2081.04   686.8 2085.74   710.1 2090.47   735.8 2093.98
#Mann= 6 ,-1 , 0
       0    .035       0     120      .1       0   338.2    .045       0
   357.7      .1       0  370.98    .035       0  480.98      .1       0
Bank Sta=338.2,357.7
XS Rating Curve= 0 ,0
Exp/Cntr=0.3,0.1

Type RM Length L Ch R = 1 ,10854   ,277.8,280.1,267.9
XS GIS Cut Line= 3
     2104162.837      201090.315     2104190.181      201286.929
      2104350.43       201748.08
#Sta/Elev= 30
       0 2075.24    28.6  2071.3    61.7 2064.13      75  2062.8   108.1 2057.62
   157.8 2046.83   177.6 2033.35   228.7 2006.74   232.2 2004.57   239.1 1998.79
   246.1 1994.18   250.91991.859   261.7 1989.26   263.4 1989.27   266.9  1991.2
   270.1 1992.07   306.8 1992.57   332.9 1991.92   395.4 1992.03   411.2 1992.65
   440.6 1995.21   471.8 2004.46   488.6 2010.52   503.1 2016.01   523.9 2025.31
   551.7 2036.61   607.1 2056.18   627.7 2062.85   643.2 2069.37   686.7 2079.26
#Mann= 5 ,-1 , 0
       0      .1       0   250.9    .045       0   270.1      .1       0
  308.51    .035       0  408.51      .1       0
Bank Sta=250.9,270.1
XS Rating Curve= 0 ,0
Exp/Cntr=0.3,0.1

Type RM Length L Ch R = 1 ,10573   ,215.3,219.5,208.3
XS GIS Cut Line= 3
     2103900.325      201136.942     2103980.545      201422.346
     2104179.764      201794.742
#Sta/Elev= 30
       0  2055.1    21.9 2052.82    38.9 2052.66    45.7 2052.01   100.7 2045.01
   134.6 2038.98   158.2 2032.23   168.4 2028.54   199.1 2020.45   216.1 2015.17
   228.7    2012   270.6 1998.11   278.2 1996.25   321.1 1992.39   365.9 1990.09
   372.4 1987.86   388.1 1989.63   396.2 1990.22     406 1989.91   417.1 1990.73
     432 1990.72   469.2 1992.73   495.6  1996.5   526.1 1999.74   543.6 2002.72
   554.8 2003.49   588.3    2007   650.7 2015.08     659 2015.81   718.8 2025.57
#Mann= 7 ,-1 , 0
       0    .035       0      80      .1       0     160    .035       0
     260      .1       0   365.9    .045       0   388.1    .035       0
  586.46      .1       0
Bank Sta=365.9,388.1
XS Rating Curve= 0 ,0
Exp/Cntr=0.3,0.1

Type RM Length L Ch R = 1 ,10354   ,209.7,222,204.2
XS GIS Cut Line= 3
      2103818.79      201183.316     2103807.368      201460.107
     2104018.306      201885.888
#Sta/Elev= 30
       0 2065.55    38.6 2062.38    50.2 2060.31    83.3 2056.37    95.4 2054.03
   109.3 2050.22   120.9    2048   191.4 2036.85   223.7 2025.27   260.3 2010.07
   270.2 2004.21   278.1 2001.05     295 1991.06   302.3  1988.5     328 1988.12
   382.9 1988.56   420.1 1987.96   443.4 1988.23   446.51987.798   451.9 1986.44
   456.8 1985.91   467.1 1987.76   518.4 1996.92   532.7 2000.16   551.3 2005.41
   591.9  2019.3     621  2027.6   635.5 2032.83   653.8 2038.33   752.2 2063.67
#Mann= 6 ,-1 , 0
       0    .035       0     200      .1       0  307.03    .035       0
   446.5    .045       0   467.1    .035       0  527.03      .1       0
Bank Sta=446.5,467.1
XS Rating Curve= 0 ,0
Exp/Cntr=0.3,0.1

Type RM Length L Ch R = 1 ,10132   ,297,310.6,295
XS GIS Cut Line= 3
     2103646.363      201278.961     2103638.965      201501.513
     2103882.455      202003.641
#Sta/Elev= 30
       0 2050.54      43    2044    56.2 2041.49      89 2033.75   141.6 2024.85
   161.3 2020.38   184.2 2012.07   222.7 2000.46   260.2 1987.78   264.7 1986.72
   299.1 1985.72   326.7 1986.26   340.9 1985.27   362.3 1986.56   404.7  1986.6
   413.3 1984.55   421.81986.358   431.6 1986.41   461.2 1988.71   488.2 1991.52
   507.2 1995.24   522.3 1995.62   544.8  1998.9   559.2 1999.12   601.1 2004.17
   643.1 2007.43   694.5 2024.39   719.6 2033.77   752.4 2039.92   780.7 2046.53
#Mann= 6 ,-1 , 0
       0    .035       0     110      .1       0     210    .035       0
   404.7    .045       0   421.8    .035       0  532.67      .1       0
Bank Sta=404.7,421.8
XS Rating Curve= 0 ,0
Exp/Cntr=0.3,0.1

Type RM Length L Ch R = 1 ,9821    ,275.5,282.6,278.3
XS GIS Cut Line= 3
     2103327.768        201431.2     2103464.486      201620.002
     2103780.105       202038.42
#Sta/Elev= 30
       0 2067.34    15.1  2064.6    43.3 2057.16   104.6  2039.7   128.5 2034.35
   144.7 2029.66   163.1 2025.19   188.9 2017.25   199.7 2014.53   205.4 2012.48
     222 2004.96   233.6  2000.6   246.2 1993.79   259.3  1984.9   262.6 1983.07
   265.9 1982.52   274.9 1984.28   279.31984.461   390.5 1983.96   431.1 1986.13
   459.9 1989.84   496.8 1998.61     571 2021.05   617.7 2032.96   628.3 2036.85
   636.4 2039.03     690 2051.66   718.5 2056.71   731.1 2060.63   757.2 2064.25
#Mann= 4 ,-1 , 0
       0    .035       0   259.3    .045       0   279.3    .035       0
  503.11      .1       0
Bank Sta=259.3,279.3
XS Rating Curve= 0 ,0
Exp/Cntr=0.3,0.1

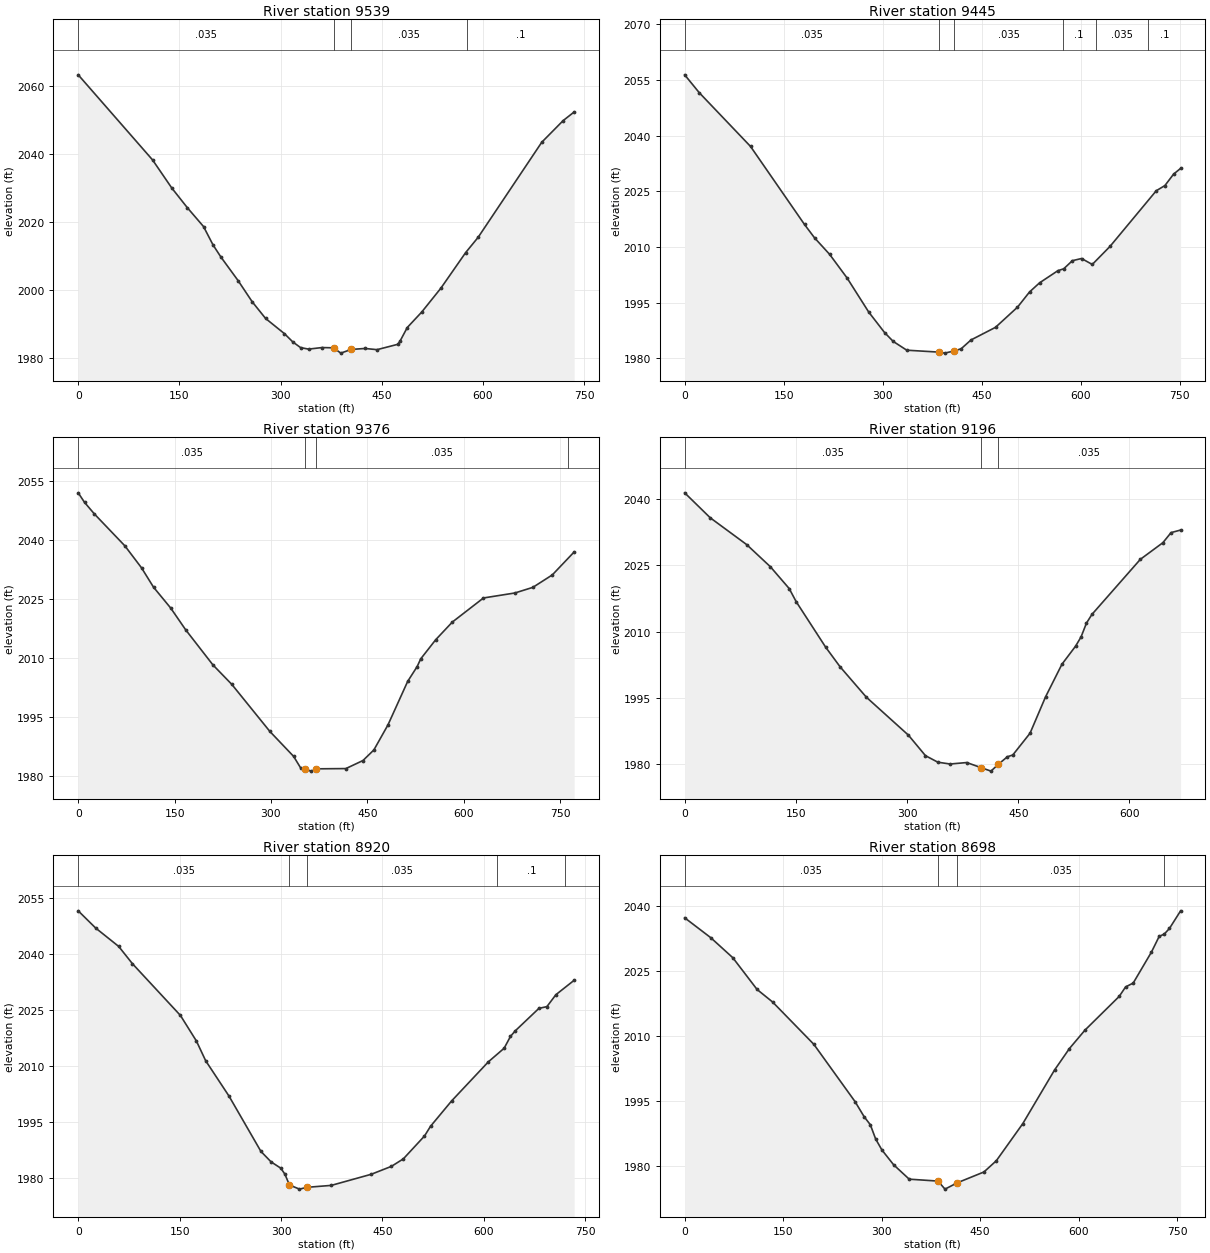
Type RM Length L Ch R = 1 ,9539    ,91.3,93.8,95.8
XS GIS Cut Line= 3
      2103186.01      201519.419     2103472.299      201936.409
     2103676.726      202040.575
#Sta/Elev= 30
       0 2063.23   110.3 2038.19   138.6 2029.98   161.7 2024.18   185.8 2018.61
   199.9  2013.2   211.7 2009.61   237.1  2002.7     258 1996.48   277.8 1991.59
   305.8 1987.11   318.2 1984.68   329.7 1983.02   341.5 1982.58   361.5 1983.04
   378.51982.958   389.3  1981.4   404.61982.484   425.2 1982.77     443 1982.42
   473.7 1983.99   476.9 1984.86   487.8 1988.93   509.2 1993.47   537.6 2000.49
   574.4 2010.97   592.9 2015.46   687.2 2043.41   718.9 2049.77   735.2 2052.31
#Mann= 4 ,-1 , 0
       0    .035       0   378.5    .045       0   404.6    .035       0
  575.81      .1       0
Bank Sta=378.5,404.6
XS Rating Curve= 0 ,0
Exp/Cntr=0.3,0.1

Type RM Length L Ch R = 1 ,9445    ,64.3,69.4,68.3
XS GIS Cut Line= 5
2103142.25161361201555.323098298 2103340.9158162 201898.49137216
2103341.35145739201906.3329136822103396.31706287202010.750418739
2103567.64183813  202162.4015356
#Sta/Elev= 30
       0 2056.38    21.9  2051.6    99.8 2037.07   181.5 2016.05   196.7 2012.45
   219.5 2008.01     246 2001.63   278.8 1992.44   302.8 1986.92   315.9 1984.53
   336.4 1982.17   385.3 1981.65   393.8 1981.38   408.6 1981.98   418.8 1982.56
   433.7 1984.93   470.8 1988.33   504.1 1993.76   522.4 1997.87   537.6 2000.33
   565.3  2003.6   574.1  2004.1   587.2 2006.29   601.1 2006.88   617.4 2005.28
   644.2 2010.13   714.3 2025.14   727.4 2026.54   740.6 2029.63   751.2 2031.17
#Mann= 6 ,-1 , 0
       0    .035       0   385.3    .045       0   408.6    .035       0
  572.38      .1       0  622.38    .035       0  702.38      .1       0
Bank Sta=385.3,408.6
XS Rating Curve= 0 ,0
Exp/Cntr(USF)=0,0
Exp/Cntr=0.3,0.1

Type RM Length L Ch R = 1 ,9376    ,177.7,179.2,180.1
XS GIS Cut Line= 3
     2103108.486        201575.82103353.93476031202047.453539314
     2103536.383      202203.701
#Sta/Elev= 30
       0 2052.04     9.8 2049.62    25.1 2046.67    72.7 2038.52    98.6 2032.92
   117.2 2028.01     144 2022.68   167.2 2017.16   209.6 2008.22   239.1 2003.24
   298.3 1991.26   335.3  1984.9   346.4 1981.91   352.6 1981.61   362.9 1981.15
   370.81981.737   416.6  1981.8   443.2 1983.85   460.2 1986.55   482.1 1992.92
   512.8 2004.01   527.6  2007.8   533.1 2009.75   556.4 2014.62   582.3 2019.12
   630.8 2025.26   679.7 2026.53   707.6 2027.96   737.9 2031.13   771.9 2036.98
#Mann= 4 ,-1 , 0
       0    .035       0   352.6    .045       0   370.8    .035       0
   761.7      .1       0
Bank Sta=352.6,370.8
XS Rating Curve= 0 ,0
Exp/Cntr=0.3,0.1

Type RM Length L Ch R = 1 ,9196    ,269.2,276.3,262.5
XS GIS Cut Line= 3
     2102993.362      201637.547     2103090.164      201891.792
     2103270.286      202245.524
#Sta/Elev= 30
       0 2041.44    34.5 2035.79    83.7 2029.72   115.6 2024.72     141 2019.78
   150.4 2016.82   190.1 2006.54   209.6 2002.09   245.1  1995.2   301.8 1986.62
   324.8 1981.98   341.5  1980.5     358 1980.09   380.5 1980.42     400 1979.26
   413.2 1978.48   422.91979.995   435.3 1981.73   442.6 1982.13   465.9 1987.06
   486.8 1995.28   508.9 2002.66   527.3 2006.75   534.7 2008.84     542 2011.97
   549.4 2013.94   614.7  2026.4   645.1 2030.16   656.1 2032.44     669 2033.02
#Mann= 3 ,-1 , 0
       0    .035       0     400    .045       0   422.9    .035       0
Bank Sta=400,422.9
XS Rating Curve= 0 ,0
Exp/Cntr=0.3,0.1

Type RM Length L Ch R = 1 ,8920    ,219,222.1,218.7
XS GIS Cut Line= 3
     2102812.143      201720.263     2102879.851      201971.565
      2103141.57      202366.096
#Sta/Elev= 30
       0 2051.57    25.9 2046.95    59.9 2042.04    80.2 2037.42   151.2 2023.57
   174.8 2016.74   188.6 2011.43     223    2002   270.3 1987.17   285.3 1984.37
   299.7 1982.68   305.8 1981.07   312.51978.182   327.3 1977.07   338.61977.557
   374.4 1978.07   433.6 1981.05   463.4 1983.17     481 1985.17   512.3 1991.29
   521.2 1993.89   552.4 2000.68   606.8 2011.15   630.1 2014.78   639.5 2017.96
   646.6 2019.45   681.6 2025.46   693.4 2025.93   706.7 2029.12   733.7 2032.98
#Mann= 5 ,-1 , 0
       0    .035       0   312.5    .045       0   338.6    .035       0
  620.26      .1       0  720.26    .035       0
Bank Sta=312.5,338.6
XS Rating Curve= 0 ,0
Exp/Cntr=0.3,0.1

Type RM Length L Ch R = 1 ,8698    ,393.7,400,389.9
XS GIS Cut Line= 2
     2102577.838      201859.757     2102992.609      202491.134
#Sta/Elev= 30
       0  2037.3    39.6 2032.72    73.3 2028.08   110.3 2020.74   133.9 2017.85
   196.7 2008.08   259.5 1994.84   273.3 1991.36   282.8 1989.49   290.9  1986.2
   300.4 1983.67   318.3 1980.24     342 1976.92   385.91976.477   396.5 1974.62
   415.31976.088   455.8 1978.58   474.7 1981.18     515 1989.75   563.3 2002.12
     586 2007.09   609.7 2011.35   661.9 2019.15   671.6 2021.33   683.2 2022.23
   710.9 2029.36   722.7 2032.99   730.6 2033.56   738.4 2034.84   755.4 2038.91
#Mann= 4 ,-1 , 0
       0    .035       0   385.9    .045       0   415.3    .035       0
     730      .1       0
Bank Sta=385.9,415.3
XS Rating Curve= 0 ,0
Exp/Cntr=0.3,0.1

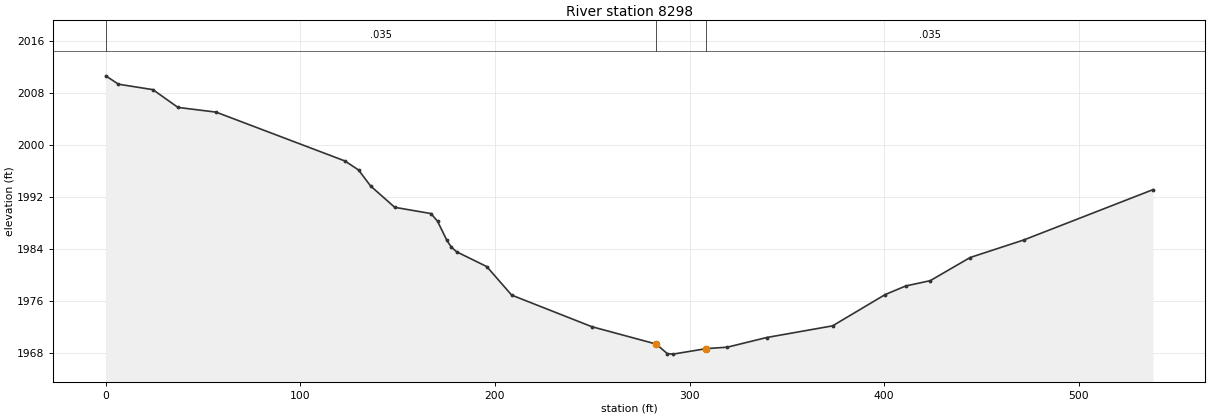
Type RM Length L Ch R = 1 ,8298    ,139.2,139.8,136.1
XS GIS Cut Line= 3
2102296.93956631202100.6300426762102520.07066608 202459.66772064
2102586.09348992202554.445283156
#Sta/Elev= 30
       0  2010.7     6.5 2009.41    24.2 2008.57    37.1 2005.83    56.7  2005.1
   122.9 1997.57   129.9 1996.18   136.1 1993.71   148.5 1990.42   167.1 1989.46
   170.5 1988.27   175.3 1985.32   177.6 1984.28   180.3 1983.56   195.8 1981.28
   208.6 1976.88   249.8 1972.01   282.91969.329   288.5 1967.87   291.5 1967.78
   308.61968.628   319.4 1968.85   339.6 1970.34   373.5 1972.14   400.5 1976.96
   411.1 1978.29   423.7 1979.11   444.2 1982.68   471.7 1985.38   538.2 1993.15
#Mann= 3 ,-1 , 0
       0    .035       0   282.9    .045       0   308.6    .035       0
Bank Sta=282.9,308.6
XS Rating Curve= 0 ,0
Exp/Cntr=0.5,0.3