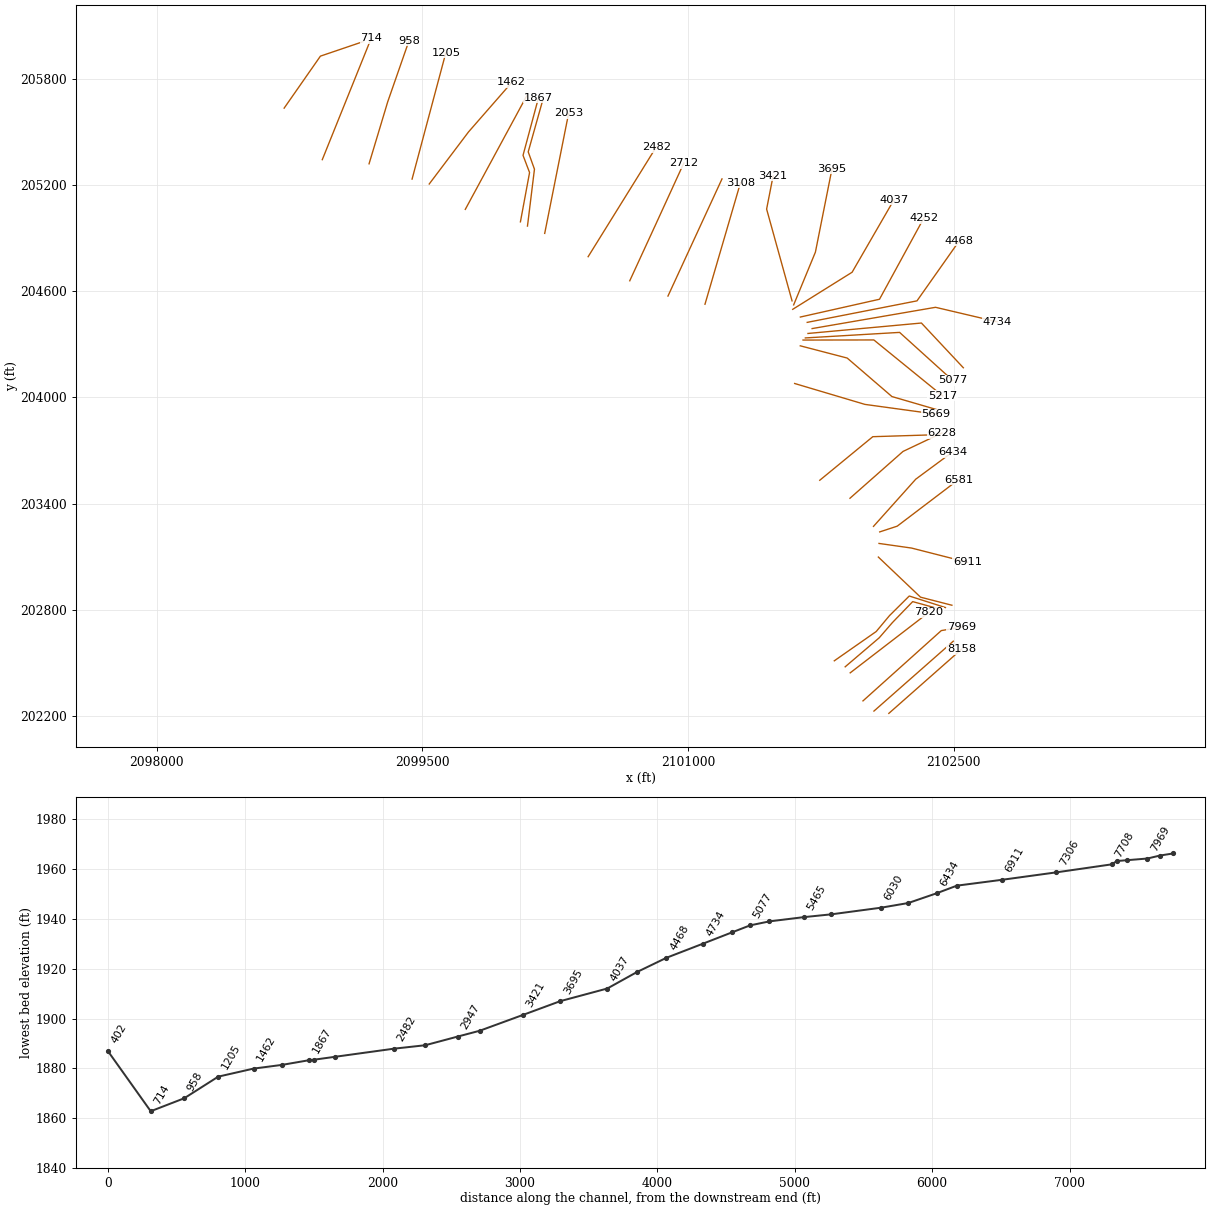
HEC-RAS study TCKTTBR.prj: TCKTTBR

--- TCKTTBR.g01 (geometry) --- (continued)

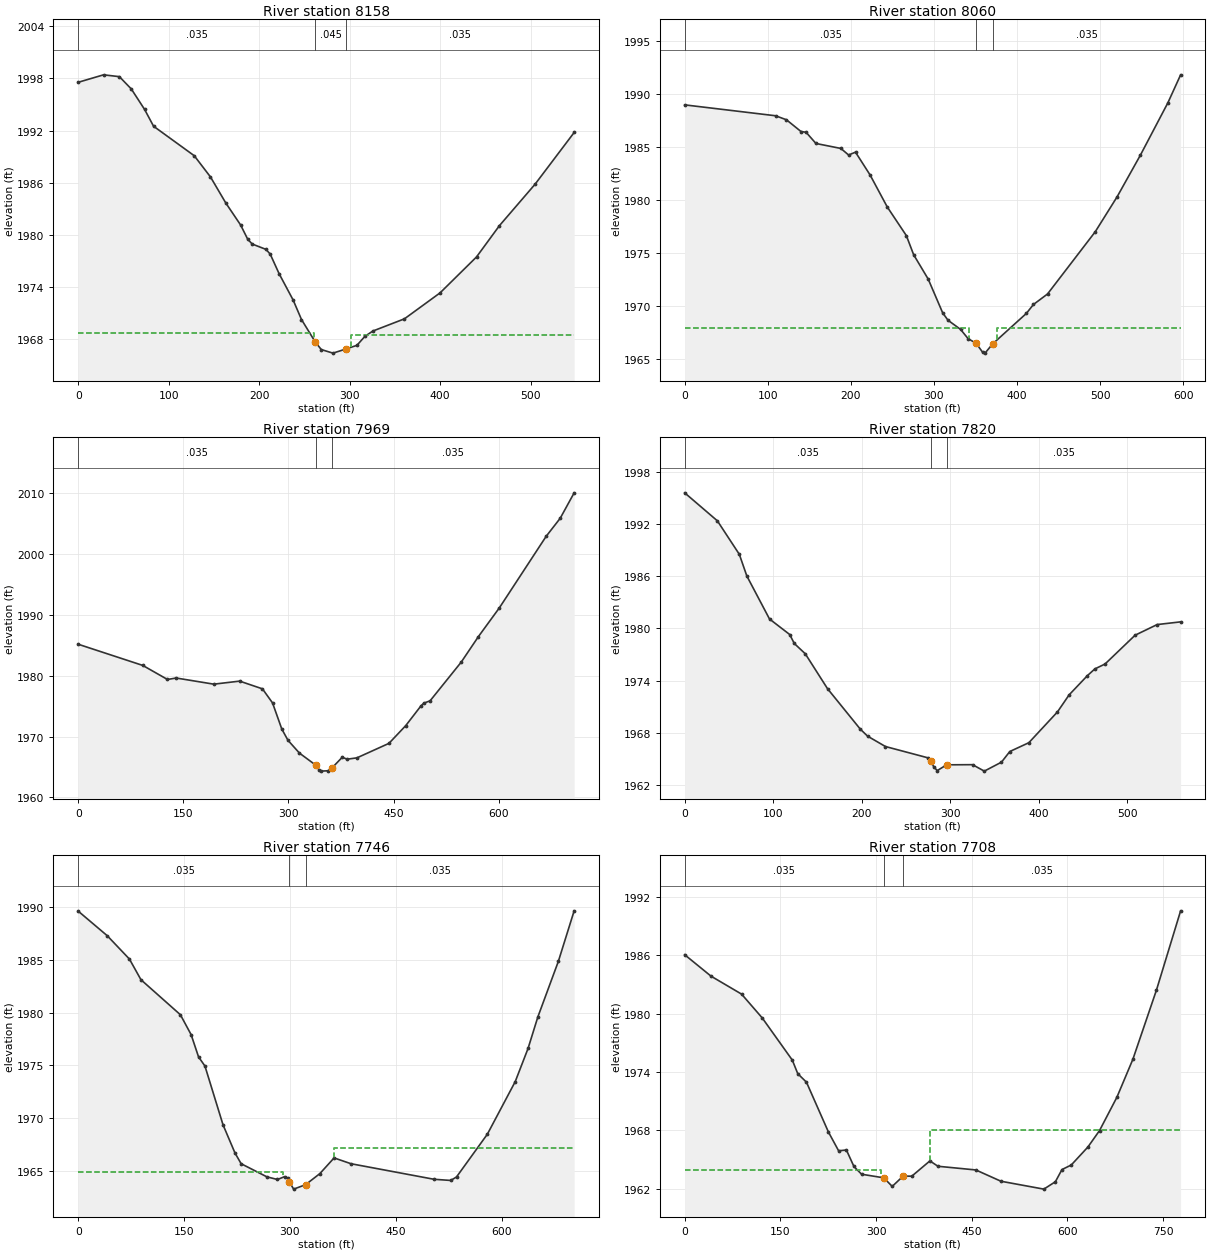
Type RM Length L Ch R = 1 ,8158    ,96,98.4,72.7
XS GIS Cut Line= 2
2102134.48385764202215.0739994182102545.51902753202577.845645715
#Sta/Elev= 30
       0 1997.56      28 1998.42    45.5 1998.21    58.7 1996.79    73.4 1994.43
    83.3  1992.5   128.3  1989.1   146.2 1986.66   163.2 1983.65   179.5 1981.13
   187.4 1979.48   192.4 1978.93   207.5 1978.32   212.2 1977.78   222.1 1975.51
   237.6 1972.48   246.8 1970.24   262.11967.642   268.7 1966.78   281.6 1966.37
     2961966.847   308.1 1967.27   316.8 1968.29   325.6 1968.91   360.6 1970.32
     400 1973.31   440.3 1977.45   465.6 1981.05   504.9 1985.81   548.2 1991.78
#Mann= 3 ,-1 , 0
       0    .035       0   262.1    .045       0     296    .035       0
#XS Ineff= 2 , 0
          260.88 1968.64  300.99         1968.49
Permanent Ineff=
       F       F
Bank Sta=262.1,296
XS Rating Curve= 0 ,0
Exp/Cntr=0.5,0.3

Type RM Length L Ch R = 1 ,8060    ,89.9,90.6,90.2
XS GIS Cut Line= 2
     2102050.424      202228.075      2102498.34      202622.607
#Sta/Elev= 30
       0 1988.98   109.4 1987.95   122.5 1987.57     140 1986.46   146.1 1986.39
     158 1985.33     188 1984.86   197.3 1984.24   205.6 1984.51   223.1 1982.36
   243.8 1979.33   266.8 1976.62   275.6 1974.81   293.1 1972.51   310.5 1969.32
   316.9 1968.62   332.1 1967.75   341.1 1966.88   350.91966.432   358.6 1965.59
   361.5 1965.51   370.61966.378   411.2 1969.26   419.8 1970.11   436.7  1971.1
   494.2 1976.99   520.4 1980.28   548.3  1984.2   581.6 1989.18   596.9 1991.82
#Mann= 3 ,-1 , 0
       0    .035       0   350.9    .045       0   370.6    .035       0
#XS Ineff= 2 , 0
          342.03 1967.89  376.38         1967.86
Permanent Ineff=
       F       F
Bank Sta=350.9,370.6
XS Rating Curve= 0 ,0
Exp/Cntr=0.5,0.3

Type RM Length L Ch R = 1 ,7969    ,148.5,149.4,147.2
XS GIS Cut Line= 3
     2101988.561       202285.64     2102430.632      202682.502
     2102542.611      202702.034
#Sta/Elev= 30
       0 1985.17    92.1 1981.69   127.4 1979.38   139.8 1979.62   193.5 1978.61
   230.4 1979.11   262.9 1977.84   277.3 1975.53   290.5 1971.24   299.3 1969.39
   315.7 1967.28   339.51965.257   344.2 1964.44   346.6 1964.32   356.6 1964.38
   362.31964.865   376.8  1966.6   383.7 1966.28   397.7  1966.5   443.4 1968.88
   467.4  1971.8   488.9 1975.01   493.3  1975.5   502.1 1975.87   546.6 1982.24
   571.1 1986.43   601.1 1991.17   667.8 2002.91   687.8 2005.87   707.7 2010.05
#Mann= 3 ,-1 , 0
       0    .035       0   339.5    .045       0   362.3    .035       0
Bank Sta=339.5,362.3
XS Rating Curve= 0 ,0
Exp/Cntr=0.3,0.1

Type RM Length L Ch R = 1 ,7820    ,67.5,73.6,75.6
XS GIS Cut Line= 2
2101916.31331464202443.9341214192102360.26126962202785.432548333
#Sta/Elev= 30
       0 1995.56    36.9 1992.35    61.7 1988.51    70.2 1986.02    95.8 1981.09
   118.6 1979.31   123.8 1978.28   136.2  1977.1   161.3  1973.1   198.3 1968.46
   206.6 1967.65   226.8 1966.46   274.6 1965.17   278.3 1964.82   281.1 1964.16
   285.2  1963.7   295.91964.364   325.1 1964.38   338.4 1963.64   357.8 1964.67
   367.2 1965.89   388.7  1966.9     421 1970.43   434.2 1972.39   454.9  1974.6
   463.2 1975.36   474.8 1975.93   508.7 1979.23   533.6 1980.45   560.1 1980.76
#Mann= 3 ,-1 , 0
       0    .035       0   278.3    .045       0   295.9    .035       0
Bank Sta=278.3,295.9
XS Rating Curve= 0 ,0
Exp/Cntr(USF)=0,0
Exp/Cntr=0.5,0.3

Type RM Length L Ch R = 1 ,7746    ,37.8,37.7,37.6
XS GIS Cut Line= 5
2101887.97459326      202478.0752102080.23255955202642.003209029
2102154.22388539202727.3778157572102269.20550113202846.229280897
2102434.75829889202800.485233705
#Sta/Elev= 30
       0 1989.58    41.1 1987.26    72.6 1985.05    88.9  1983.1   144.8 1979.79
     160 1977.91   170.5 1975.81   179.6 1974.94   205.2 1969.39   222.2 1966.72
   230.9 1965.71   267.4 1964.47   282.4 1964.22   292.5 1964.49   297.5 1964.35
     2991964.028   305.3 1963.31   322.21963.728   342.5 1964.78   362.6 1966.26
   386.6 1965.71   504.3 1964.24   527.9 1964.13   536.1 1964.46   579.8  1968.5
   619.3 1973.47   637.5 1976.61   651.3 1979.57   680.4 1984.83   702.8 1989.61
#Mann= 3 ,-1 , 0
       0    .035       0     299    .045       0   322.2    .035       0
#XS Ineff= 2 , 0
          290.55 1964.91  362.03          1967.2
Permanent Ineff=
       F       F
Bank Sta=299,322.2
XS Rating Curve= 0 ,0
Exp/Cntr=0.5,0.3

Type RM Length L Ch R = 1 ,7708    ,438.3,402.3,385.8
XS GIS Cut Line= 5
     2101826.465      202511.9292102063.15763821 202677.29137981
2102138.28729213202767.2192988972102249.81404719202877.806624718
      2102454.07      202812.711
#Sta/Elev= 30
       0 1986.06    41.2 1983.86    89.2 1982.01   121.6 1979.56   168.7 1975.23
   177.3 1973.83   190.9 1972.96   225.4 1967.83   241.3 1965.91   253.5 1965.99
   265.3  1964.3   277.3  1963.5   312.2 1963.13   325.3 1962.25   342.5 1963.31
     356  1963.3   384.4 1964.87     397 1964.32   456.4 1963.94   495.8 1962.78
     563 1961.97   581.1 1962.73   591.4 1963.98     606 1964.45   632.1  1966.3
   650.3 1967.99   677.5 1971.41   702.6 1975.32   739.5 1982.42   777.4 1990.57
#Mann= 3 , 0 , 0
       0    .035       0   312.2    .045       0   342.5    .035       0
#XS Ineff= 2 , 0
          306.99 1963.98  385.08         1968.06
Permanent Ineff=
       F       F
Bank Sta=312.2,342.5
XS Rating Curve= 0 ,0
Exp/Cntr=0.5,0.3

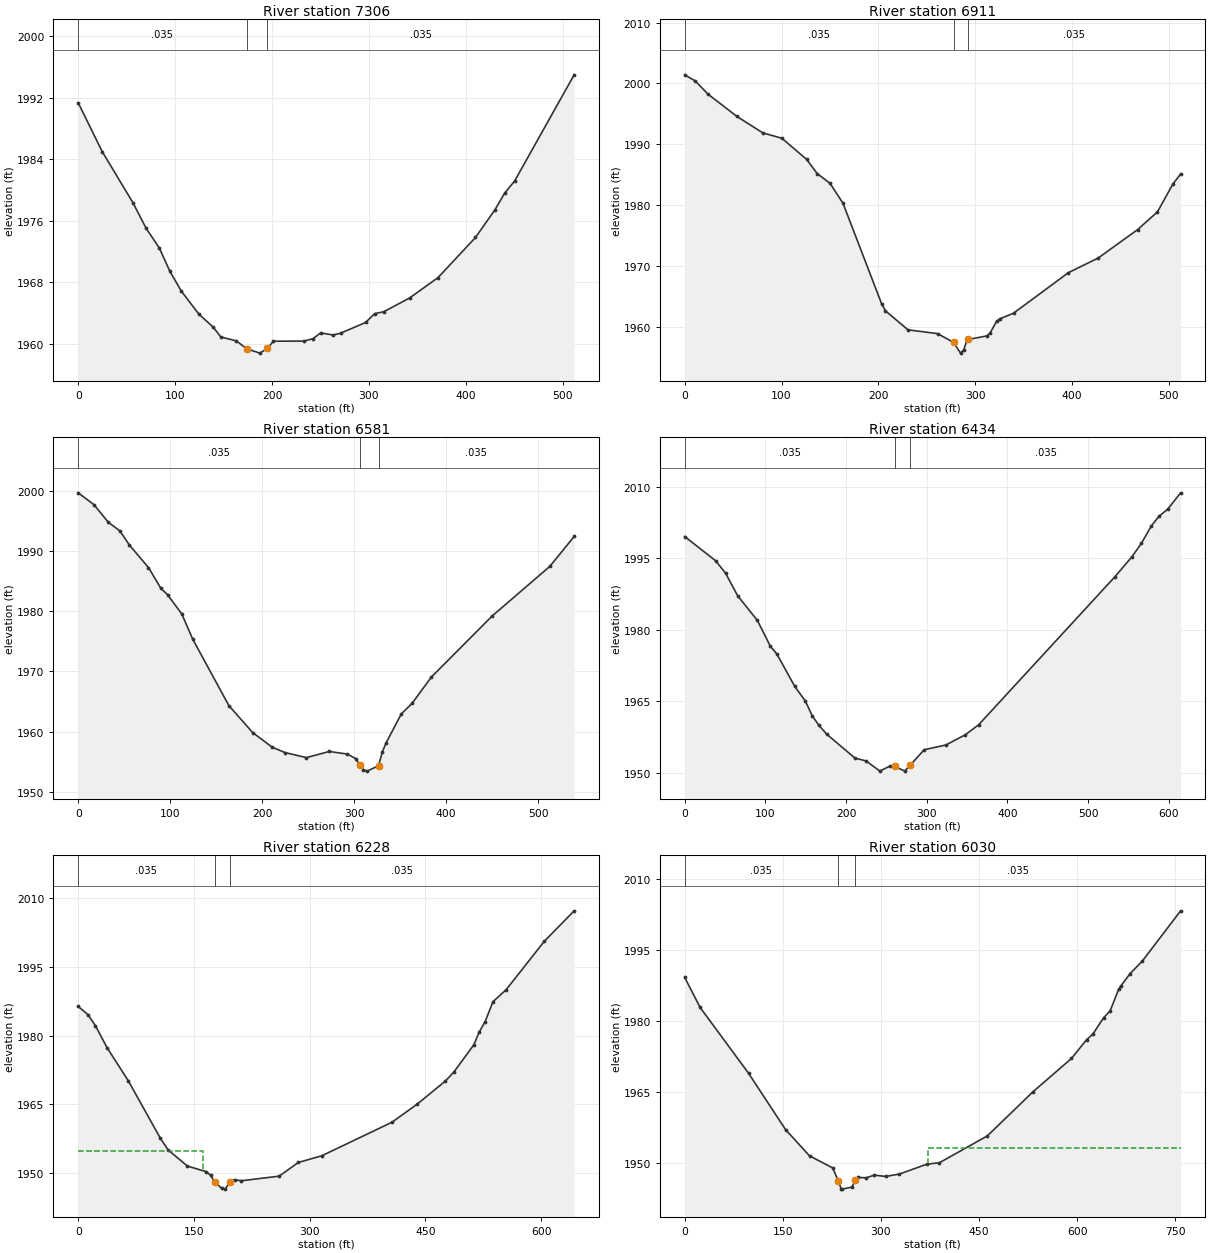
Type RM Length L Ch R = 1 ,7306    ,367.8,395.5,369.4
XS GIS Cut Line= 3
     2102075.163      203097.867     2102313.445      202871.304
     2102490.528      202825.732
#Sta/Elev= 30
       0 1991.36    24.8 1984.99    56.5 1978.34    70.1 1975.01    83.7 1972.45
    94.6 1969.41   106.3 1966.85   124.4 1963.85   139.4 1962.13   147.1 1960.87
   163.2 1960.35   173.71959.339   187.4 1958.76   195.3 1959.39   201.4 1960.31
   233.1 1960.33   242.2 1960.64   250.1 1961.39   263.2 1961.12     271 1961.37
   296.5 1962.75   305.8  1963.9   315.1 1964.14   341.9 1965.94   371.2 1968.59
   409.9 1973.82     430 1977.43   440.1 1979.61   450.3 1981.18   511.7    1995
#Mann= 3 ,-1 , 0
       0    .035       0   173.7    .045       0   195.3    .035       0
Bank Sta=173.7,195.3
XS Rating Curve= 0 ,0
Exp/Cntr=0.3,0.1

Type RM Length L Ch R = 1 ,6911    ,303.5,329.4,327
XS GIS Cut Line= 3
      2102079.07       203174.69     2102262.663      203148.648
      2102579.07      203067.919
#Sta/Elev= 30
       0 2001.42    10.9 2000.42    24.2 1998.23      54 1994.59    80.5 1991.91
   100.4 1991.01   125.9 1987.55   136.8 1985.22   150.1 1983.61   163.4 1980.37
   203.5 1963.79   207.3  1962.7   230.6 1959.59   261.1 1958.97   277.6 1957.53
   284.8 1955.77   288.1  1956.3   291.5 1957.94   292.6 1958.01   311.9 1958.59
   315.2 1959.03     322 1960.99   325.4  1961.4   339.5 1962.32   396.1 1968.96
     427 1971.38   467.6 1976.03   488.1 1978.94     504  1983.5     512 1985.15
#Mann= 3 ,-1 , 0
       0    .035       0   277.6    .045       0   292.6    .035       0
Bank Sta=277.6,292.6
XS Rating Curve= 0 ,0
Exp/Cntr=0.3,0.1

Type RM Length L Ch R = 1 ,6581    ,145.1,147.6,150.3
XS GIS Cut Line= 3
     2102082.976      203239.794     2102181.934      203272.346
     2102528.288      203535.367
#Sta/Elev= 30
       0 1999.74    17.1 1997.77    32.7 1994.84    45.3  1993.4    55.6 1991.06
    76.4  1987.3    89.8 1983.85    97.1 1982.78   112.5  1979.6   124.5 1975.37
   163.8 1964.31   189.6 1959.84   210.7 1957.41   224.7  1956.5   248.1 1955.66
   272.9 1956.68   292.6 1956.25   301.7 1955.48   306.21954.463   309.9 1953.67
     314 1953.41   326.51954.316   330.5 1956.57   334.6 1958.09   351.2 1962.93
   362.9 1964.69   383.9 1969.07     450 1979.24   512.7  1987.5   539.1 1992.47
#Mann= 3 ,-1 , 0
       0    .035       0   306.2    .045       0   326.5    .035       0
Bank Sta=306.2,326.5
XS Rating Curve= 0 ,0
Exp/Cntr=0.3,0.1

Type RM Length L Ch R = 1 ,6434    ,207.7,205.7,204.5
XS GIS Cut Line= 3
      2102047.82      203271.044     2102286.596      203537.663
     2102493.132      203690.315
#Sta/Elev= 30
       0 1999.59    38.5 1994.48    50.6 1991.91    65.8 1987.12    90.1 1981.98
   106.3 1976.52   114.2 1974.94   136.5 1968.11   149.5 1965.07   158.3 1961.89
   166.3 1959.97     176 1958.11   210.9 1953.09   224.8 1952.48     242 1950.34
     255 1951.46   260.31951.329   272.8 1950.36   279.81951.633   296.8 1954.83
   323.7 1955.82     348 1957.99   364.3 1960.06   533.2 1991.13   554.3 1995.33
   566.2 1998.18   578.4 2001.82   587.9 2003.83   598.9 2005.37   614.7 2008.76
#Mann= 3 ,-1 , 0
       0    .035       0   260.3    .045       0   279.8    .035       0
Bank Sta=260.3,279.8
XS Rating Curve= 0 ,0
Exp/Cntr=0.3,0.1

Type RM Length L Ch R = 1 ,6228    ,192.9,198,192.8
XS GIS Cut Line= 3
     2101915.007      203429.898     2102214.486      203694.221
     2102434.268      203798.525
#Sta/Elev= 30
       0 1986.35    12.5 1984.58    22.4 1982.12    37.3 1977.36    64.7 1970.17
   106.5 1957.54   116.6 1954.99   141.4 1951.49   166.2 1950.24   171.6 1949.44
   176.81948.018     186  1946.6   190.2 1946.44     1971948.022   202.6 1948.51
   211.4 1948.27   260.4 1949.27   285.2 1952.26   315.7 1953.73   406.8 1961.07
   439.5 1965.04   475.6 1970.02   486.7 1971.99   512.7 1977.97   519.4 1980.66
   527.4 1983.06   537.5 1987.39   554.5 1989.99   603.8 2000.54   642.7 2007.24
#Mann= 3 ,-1 , 0
       0    .035       0   176.8    .045       0     197    .035       0
#XS Ineff= 2 , 0
          162.08 1954.68
Permanent Ineff=
       F       F
Bank Sta=176.8,197
XS Rating Curve= 0 ,0
Exp/Cntr=0.3,0.1

Type RM Length L Ch R = 1 ,6030    ,371.9,361.1,344.2
XS GIS Cut Line= 3
     2101744.434      203531.461     2102043.913      203777.554
     2102414.134       203788.97
#Sta/Elev= 30
       0 1989.28    23.6 1982.93    97.6 1969.04   154.1 1957.15   190.8 1951.59
   226.3 1949.04   234.51946.345   239.1 1944.66   240.6 1944.56   255.7 1944.99
   260.61946.402   265.4 1947.03   277.1 1946.95     290 1947.52     307 1947.24
   328.2 1947.74   370.3 1949.84   389.2 1950.12   462.7 1955.81   532.1 1965.09
   591.2 1972.16   614.2  1976.1     624 1977.33   640.4 1980.77   650.3 1982.21
   663.3 1986.78   666.9  1987.5   680.4 1990.02   699.5 1992.74     758 2003.34
#Mann= 3 ,-1 , 0
       0    .035       0   234.5    .045       0   260.6    .035       0
#XS Ineff= 2 , 0
                          372.39         1953.24
Permanent Ineff=
       F       F
Bank Sta=234.5,260.6
XS Rating Curve= 0 ,0
Exp/Cntr=0.3,0.1

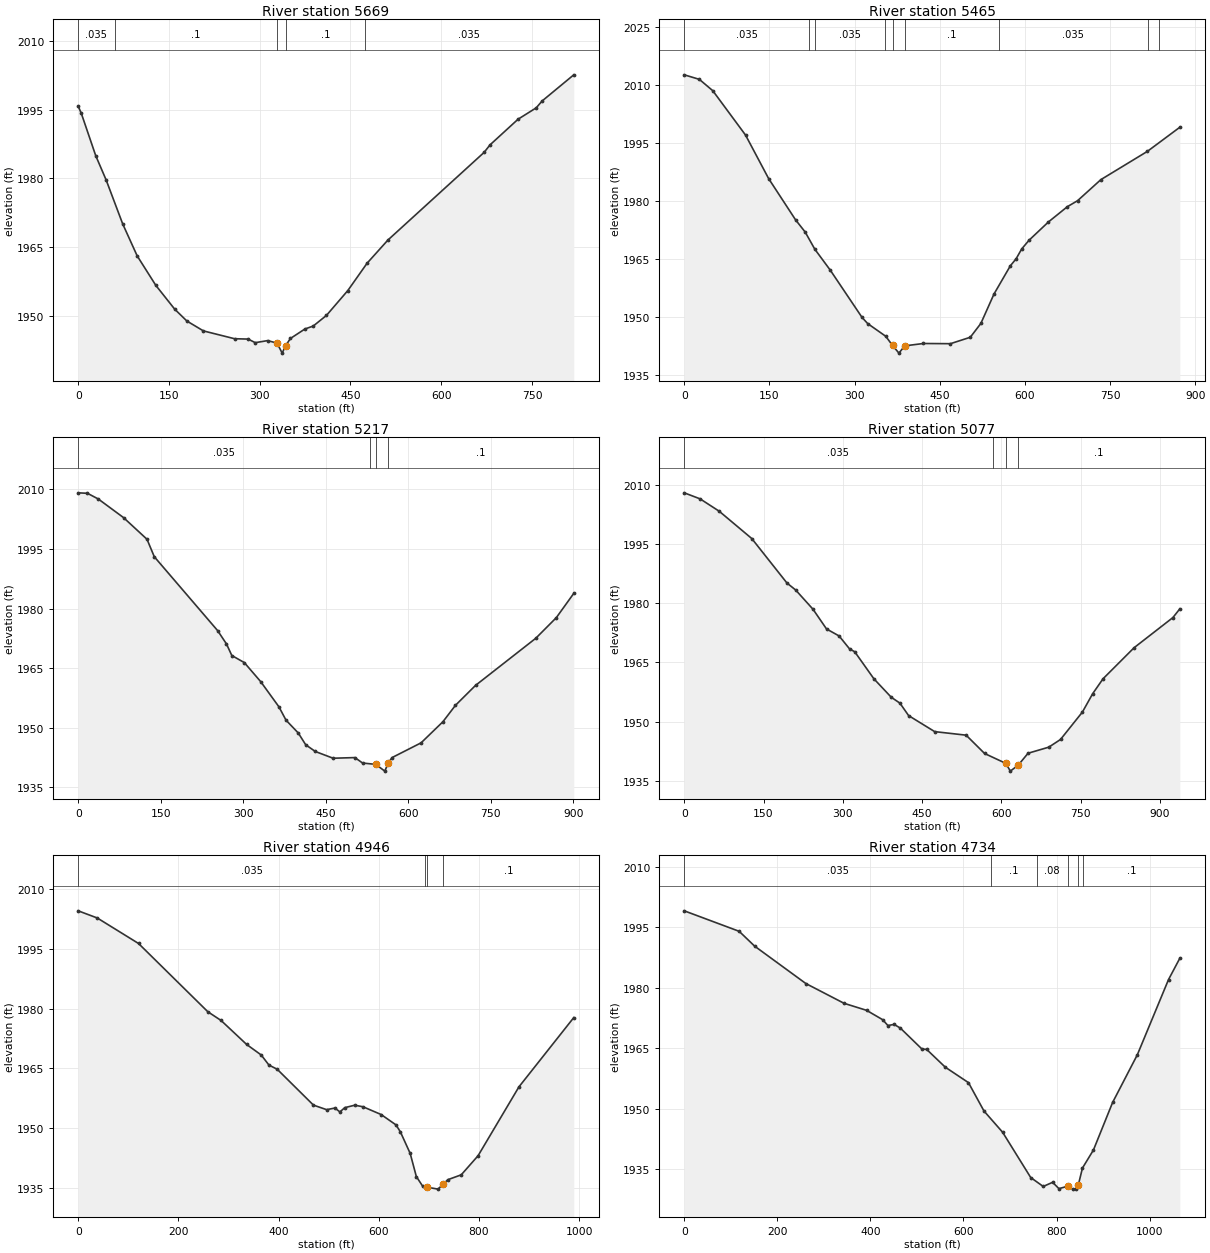
Type RM Length L Ch R = 1 ,5669    ,208,203.6,194.3
XS GIS Cut Line= 3
2101602.73171893204077.868294034     2101999.643      203959.846
      2102400.84      203904.845
#Sta/Elev= 30
       0 1995.72     5.1 1994.18      29 1984.93    46.2 1979.64    73.5 1970.08
    97.5 1963.09   128.3 1956.67   159.5 1951.48   179.6  1948.9     207 1946.74
   258.4 1945.04   280.9 1944.96   292.6 1944.18   313.1 1944.63   328.71944.079
   337.1  1941.9   342.71943.514   350.8  1945.1   374.7 1947.16   388.4  1947.8
   410.2 1950.11   445.6 1955.54   477.4 1961.49   511.8 1966.54   670.8 1985.65
   680.6 1987.29     727 1992.89   756.9 1995.36   766.8 1996.87     819 2002.56
#Mann= 5 ,-1 , 0
       0    .035       0      60      .1       0   328.7    .045       0
   342.7      .1       0  474.09    .035       0
Bank Sta=328.7,342.7
XS Rating Curve= 0 ,0
Exp/Cntr=0.3,0.1

Type RM Length L Ch R = 1 ,5465    ,237.8,247.9,239.7
XS GIS Cut Line= 4
     2101634.354      204290.682     2101899.382      204221.565
     2102151.986      204004.117     2102407.195      203929.898
#Sta/Elev= 30
       0 2012.68    26.6 2011.51    50.3 2008.57     108  1997.1   148.7 1985.85
   196.1  1975.2   213.1 1972.03     230 1967.61   257.4 1962.16   313.1    1950
   323.1 1948.39     355  1945.1   366.91942.731   378.2 1940.75   388.31942.626
   421.4 1943.24   468.9 1943.19   503.9 1944.85   522.5 1948.42   545.7 1956.04
   574.5 1963.33   584.6 1965.13   594.5 1967.69   607.4 1969.93   641.6 1974.66
   674.9  1978.6   692.9 1980.15   733.9 1985.59   815.9  1992.9     873 1999.13
#Mann= 9 ,-1 , 0
       0    .035       0     220      .1       0     230    .035       0
  353.89      .1       0   366.9    .045       0   388.3      .1       0
  553.89    .035       0   817.2      .1       0   837.2    .035       0
Bank Sta=366.9,388.3
XS Rating Curve= 0 ,0
Exp/Cntr=0.3,0.1

Type RM Length L Ch R = 1 ,5217    ,139.6,140.7,136.6
XS GIS Cut Line= 3
     2101649.789      204323.229     2102049.904      204323.809
     2102438.381      204007.764
#Sta/Elev= 30
       0 2009.16    16.9 2009.04    36.6  2007.6    82.5 2002.91   125.1 1997.46
   138.3 1993.07   253.5 1974.45   269.5 1971.11   279.3 1968.18     302  1966.4
   331.8  1961.6   364.9 1955.26   377.8  1951.9   400.1 1948.66   413.6  1945.7
     431 1944.01   463.4 1942.31     503 1942.47     517  1941.1   540.91940.763
   557.4 1939.06   563.41941.063   570.7 1942.48   623.4 1946.19   663.1 1951.51
   685.8 1955.63   722.3 1960.65   831.9 1972.53   869.2 1977.72   900.9 1983.83
#Mann= 4 ,-1 , 0
       0    .035       0  530.12      .1       0   540.9    .045       0
   563.4      .1       0
Bank Sta=540.9,563.4
XS Rating Curve= 0 ,0
Exp/Cntr=0.3,0.1

Type RM Length L Ch R = 1 ,5077    ,129.4,130.4,131
XS GIS Cut Line= 3
2101662.95402497204335.2531107312102195.20129926 204366.48827941
2102495.05891858204095.367015276
#Sta/Elev= 30
       0 2007.98      30 2006.45    66.2 2003.31   127.7  1996.4   194.3 1985.12
   210.8 1983.35   243.6 1978.47   269.1 1973.49   292.9 1971.71   312.6 1968.45
   322.5  1967.7   358.7 1960.86   391.5 1956.19     408 1954.68   424.4 1951.53
   473.7 1947.47   533.2 1946.57   568.1 1941.93   608.41939.416   616.8 1937.46
   631.71938.971   650.3 1941.99   689.5 1943.53   711.7 1945.48   753.1 1952.42
   772.6 1957.09   792.2 1960.87   850.9 1968.73   924.3 1976.37   937.4 1978.58
#Mann= 4 ,-1 , 0
       0    .035       0  583.16      .1       0   608.4    .045       0
   631.7      .1       0
Bank Sta=608.4,631.7
XS Rating Curve= 0 ,0
Exp/Cntr(USF)=0,0
Exp/Cntr=0.3,0.1

Type RM Length L Ch R = 1 ,4946    ,202.4,212.6,216.3
XS GIS Cut Line= 3
     2101677.902       204360.45     2102318.456      204419.395
     2102555.147      204166.774
#Sta/Elev= 30
       0 2004.62    38.1 2002.82   120.5 1996.41   258.9 1979.25   285.2 1977.07
   336.3 1971.04   365.4 1968.39   380.8 1965.86   397.3 1964.81   469.7 1955.79
     496 1954.65   512.6 1955.06   522.5 1954.08   532.3 1955.16   552.1 1955.77
   568.6 1955.38   604.8 1953.43   634.5 1950.82   643.3 1949.06   662.8 1943.66
   675.1 1937.84     688 1935.37   697.21935.148   718.5 1934.68   728.21935.897
     738 1937.05   764.8 1938.28   798.4 1943.08     880 1960.39   989.4 1977.79
#Mann= 4 ,-1 , 0
       0    .035       0  693.26      .1       0   697.2    .045       0
   728.2      .1       0
Bank Sta=697.2,728.2
XS Rating Curve= 0 ,0
Exp/Cntr=0.3,0.1

Type RM Length L Ch R = 1 ,4734    ,241.5,265.8,281.4
XS GIS Cut Line= 3
     2101701.275      204388.079     2102398.112      204508.154
      2102746.32      204426.223
#Sta/Elev= 30
       0 1999.11     118 1994.03   151.3 1990.35   261.2 1981.09   343.4 1976.18
   391.7 1974.44   426.3 1972.12   437.6 1970.67   450.9 1970.95   464.3 1970.04
   510.8 1964.83   520.9 1964.75   560.8 1960.35   610.7 1956.51     644 1949.48
     684 1944.22   744.4 1932.99   771.3 1930.77   791.5  1931.8     805 1930.23
   824.21930.837   834.6 1930.11   842.1 1930.19   846.91931.233   855.6 1935.34
   879.2 1939.81   920.4  1951.6   973.6 1963.44  1040.5 1982.06  1064.8 1987.35
#Mann= 6 ,-1 , 0
       0    .035       0     660      .1       0  757.11     .08       0
   824.2    .045       0   846.9     .08       0  857.11      .1       0
Bank Sta=824.2,846.9
XS Rating Curve= 0 ,0
Exp/Cntr=0.3,0.1

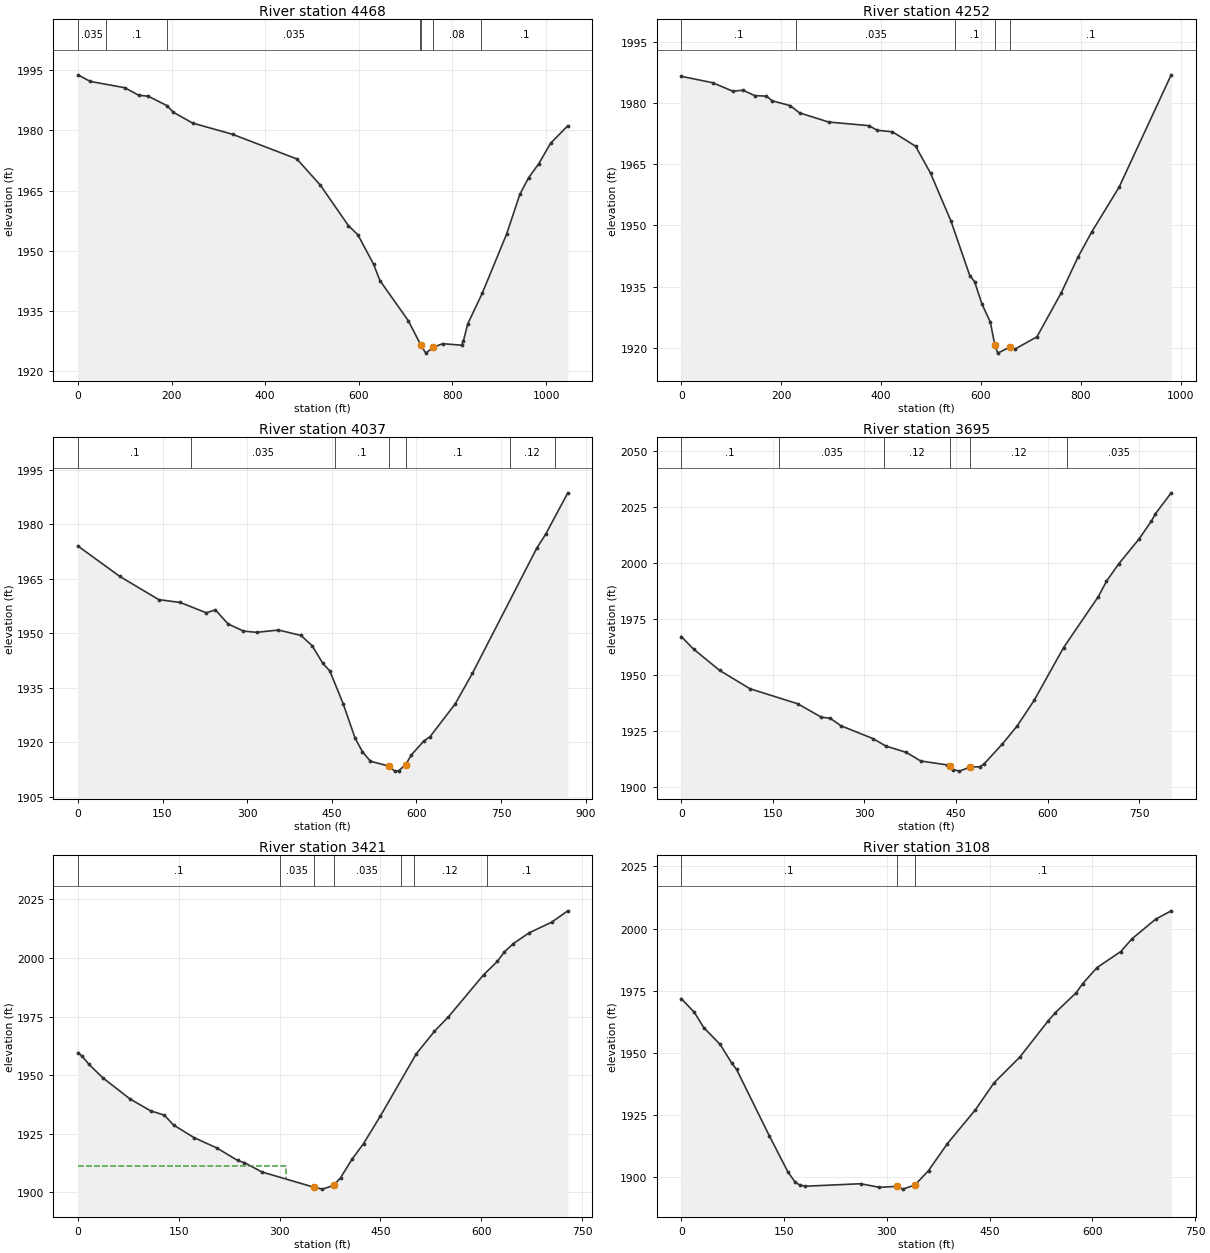
Type RM Length L Ch R = 1 ,4468    ,210.3,215.8,213.9
XS GIS Cut Line= 3
     2101673.572      204423.108     2102293.422      204544.568
     2102532.388      204883.673
#Sta/Elev= 30
       0 1993.89    26.4 1992.24    99.9 1990.68     130 1988.78   150.1 1988.56
   190.2 1986.21   203.6 1984.57   245.1 1981.85   330.6 1979.04   467.7  1972.9
   517.8 1966.37     578 1956.23   598.1 1953.96   631.6 1946.63   645.1 1942.55
   705.5 1932.58   732.9 1926.38   743.1 1924.44     7591925.873   779.2  1926.8
   819.4 1926.42   823.4 1927.44   832.8 1931.76   863.5 1939.33   915.7 1954.14
   944.1 1964.09     963 1968.26   984.6 1971.74  1009.5 1976.79  1046.5 1981.19
#Mann= 7 ,-1 , 0
       0    .035       0      60      .1       0     190    .035       0
  731.64     .08       0   732.9    .045       0     759     .08       0
  861.64      .1       0
Bank Sta=732.9,759
XS Rating Curve= 0 ,0
Exp/Cntr=0.3,0.1

Type RM Length L Ch R = 1 ,4252    ,213.7,215,211.9
XS GIS Cut Line= 3
     2101634.754      204453.232     2102081.766      204553.672
     2102332.313      205012.666
#Sta/Elev= 30
       0 1986.54      63 1984.97   103.3 1982.89   123.5 1983.14     147 1981.82
   170.6 1981.68   182.1 1980.54   217.8 1979.37     237 1977.58     295 1975.34
   375.7 1974.45   392.5 1973.31   422.8 1972.95   469.3  1969.4   499.2 1962.79
   540.4 1950.96   577.7  1937.7   587.4  1936.2   601.9 1930.78   618.9 1926.28
   628.11920.555   633.8 1918.68   657.51920.139   667.4 1919.62   712.3 1922.69
   760.9 1933.47   794.5 1942.24     822  1948.4   876.8 1959.38   981.1 1986.91
#Mann= 5 ,-1 , 0
       0      .1       0     230    .035       0  548.16      .1       0
   628.1    .045       0   657.5      .1       0
Bank Sta=628.1,657.5
XS Rating Curve= 0 ,0
Exp/Cntr=0.3,0.1

Type RM Length L Ch R = 1 ,4037    ,331,342.3,342.3
XS GIS Cut Line= 3
     2101591.663      204496.753     2101927.007      204706.155
     2102163.697      205115.812
#Sta/Elev= 30
       0 1974.06    74.3 1965.69   143.3  1959.3   181.3 1958.52   227.7 1955.67
   243.7 1956.48   266.3  1952.6   293.4 1950.65   316.6 1950.29   355.5 1950.93
   395.4 1949.45     415 1946.66   434.2 1941.77   446.6 1939.67   470.2 1930.66
   491.4 1921.16   504.5  1917.4   518.6 1914.82     5521913.441   561.4 1912.09
   568.7 1912.21   581.31913.885   590.5 1916.45   613.3  1920.4   623.9  1921.5
   668.5 1930.52   699.3 1939.01   813.6 1973.51   829.3 1977.34   868.5  1988.7
#Mann= 7 ,-1 , 0
       0      .1       0     200    .035       0  455.35      .1       0
     552    .045       0   581.3      .1       0  765.35     .12       0
  845.35    .035       0
Bank Sta=552,581.3
XS Rating Curve= 0 ,0
Exp/Cntr=0.3,0.1

Type RM Length L Ch R = 1 ,3695    ,262.8,273.9,283
XS GIS Cut Line= 3
     2101597.005       204521.81     2101719.902      204819.949
     2101813.577      205290.815
#Sta/Elev= 30
       0  1967.2    20.2 1961.58    62.8 1952.07   112.5 1943.86   190.6 1937.15
   229.6 1931.11   243.8 1930.69   261.5 1927.31   313.9 1921.58   335.2 1918.23
   368.7 1915.38   392.2 1911.55   435.8 1909.78     440 1909.12   445.7 1907.69
   455.7 1907.01   472.71908.763   489.2 1908.99   495.9 1910.19     526 1919.13
   550.2 1927.19   578.1 1938.69   626.3 1962.26   683.2 1985.05   696.6 1991.94
   716.6  1999.7   750.1 2010.88   770.2 2018.87   776.8 2022.12   802.6 2031.48
#Mann= 6 ,-1 , 0
       0      .1       0     160    .035       0  332.48     .12       0
     440    .045       0   472.7     .12       0  632.48    .035       0
Bank Sta=440,472.7
XS Rating Curve= 0 ,0
Exp/Cntr=0.3,0.1

Type RM Length L Ch R = 1 ,3421    ,321.5,312.5,301.3
XS GIS Cut Line= 3
     2101587.902      204544.568     2101444.288      205062.771
     2101480.936      205250.088
#Sta/Elev= 30
       0  1959.6       6 1958.28    16.2 1954.74    36.7    1949    77.5  1939.9
   108.1 1934.83   128.6 1932.97   142.2  1928.8   172.8 1923.39   206.9 1918.95
   237.5 1913.67   247.7  1912.7   273.9 1908.73   351.2 1902.23   363.5 1901.43
   380.4    1903   390.7 1906.33   407.7 1914.18   424.8 1920.87   449.9 1932.64
   503.2 1959.14   530.3 1968.78   551.1 1974.97   603.7 1992.99     624 1998.62
   634.1 2002.61   647.4 2006.14   670.8 2010.73   704.4 2015.29   728.6 2020.16
#Mann= 7 ,-1 , 0
       0      .1       0     300    .035       0   351.2    .045       0
   380.4    .035       0     480      .1       0     500     .12       0
  607.74      .1       0
#XS Ineff= 2 , 0
          309.32 1911.11
Permanent Ineff=
       F       F
Bank Sta=351.2,380.4
XS Rating Curve= 0 ,0
Exp/Cntr=0.3,0.1

Type RM Length L Ch R = 1 ,3108    ,164,161.6,158.8
XS GIS Cut Line= 2
     2101096.242      204525.451     2101296.816      205211.883
#Sta/Elev= 30
       0 1971.81    19.1 1966.27    32.8 1960.13    56.7 1953.38    73.8 1945.77
    80.6 1943.37   128.5 1916.59   155.8 1901.97   166.1 1897.99   172.9 1896.76
   181.1 1896.29   261.8 1897.29   289.1 1895.85   314.91896.239   323.3 1895.12
   341.21896.799   360.9 1902.59   388.3 1913.39   429.3 1927.06   456.6 1937.94
   494.2 1948.28   535.2 1962.74   546.1  1966.2   576.3 1974.12   585.8 1977.81
   606.9 1984.31   641.3 1990.71   658.3 1995.98   692.5  2003.8   715.1 2007.14
#Mann= 3 ,-1 , 0
       0      .1       0   314.9    .045       0   341.2      .1       0
Bank Sta=314.9,341.2
XS Rating Curve= 0 ,0
Exp/Cntr=0.3,0.1

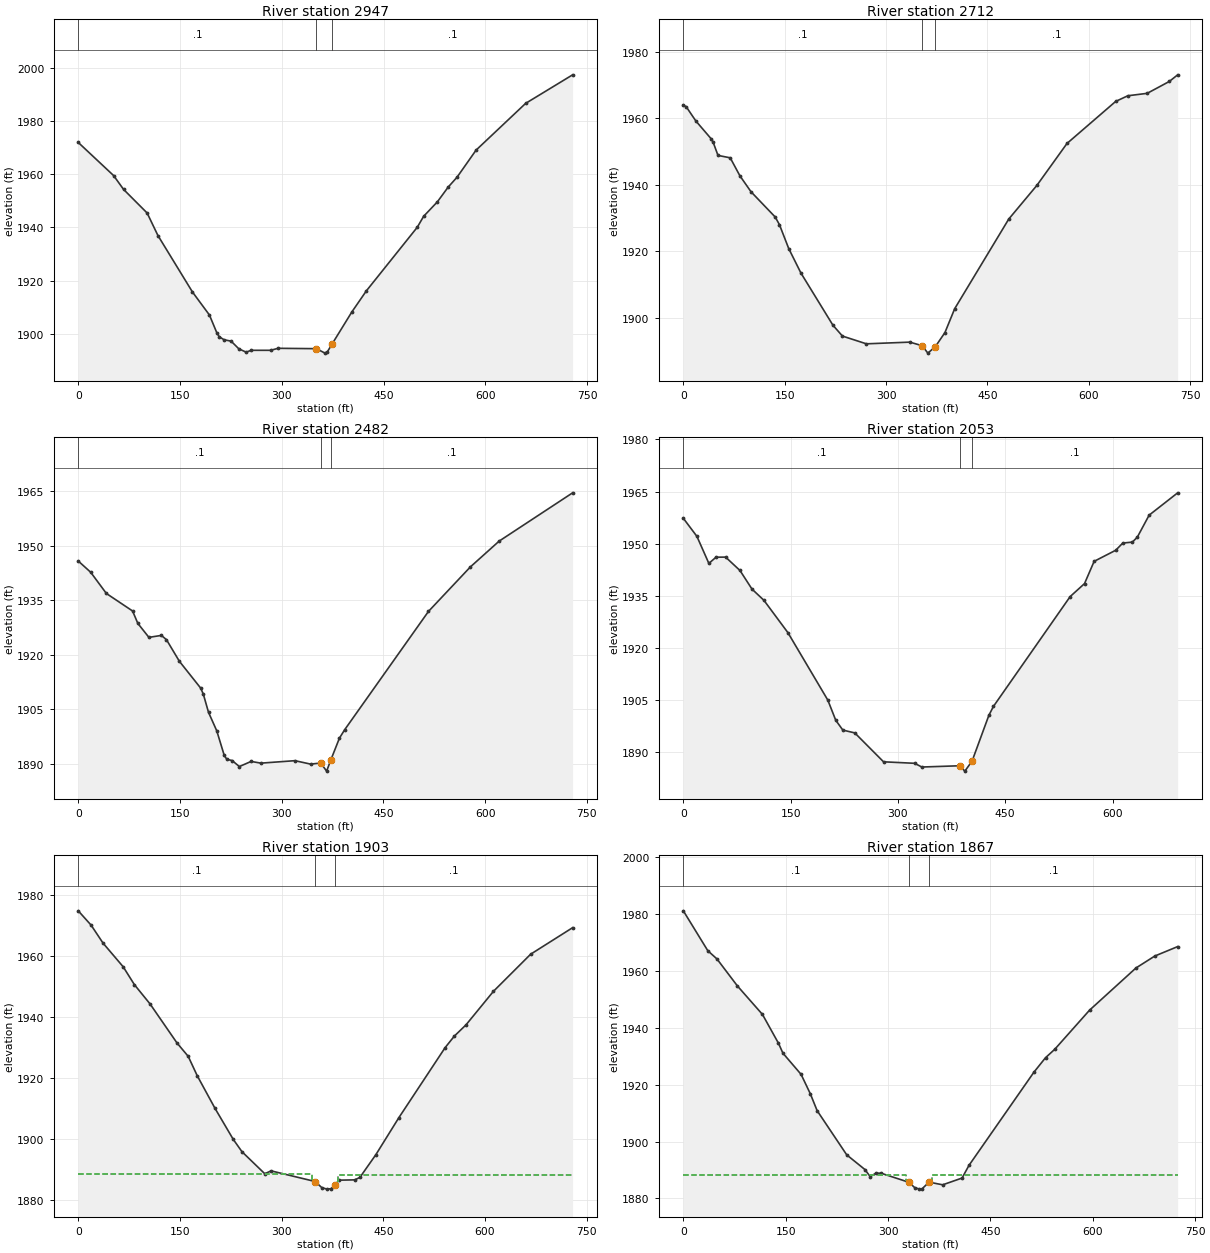
Type RM Length L Ch R = 1 ,2947    ,233.6,234.7,234
XS GIS Cut Line= 2
     2100887.247      204571.717     2101192.297      205233.244
#Sta/Elev= 30
       0  1971.9    52.1 1959.46    66.8 1954.26   101.5  1945.4   117.4 1936.94
   168.3 1915.72   193.3 1907.08   204.1 1900.46   207.7 1898.94   214.9 1897.77
   225.2 1897.27   236.6 1894.39   247.4 1893.12   254.8 1893.82   283.6 1893.82
   294.4 1894.57     3511894.432   363.6 1892.76   366.7 1893.08   373.81896.078
   403.2 1908.24   424.5 1916.13   499.6 1940.05     509 1944.17   529.2 1949.59
     545 1955.09   558.2 1958.85   586.2 1969.01   659.3 1986.59   728.5 1997.31
#Mann= 3 ,-1 , 0
       0      .1       0     351    .045       0   373.8      .1       0
Bank Sta=351,373.8
XS Rating Curve= 0 ,0
Exp/Cntr=0.3,0.1

Type RM Length L Ch R = 1 ,2712    ,231.5,230,227.8
XS GIS Cut Line= 3
     2100671.476      204657.972      2100823.39      204987.891
     2100976.786      205322.831
#Sta/Elev= 30
       0 1963.94     4.3 1963.43    18.6 1959.14    40.9 1953.86    44.1 1952.78
    51.3 1948.79    69.4 1948.07    83.8 1942.63   100.2 1937.85     136 1930.25
   142.3 1927.93     156 1920.76   174.1 1913.38   221.4  1897.7   235.5 1894.43
   270.9  1892.1   335.2 1892.61   353.41891.536   361.9  1889.3     3731891.255
   387.2  1895.5   401.6 1902.67   481.6 1929.64   523.3 1939.79   567.8 1952.39
   639.8 1965.03   657.8 1966.74   686.5 1967.47   719.2 1971.04   731.6 1973.04
#Mann= 3 ,-1 , 0
       0      .1       0   353.4    .045       0     373      .1       0
Bank Sta=353.4,373
XS Rating Curve= 0 ,0
Exp/Cntr=0.3,0.1

Type RM Length L Ch R = 1 ,2482    ,419.7,429.6,432.7
XS GIS Cut Line= 2
     2100436.419      204793.961     2100821.015      205413.373
#Sta/Elev= 30
       0  1945.8    18.3 1942.71    41.5 1936.85    80.1 1932.03    87.9  1928.6
   104.2 1924.76   122.6  1925.3   130.1 1924.12   149.1 1918.18   180.5 1910.79
   184.4 1909.15   192.1 1904.11   204.3 1898.99   215.3 1892.24   219.2 1891.14
   226.9 1890.82   237.6 1889.16   254.9 1890.57   269.4  1890.1   319.6 1890.78
   342.7 1889.83   357.61890.136   366.3  1887.9   372.71891.077   385.2 1896.99
   392.9  1899.3   516.5 1931.91   578.3 1944.17   620.8 1951.29   729.1 1964.59
#Mann= 3 ,-1 , 0
       0      .1       0   357.6    .045       0   372.7      .1       0
Bank Sta=357.6,372.7
XS Rating Curve= 0 ,0
Exp/Cntr=0.3,0.1

Type RM Length L Ch R = 1 ,2053    ,138.8,149.8,159.5
XS GIS Cut Line= 2
     2100191.149      204925.476 2100326.1818315205603.304539314
#Sta/Elev= 30
       0 1957.33      19 1952.13    35.7 1944.36    45.7 1946.14    59.1 1946.17
    79.2 1942.32      96 1936.97   112.7 1933.74   146.2 1924.45     202 1905.05
   213.1 1899.25     223 1896.43   239.7 1895.62   279.9 1887.31   323.4 1886.88
   333.4 1885.81   386.1 1886.17   393.6 1884.63   403.7 1887.53   427.1 1900.65
   433.5 1903.23   540.8 1934.82   560.9 1938.56   574.3 1944.95   604.4 1948.13
   614.4 1950.21   627.8 1950.48   634.7 1951.91   651.2 1958.23   691.1 1964.65
#Mann= 3 ,-1 , 0
       0      .1       0   386.1    .045       0   403.7      .1       0
Bank Sta=386.1,403.7
XS Rating Curve= 0 ,0
Exp/Cntr=0.5,0.3

Type RM Length L Ch R = 1 ,1903    ,35.7,36.1,38.7
XS GIS Cut Line= 4
      2100093.86      204966.8452100133.29881824205288.144452334
2100098.01064746205386.0406680492100179.55639326205676.217719103
#Sta/Elev= 30
       0 1974.84      19 1970.13    36.5 1964.26    66.3 1956.46    82.8 1950.61
     106 1944.25   145.6 1931.48   162.2 1927.07   175.4 1920.75   201.8 1909.97
   228.6 1899.83   241.5 1895.77   275.1 1888.55   284.5 1889.48   349.51885.987
   359.1 1884.01   366.7 1883.49     373 1883.64   378.31884.804   384.6 1886.43
   407.7 1886.53   415.4 1887.33     439 1894.81     473 1906.98   541.2 1929.95
   554.8 1933.73   571.9  1937.4   612.4 1948.41   667.3  1960.6   729.2 1969.31
#Mann= 3 ,-1 , 0
       0      .1       0   349.5    .045       0   378.3      .1       0
#XS Ineff= 2 , 0
             345 1888.33  382.62         1888.08
Permanent Ineff=
       F       F
Bank Sta=349.5,378.3
XS Rating Curve= 0 ,0
Exp/Cntr=0.5,0.3

Type RM Length L Ch R = 1 ,1867    ,209,197.5,174.8
XS GIS Cut Line= 4
2100054.05273258204990.7472651662100105.66021222205269.282355888
2100068.74423227205366.1996094462100156.31812359205692.151687641
#Sta/Elev= 30
       0  1981.2    35.9 1967.16    49.3 1964.27    79.3 1954.76     116 1944.74
   139.4 1934.63     146 1931.11   172.6 1923.66   186.1 1916.85   196.1  1910.9
   239.5 1895.34   266.2 1890.17   273.9 1887.68   282.3 1888.92   289.9 1888.88
   330.6  1885.7     339 1883.84     346 1883.29   349.6 1883.33   360.1 1885.75
   380.1 1884.81   408.5 1887.19   418.7 1891.67   513.8 1924.43   530.8 1929.52
   544.4  1932.5   595.3 1946.24   663.3 1961.08     691  1965.3   724.5 1968.62
#Mann= 3 ,-1 , 0
       0      .1       0   330.6    .045       0   360.1      .1       0
#XS Ineff= 2 , 0
          327.02  1888.4  365.17          1888.4
Permanent Ineff=
       F       F
Bank Sta=330.6,360.1
XS Rating Curve= 0 ,0
Exp/Cntr=0.5,0.3

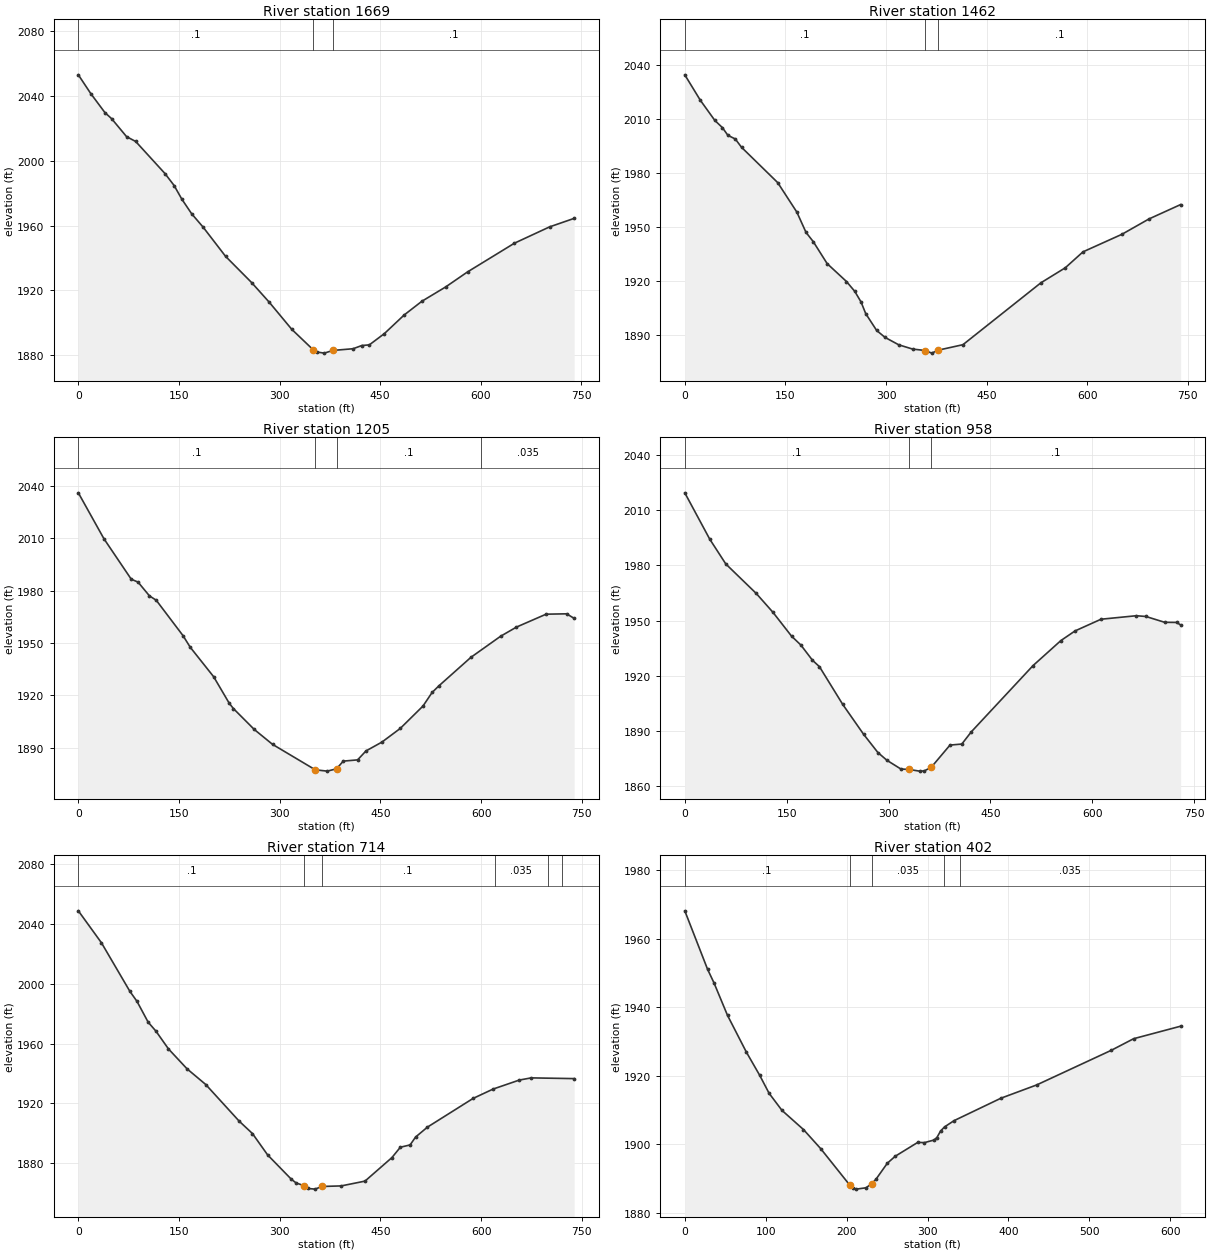
Type RM Length L Ch R = 1 ,1669    ,208.8,207.1,201.5
XS GIS Cut Line= 2
     2099742.754      205061.237     2100094.488       205711.29
#Sta/Elev= 30
       0 2052.87    18.6 2041.28    39.6 2029.62    49.6 2025.87    71.9 2014.78
    85.5 2011.81   129.1 1992.07   142.8 1984.67   154.2 1976.32   168.9 1967.28
     186 1959.03   219.5 1941.03   258.3 1924.88   284.6 1912.76   318.1 1896.09
   349.91883.535   355.4  1882.1   366.6  1881.4   379.41883.048   409.6 1884.11
   422.6 1886.09   433.8 1886.49   456.2 1893.43   485.8 1904.93   512.1 1913.35
   547.5 1922.16   580.2 1931.45   650.1 1949.14   702.4 1959.17   739.1 1964.43
#Mann= 3 ,-1 , 0
       0      .1       0   349.9    .045       0   379.4      .1       0
Bank Sta=349.9,379.4
XS Rating Curve= 0 ,0
Exp/Cntr=0.3,0.1

Type RM Length L Ch R = 1 ,1462    ,243.8,257,260.7
XS GIS Cut Line= 3
     2099539.016       205204.48     2099760.768      205498.331
     2100004.856       205777.66
#Sta/Elev= 30
       0 2034.79    23.1 2020.67    44.8  2009.4      56 2005.43    64.2 2001.14
    75.3 1999.07    84.6 1994.45   138.5  1974.8     167 1958.41   180.7  1947.1
   191.6  1941.9   212.2 1929.72     241 1919.77   253.3 1914.32   262.7 1908.39
   269.7 1901.89     286 1892.52   298.5 1888.66   318.9 1884.54   339.6 1882.17
   358.41881.367   368.1 1879.91   377.91881.577   414.6  1884.6   530.8 1919.04
   567.2 1927.41   593.6 1936.28   651.6 1946.04   691.8 1954.56   739.1 1962.59
#Mann= 3 ,-1 , 0
       0      .1       0   358.4    .045       0   377.9      .1       0
Bank Sta=358.4,377.9
XS Rating Curve= 0 ,0
Exp/Cntr=0.3,0.1

Type RM Length L Ch R = 1 ,1205    ,248,247.6,246.8
XS GIS Cut Line= 2
     2099442.227      205232.134     2099632.816       205945.73
#Sta/Elev= 30
       0 2036.04    38.1 2009.77    78.8 1986.59      89  1984.9   105.9 1977.05
   116.1 1974.51     156 1954.23   166.7 1947.62   201.6 1930.72   224.8 1915.54
     231 1912.51   262.1 1900.53   289.3 1892.01     353 1877.43   370.8 1876.68
   384.81878.032   394.6 1882.41     416 1883.12   428.5 1888.25   452.3 1893.32
   479.5 1901.11   513.4 1913.94     527 1921.72   537.2 1925.55   584.8 1941.84
   628.9 1953.88   652.7 1959.17   696.8 1966.55   727.4 1966.76   738.6 1964.15
#Mann= 4 ,-1 , 0
       0      .1       0     353    .045       0   384.8      .1       0
     600    .035       0
Bank Sta=353,384.8
XS Rating Curve= 0 ,0
Exp/Cntr=0.3,0.1

Type RM Length L Ch R = 1 ,958     ,242.3,243.8,240.7
XS GIS Cut Line= 3
     2099199.257      205318.458     2099304.755      205669.058
     2099424.574      206012.742
#Sta/Elev= 30
       0 2019.52    36.7 1994.31    60.4 1980.78   105.2 1964.74   129.8 1954.47
   157.2 1941.48   170.9 1936.65     188 1928.36   198.3 1924.85   232.6 1904.29
   263.2  1888.1   284.3 1878.13   297.7 1873.87   318.2 1869.14   330.21868.899
   345.6 1867.99   352.5 1868.09   362.91870.085   390.5 1882.17   407.9 1882.73
   421.8 1889.35   512.8 1925.46   553.8 1939.08   574.7 1944.34   612.9  1950.7
   664.8  1952.6   678.9  1952.2   706.7 1949.01   724.1 1948.95   730.1  1947.6
#Mann= 3 ,-1 , 0
       0      .1       0   330.2    .045       0   362.9      .1       0
Bank Sta=330.2,362.9
XS Rating Curve= 0 ,0
Exp/Cntr=0.3,0.1

Type RM Length L Ch R = 1 ,714     ,307.2,311.9,292
XS GIS Cut Line= 2
     2098935.197      205341.986     2099211.291      206027.051
#Sta/Elev= 30
       0 2048.75    34.4 2027.42    76.8 1994.94    87.4 1988.24     104 1974.35
   115.7  1968.3   134.3 1956.46     162 1943.14   189.8 1932.69   239.5 1908.25
   259.4 1899.91     282 1885.63   317.3 1869.39   324.4 1866.92   336.61865.017
   342.1 1863.21   352.7 1862.78   362.81864.555   391.6 1864.93     427 1868.13
   467.1 1883.84   479.7 1890.78   494.2 1892.32   502.4 1897.58     520  1904.2
   588.1 1923.41     618 1929.67   656.9 1935.66   674.6 1937.12   738.6 1936.63
#Mann= 6 ,-1 , 0
       0      .1       0   336.6    .045       0   362.8      .1       0
     620    .035       0     700      .1       0     720    .035       0
Bank Sta=336.6,362.8
XS Rating Curve= 0 ,0
Exp/Cntr=0.3,0.1

Type RM Length L Ch R = 1 ,402     ,170.1,169,164.4
XS GIS Cut Line= 3
     2098719.777      205632.963     2098924.605       205926.55
     2099165.847      206008.482
#Sta/Elev= 30
       0 1968.11    28.1 1951.09    36.1 1947.09    52.8 1937.62    76.1 1926.91
    92.5 1920.18   104.2  1914.9   120.1 1909.92   146.7 1904.33   167.9 1898.78
   203.7 1888.19   208.1 1887.22   212.1 1886.96   224.1 1887.36   231.11888.567
   236.1 1889.78   250.3 1894.51   260.1 1896.55   287.9 1900.59   296.1 1900.52
   308.1 1901.28   311.6 1902.01   316.1 1903.89     321  1905.1   332.8 1906.93
   390.7 1913.47   434.9 1917.34   527.2 1927.45   554.7 1930.82   612.8 1934.47
#Mann= 5 ,-1 , 0
       0      .1       0   203.7    .045       0   231.1    .035       0
     320      .1       0     340    .035       0
Bank Sta=203.7,231.1
XS Rating Curve= 0 ,0
Exp/Cntr=0.3,0.1