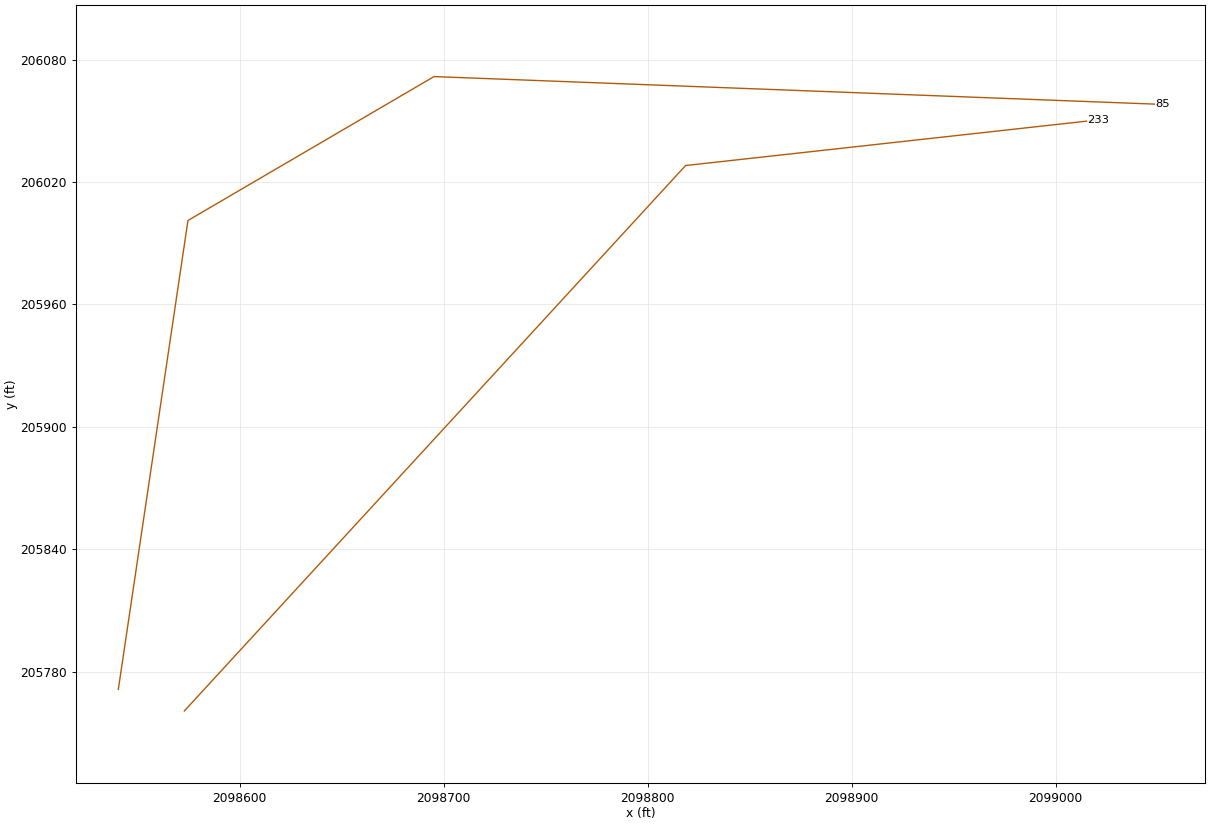
HEC-RAS study TCKTTBR.prj: TCKTTBR

--- TCKTTBR.g01 (geometry) --- (continued)

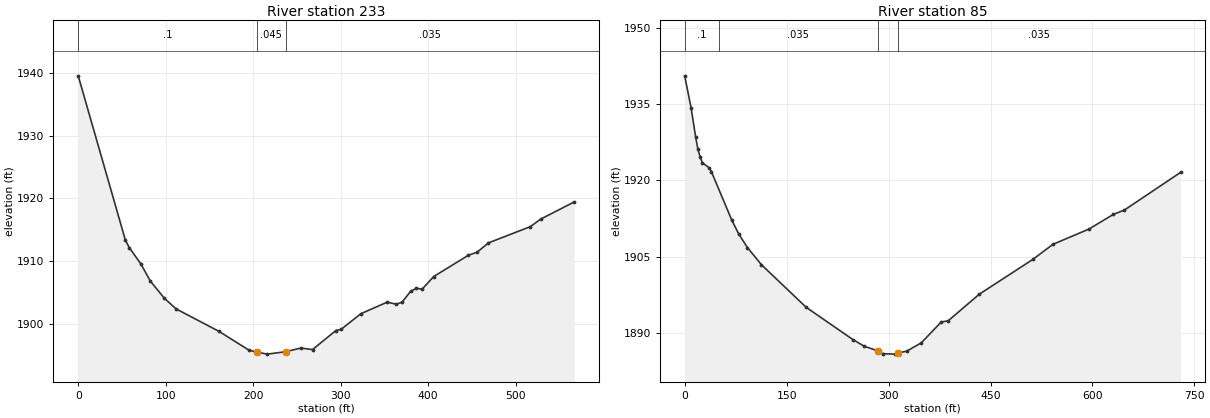
Type RM Length L Ch R = 1 ,233     ,150,147.5,137.7
XS GIS Cut Line= 3
2098572.88016823205760.6880956552098818.59614086206028.062923014
2099020.99440403206050.468634804
#Sta/Elev= 30
       0 1939.55    53.9 1913.32    58.3 1912.14    71.7  1909.5    82.4 1906.79
    98.4 1904.05   111.8 1902.35   160.8 1898.76   195.2 1895.75   204.5 1895.43
   216.1 1895.12     237  1895.5   254.4 1896.09   267.8 1895.85   294.5 1898.89
   300.5 1899.08   322.9 1901.56   353.1 1903.42   363.4 1903.09     370 1903.39
   379.9 1905.15   386.5 1905.62   393.1  1905.5   406.3 1907.51     446 1910.91
   455.9 1911.39   468.9 1912.88   516.7 1915.47   528.6 1916.68   566.8 1919.41
#Mann= 3 ,-1 , 0
       0      .1       0   204.5    .045       0     237    .035       0
Bank Sta=204.5,237
XS Rating Curve= 0 ,0
Exp/Cntr(USF)=0,0
Exp/Cntr=0.3,0.1

Type RM Length L Ch R = 1 ,85      ,53.1,55.1,56.7
XS GIS Cut Line= 4
     2098540.511      205771.262      2098574.65      206001.125
     2098695.271      206071.677     2099052.582      206058.022
#Sta/Elev= 30
       0 1940.57     9.5 1934.24    16.2 1928.48    19.5 1926.13    22.8  1924.6
    26.1 1923.47    36.1  1922.5    39.4 1921.71    69.2 1912.24    79.2 1909.56
    92.4 1906.81     113 1903.44   178.7 1895.08   247.4 1888.74   264.2 1887.42
   284.4  1886.5   291.1 1885.96   309.7 1885.87   313.6 1886.11   326.5 1886.44
   348.1 1888.09   377.6  1892.2   387.5  1892.4   433.5 1897.65   512.3 1904.49
   541.8 1907.45   594.7 1910.44   630.5 1913.32   646.9 1914.18   729.7  1921.6
#Mann= 4 ,-1 , 0
       0      .1       0      50    .035       0   284.4    .045       0
   313.6    .035       0
Bank Sta=284.4,313.6
XS Rating Curve= 0 ,0
Exp/Cntr=0.3,0.1
LCMann Table=0

Chan Stop Cuts=-1
Use User Specified Reach Order=0
Composite Channel Slope=5